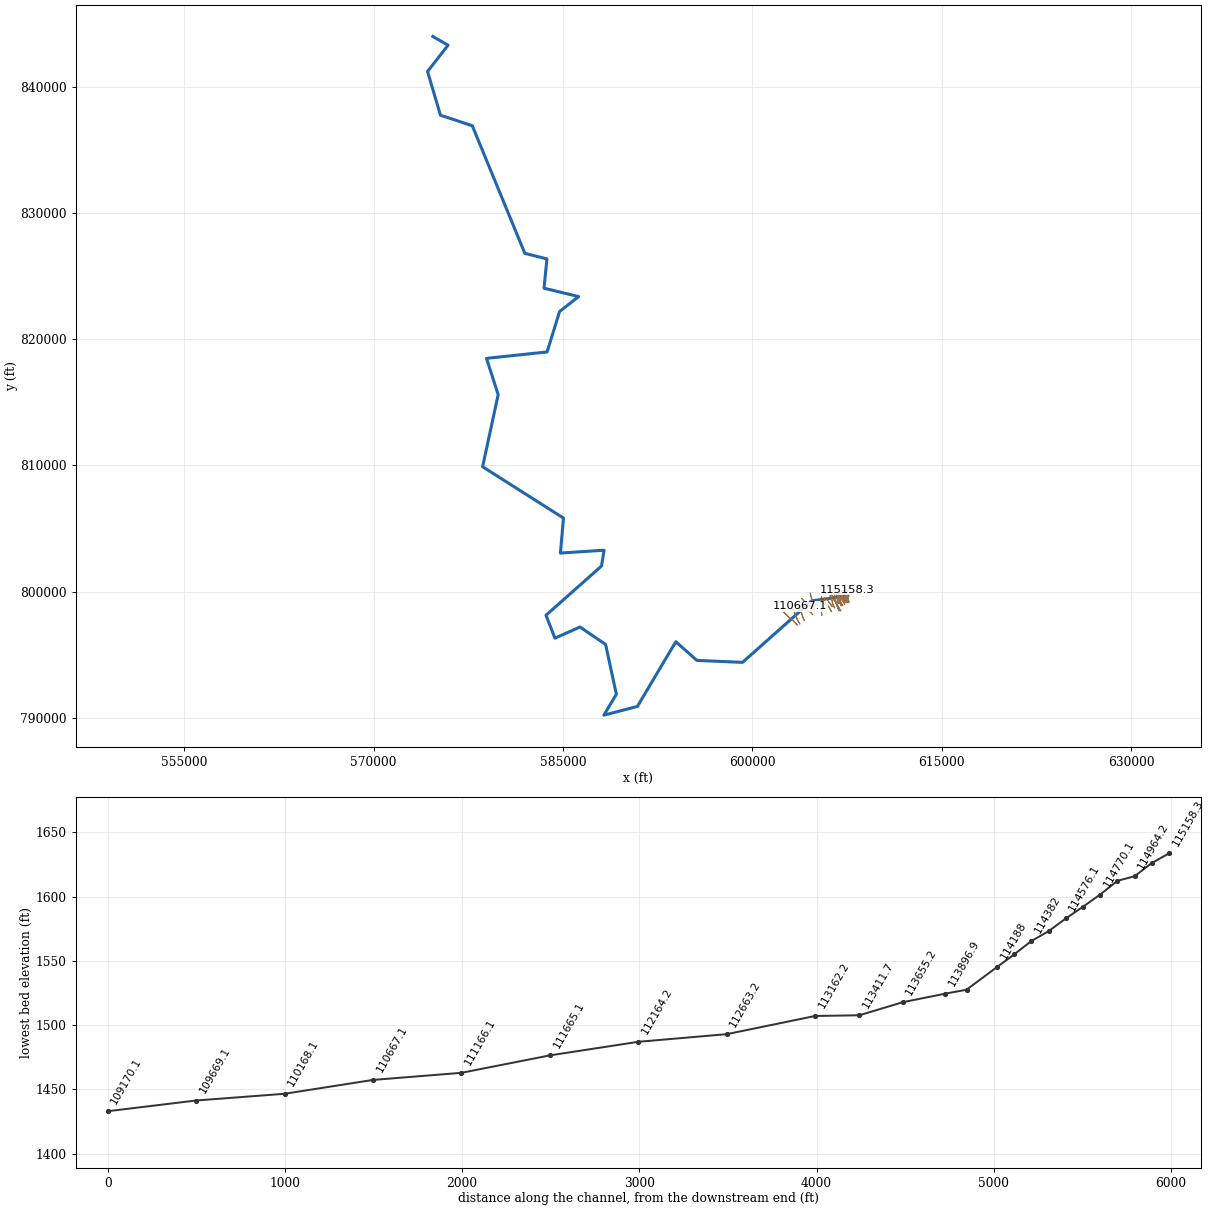
--- 10395_ras.prj (project) ---

Proj Title=10395
Current Plan=p01
Default Exp/Contr=0.3,0.1
English Units
Geom File=g01
Flow File=f01
Plan File=p01
Y Axis Title=Elevation
X Axis Title(PF)=Main Channel Distance
X Axis Title(XS)=Station
BEGIN DESCRIPTION:
RFD model 10395 exported to HEC-RAS
END DESCRIPTION:

--- 10395_ras.p01 (plan) ---

Plan Title=Plan 01
Program Version=4.10
Short Identifier=Plan 01
Geom File=g01
Flow File=f01
Subcritical Flow
Calc Critical at every XS
Secant Critical Depth

--- 10395_ras.f01 (steady flow) ---

Flow Title=Flow 01
Program Version=5.01
Number of Profiles= 6
Profile Names=10yr,25yr,50yr,100yr,100plus,500yr
River Rch & RM=10395,211,115158.3
  858.41 1340.81 1784.33 2172.55 3171.93 4256.24
River Rch & RM=10395,211,115061.2
  860.29 1343.79 1788.36 2177.51 3179.17 4264.82
River Rch & RM=10395,211,114964.2
  862.78 1347.77 1793.73 2184.13 3188.82 4276.25
River Rch & RM=10395,211,114867.2
  864.34 1350.26 1797.08 2188.26 3194.85 4283.39
River Rch & RM=10395,211,114770.1
  881.62 1377.87 1834.41 2234.27 3262.04 4363.02
River Rch & RM=10395,211,114673.1
  883.67  1381.2 1838.94 2239.91 3270.26 4372.93
River Rch & RM=10395,211,114576.1
  886.96 1386.49 1846.14 2248.82 3283.28 4388.49
River Rch & RM=10395,211,  114479
  892.23 1395.03 1857.78 2263.28 3304.39 4413.91
River Rch & RM=10395,211,  114382
  893.64 1397.35 1860.95 2267.24 3310.17 4420.96
River Rch & RM=10395,211,  114188
  895.92 1401.07 1866.05  2273.6 3319.45 4432.23
River Rch & RM=10395,211,  114016
  897.95 1404.36 1870.55 2279.19 3327.62 4442.08
River Rch & RM=10395,211,113896.9
   926.6 1450.45  1933.1  2356.6 3440.64 4576.35
River Rch & RM=10395,211,113655.2
11782.4819738.9227849.3838268.8557433.6774425.65
River Rch & RM=10395,211,113411.7
   1187019861.5427999.8638446.8257700.78 74654.7
River Rch & RM=10395,211,113162.2
 11873.9   1986728006.5638454.7557712.6774664.89
River Rch & RM=10395,211,112663.2
11886.2119884.2428027.7138479.75 57750.274697.03
River Rch & RM=10395,211,112164.2
11896.6719898.8828045.6638500.9757782.0474724.32
River Rch & RM=10395,211,111665.1
12101.3820185.0228396.2738915.0558403.4875255.59
River Rch & RM=10395,211,111166.1
12174.0820286.4528520.3939061.4658623.2375442.99
River Rch & RM=10395,211,110667.1
12184.5520301.0628538.2639082.5358654.8475469.95
River Rch & RM=10395,211,110168.1
 12262.720409.9528671.42 39239.558890.4375670.55
River Rch & RM=10395,211,109669.1
12275.5220427.8128693.2439265.2258929.03 75703.4
River Rch & RM=10395,211,109170.1
12350.0420531.5428819.9839414.5159153.0875893.89
River Rch & RM=10395,211,108920.6
12355.4220539.0228829.1339425.2859169.2475907.63
River Rch & RM=10395,211,108421.5
12368.5720557.3128851.4639451.5859208.7175941.16
River Rch & RM=10395,211,  108157
12376.5320568.3828864.98 39467.5 59232.675961.45
River Rch & RM=10395,211,108021.8
12381.3120575.0328873.0939477.0559246.9375973.63
River Rch & RM=10395,211,107848.1
12387.6720583.88 28883.939489.7759266.0375989.84
River Rch & RM=10395,211,107423.5
12395.6320594.9428897.4139505.6759289.8976010.09
River Rch & RM=10395,211,107169.4
12446.2420665.2928983.2839606.7359441.5776138.82
River Rch & RM=10395,211,107066.8
12446.6320665.8428983.9539607.5359442.7576139.83
River Rch & RM=10395,211,106425.5
14780.2223861.9132847.4444113.3966205.1381771.38
River Rch & RM=10395,211,105926.5
14869.0523981.8732991.0844279.4466454.3481975.11
River Rch & RM=10395,211,105638.8
14870.9623984.4532994.16   4428366459.6981979.48
River Rch & RM=10395,211,105529.8
14871.8323985.6232995.5744284.6266462.1181981.46
River Rch & RM=10395,211,105177.9
14874.0823988.6632999.2144288.8366468.4381986.63
River Rch & RM=10395,211,104690.3
15141.2524348.7133429.7844785.9667214.5282594.95
River Rch & RM=10395,211,103714.9
15282.9424539.25 33657.3 45048.367608.2382915.05
River Rch & RM=10395,211,102251.9
15338.4324613.7933746.2545150.7967762.0583039.92
River Rch & RM=10395,211,101456.3
15353.6824634.2633770.6745178.9267804.2783074.19
River Rch & RM=10395,211,100788.9
15368.7524654.49 33794.845206.7167845.9883108.02
River Rch & RM=10395,211, 99813.5
15416.2424718.2333870.8145294.2567977.3683214.58
River Rch & RM=10395,211,98838.15
15439.1924749.0233907.5245336.5168040.7883265.98
River Rch & RM=10395,211,98350.47
16140.6125686.5135022.4746617.2469962.8984816.45
River Rch & RM=10395,211, 97862.8
16146.9725694.9835032.5246628.7569980.1684830.32
River Rch & RM=10395,211,97375.12
16326.0825933.2935315.07 46952.4 70465.985219.81
River Rch & RM=10395,211,96887.45
 16333.225942.7535326.2846965.2370485.1585235.23
River Rch & RM=10395,211,96399.77
16397.2926027.9135427.1647080.6970658.4385373.95
River Rch & RM=10395,211, 95912.1
16405.18 26038.435439.5947094.9170679.7785391.02
River Rch & RM=10395,211,94936.75
16438.0326082.0235491.2447154.0170768.4785461.98
River Rch & RM=10395,211,94449.07
16690.63   2641735887.5747607.0571448.3986004.89
River Rch & RM=10395,211,93201.53
18336.0228579.4338430.6450497.9175786.9889429.06
River Rch & RM=10395,211,92808.31
18341.3628586.3938438.7950507.12 75800.889439.87
River Rch & RM=10395,211,92526.51
18352.7728601.27 38456.250526.8275830.3789462.96
River Rch & RM=10395,211,92402.55
18353.9628602.8238458.0150528.8675833.4389465.37
River Rch & RM=10395,211, 92203.5
18357.0628606.8838462.7550534.2375841.4989471.66
River Rch & RM=10395,211,91705.26
 18384.628642.7838504.7550581.75 75912.889527.36
River Rch & RM=10395,211,91207.02
18396.2928658.0138522.58 50601.975943.0589550.99
River Rch & RM=10395,211,90708.78
18404.86 28669.238535.6550616.6975965.2489568.33
River Rch & RM=10395,211,90034.52
18421.4128690.7738560.8850645.2376008.0789601.76
River Rch & RM=10395,211,89214.07
19540.5430142.3240253.0352553.1178871.4191823.23
River Rch & RM=10395,211, 87813.6
19711.85 30363.3 40509.752841.5279304.2792156.66
River Rch & RM=10395,211,86722.87
19843.6630533.1240706.7753062.7979636.3492412.05
River Rch & RM=10395,211,86224.64
19861.2630555.7840733.06 53092.379680.6392446.07
River Rch & RM=10395,211, 85726.4
19866.8530562.96 40741.453101.6679694.6792456.87
River Rch & RM=10395,211,85228.16
19889.4530592.0640775.1653139.5379751.5192500.54
River Rch & RM=10395,211,84729.92
19906.19 30613.640800.1353167.5679793.5892532.84
River Rch & RM=10395,211,84329.21
19935.8630651.7840844.4153217.2479868.14 92590.1
River Rch & RM=10395,211,83699.99
19960.0830682.9440880.5353257.7679928.9592636.79
River Rch & RM=10395,211, 83235.2
20004.6930740.3340947.0653332.3880040.9392722.71
River Rch & RM=10395,211,82736.97
20019.8330759.7940969.6153357.67 80078.992751.84
River Rch & RM=10395,211,82238.73
20039.1130784.5840998.3453389.8980127.2692788.94
River Rch & RM=10395,211,81740.49
20065.5930818.6241037.7953434.1180193.6292839.82
River Rch & RM=10395,211,81242.25
20072.5230827.5241048.1153445.6880210.9892853.13
River Rch & RM=10395,211,80999.76
20074.0430829.4841050.3853448.23 80214.892856.05
River Rch & RM=10395,211,80883.51
20142.3930917.2941152.0953562.2580385.92 92987.2
River Rch & RM=10395,211,80757.28
20148.3330924.9241160.9353572.1580400.7992998.59
River Rch & RM=10395,211,80514.79
20150.8130928.1241164.63 53576.380407.0193003.36
River Rch & RM=10395,211, 80272.3
20154.6830933.0841170.3853582.7480416.6893010.77
River Rch & RM=10395,211,80029.82
20157.8630937.1641175.1153588.0480424.6393016.85
River Rch & RM=10395,211,79787.33
20159.9330939.8241178.1953591.4980429.8193020.82
River Rch & RM=10395,211,79592.48
20168.6330950.9941191.1353605.9880451.5693037.48
River Rch & RM=10395,211,79302.35
20173.8730957.7341198.9353614.7380464.6893047.53
River Rch & RM=10395,211,78817.38
 20181.630967.6541210.41 53627.680484.0193062.33
River Rch & RM=10395,211,78574.89
20183.5330970.1341213.2953630.8280488.8493066.03
River Rch & RM=10395,211, 78332.4
20200.3530991.73 41238.353658.85 80530.993098.23
River Rch & RM=10395,211,78089.92
20220.7531017.9241268.6253692.8180581.8893137.26
River Rch & RM=10395,211,77604.94
20229.7131029.4141281.9353707.7280604.2493154.38
River Rch & RM=10395,211,77362.46
20233.1531033.8341287.0453713.4580612.8493160.96
River Rch & RM=10395,211,77034.84
20247.1931051.8541307.9153736.8280647.92 93187.8
River Rch & RM=10395,211,76634.99
20255.0331061.9241319.5653749.8780667.5193202.79
River Rch & RM=10395,211,76150.02
20263.5631072.8741332.2353764.06 80688.893219.09
River Rch & RM=10395,211,75665.05
20269.6231080.6341341.2153774.1380703.9193230.65
River Rch & RM=10395,211,75270.87
 20329.131156.9441429.5253873.0280852.3293344.16
River Rch & RM=10395,211,74684.61
23085.5834655.11 45448.8   5834487562.3598405.24
River Rch & RM=10395,211,74194.39
23094.5634666.3945461.6858358.2387583.7198421.14
River Rch & RM=10395,211,73704.17
23106.0334680.7945478.1258376.4187610.9898441.43
River Rch & RM=10395,211,73355.31
23261.2234875.6145700.3458621.9387979.4798715.45
River Rch & RM=10395,211,73271.29
23261.8434876.3945701.2358622.9287980.9598716.54
River Rch & RM=10395,211,72937.52
23368.8235010.5745854.1958791.8288234.4498904.81
River Rch & RM=10395,211,72489.62
23386.3735032.5745879.26 58819.588275.9798935.65
River Rch & RM=10395,211,72041.73
23423.41   3507945932.1658877.8988363.6199000.68
River Rch & RM=10395,211,71593.83
 23430.2 35087.545941.8658888.5988379.66 99012.6
River Rch & RM=10395,211,71369.89
23433.1635091.2145946.0858893.2588386.66 99017.8
River Rch & RM=10395,211,70921.99
23474.8335143.4246005.5558958.8988485.1699090.87
River Rch & RM=10395,211, 70426.8
23489.6135161.9346026.6458982.1688520.0999116.77
River Rch & RM=10395,211,69931.61
23514.5935193.2346062.29 59021.588579.1399160.54
River Rch & RM=10395,211,69436.43
23564.3835255.58 46133.359099.8288696.6899247.67
River Rch & RM=10395,211,68941.24
23581.2135276.6446157.2859126.2888736.3899277.09
River Rch & RM=10395,211,68446.05
23593.6135292.1646174.9559145.7688765.6399298.76
River Rch & RM=10395,211,68198.46
23602.9335303.8446188.2459160.4288787.6399315.05
River Rch & RM=10395,211,67950.86
23608.58 35310.946196.2859169.2988800.9599324.91
River Rch & RM=10395,211,67703.27
23610.4235313.21 46198.959172.1888805.2799328.13
River Rch & RM=10395,211,67208.08
23620.2335325.4846212.88 59187.688828.4199345.27
River Rch & RM=10395,211,66712.89
 23634.235342.9846232.7959209.5588861.3799369.67
River Rch & RM=10395,211,66217.71
23643.6435354.7946246.2359224.3888883.6299386.15
River Rch & RM=10395,211, 65825.1
24091.5135914.3646882.5259925.3389935.59100163.6
River Rch & RM=10395,211,65474.93
24112.7735940.8846912.6359958.4789985.34100200.3
River Rch & RM=10395,211,64979.74
24134.0135967.3846942.7359991.5990035.04  100237
River Rch & RM=10395,211,64484.55
24217.6436071.6547061.1360121.8690230.55100381.1
River Rch & RM=10395,211,63989.36
24222.4636077.6547067.9460129.3590241.79100389.3
River Rch & RM=10395,211,63494.17
24265.27   36131 47128.560195.9690341.76  100463
River Rch & RM=10395,211,62998.99
24299.86 36174.147177.4160249.7590422.48100522.4
River Rch & RM=10395,211, 62503.8
 24305.536181.1347185.3960258.5290435.65100532.1
River Rch & RM=10395,211, 62256.2
24308.2636184.5747189.2960262.8190442.09100536.8
River Rch & RM=10395,211,62008.61
 24313.936191.5947197.2660271.5890455.25100546.5
River Rch & RM=10395,211,61761.02
24316.5436194.8847200.9960275.6890461.41100551.1
River Rch & RM=10395,211,61513.42
24320.3836199.6647206.4260281.6590470.36100557.7
River Rch & RM=10395,211,61265.83
24322.5436202.3547209.47   6028590475.39100561.4
River Rch & RM=10395,211,60770.64
24362.8236252.5247266.3960347.5990569.32100630.5
River Rch & RM=10395,211,60275.45
24394.3236291.7347310.8860396.4990642.71100684.5
River Rch & RM=10395,211,59780.27
24415.6236318.2547340.9660429.5490692.32  100721
River Rch & RM=10395,211,59285.08
24428.5336334.33 47359.260449.5990722.41100743.1
River Rch & RM=10395,211,58789.89
24441.0936349.9547376.9160469.0690751.63100764.6
River Rch & RM=10395,211,58094.26
24493.04 36414.647450.2260549.6290872.53100853.5
River Rch & RM=10395,211,57198.19
24693.0336663.2547732.0460859.1491337.06101194.6
River Rch & RM=10395,211,56302.12
24773.9436763.7647845.88 60984.1 91524.6101332.2
River Rch & RM=10395,211,54726.83
24846.0436853.2747947.2361095.3291691.52101454.5
River Rch & RM=10395,211,52309.35
23043.0237295.98 50947.963208.4492284.32 79920.9
River Rch & RM=10395,211,50312.96
23375.7337862.3851747.1664227.6893772.4281103.12
River Rch & RM=10395,211,48316.57
 23468.238018.4851966.3464505.9894178.7381422.08
River Rch & RM=10395,211,46320.19
24318.7739461.1353997.8267091.7997954.0284394.16
River Rch & RM=10395,211, 44323.8
24408.1339615.09 54216.7 67372.798364.1484722.34
River Rch & RM=10395,211,42327.41
24573.3939897.6954616.6467883.9899110.6185313.73
River Rch & RM=10395,211, 42141.5
24583.6339915.3254641.6867916.1299157.53 85351.2
River Rch & RM=10395,211,41649.69
24600.9139944.9854683.7567969.9999236.1985413.77
River Rch & RM=10395,211,41157.88
24606.21 39954.154696.7167986.6399260.4885433.14
River Rch & RM=10395,211,40666.06
24689.0340095.6754897.04 68242.799634.3585728.95
River Rch & RM=10395,211,40174.25
24714.2840139.3554959.2768322.7299751.1785822.63
River Rch & RM=10395,211,39682.44
24719.3440148.1154971.7768338.8199774.6785841.54
River Rch & RM=10395,211,39190.62
24748.0740198.0255043.08 68430.799908.8385949.67
River Rch & RM=10395,211,38698.81
24756.1840212.1555063.2868456.7799946.8985980.44
River Rch & RM=10395,211,   38207
24794.7540279.1855159.0768580.27100127.286125.83
River Rch & RM=10395,211,37715.18
24817.3640318.61 55215.568653.12100233.686211.88
River Rch & RM=10395,211,37223.37
24828.7140338.4355243.9268689.84100287.286255.32
River Rch & RM=10395,211,36731.56
24843.9340365.0255282.0468739.11100359.186313.67
River Rch & RM=10395,211,36425.17
24894.5140452.9655407.74 68901.2100595.886504.45
River Rch & RM=10395,211,36177.61
24907.5340475.61 55440.168942.91100656.786553.53
River Rch & RM=10395,211,35737.51
24917.9940493.7955466.0968976.43100705.686592.97
River Rch & RM=10395,211,35297.41
24968.4440581.0655590.4569136.35100939.186779.99
River Rch & RM=10395,211,34857.31
24974.6640591.8955605.9669156.38100968.386803.63
River Rch & RM=10395,211,34417.21
25088.1340787.0955883.2169511.95101487.487216.48
River Rch & RM=10395,211,34183.17
25097.33 40803.255906.3269541.84101531.187251.88
River Rch & RM=10395,211,33949.12
25102.6740812.5455919.7269559.17101556.4 87272.4
River Rch & RM=10395,211,33715.08
25115.3840834.7855951.6469600.48101616.787321.32
River Rch & RM=10395,211,33481.04
25119.4740841.9455961.9169613.77101636.187337.05
River Rch & RM=10395,211,33246.99
25122.9840848.0855970.7369625.18101652.887350.59
River Rch & RM=10395,211,33012.95
25130.6340861.5155990.0469650.18101689.387380.27
River Rch & RM=10395,211,32765.92
25140.4940878.8456014.9569682.49101736.4 87418.7
River Rch & RM=10395,211,32555.15
25143.0740883.3756021.4769690.92101748.887428.73
River Rch & RM=10395,211,32174.85
25145.8740888.2956028.5569700.11101762.287439.65
River Rch & RM=10395,211,32066.01
25152.2640899.52 56044.769721.03101792.787464.53
River Rch & RM=10395,211,31831.97
25155.0740904.4656051.7969730.22101806.187475.43
River Rch & RM=10395,211,31597.92
 25158.840910.9956061.1769742.37101823.987489.84
River Rch & RM=10395,211,31363.88
25161.1840915.1556067.1569750.09101835.1   87499
River Rch & RM=10395,211, 30880.4
25243.7841058.3456271.4670013.14102219.287806.88
River Rch & RM=10395,211,30396.91
25294.0841145.7556396.39 70174.2102454.387995.93
River Rch & RM=10395,211,29913.43
25306.4441167.3356427.2870214.11102512.688042.95
River Rch & RM=10395,211,29429.95
25316.4741184.8456452.3970246.57  10256088081.25
River Rch & RM=10395,211,28946.46
25325.9441201.3756476.0870277.19102604.788117.37
River Rch & RM=10395,211,28462.98
25333.5441214.6756495.1670301.86102640.788146.53
River Rch & RM=10395,211, 27979.5
25340.7641227.3256513.3270325.37  10267588174.38
River Rch & RM=10395,211,27496.01
25347.5341239.1856530.3670347.41102707.288200.48
River Rch & RM=10395,211,27012.53
 25380.441296.8856613.2870454.86102864.1 88327.9
River Rch & RM=10395,211,26529.05
25392.8141318.63 56644.570495.27102923.188375.72
River Rch & RM=10395,211,26045.56
25397.4341326.6556655.9870510.07102944.7 88393.1
River Rch & RM=10395,211,25562.08
25407.0141343.3256679.81 70540.8102989.688429.18
River Rch & RM=10395,211, 25078.6
25663.3341783.6757304.8671341.96104159.389355.09
River Rch & RM=10395,211,24595.11
25665.6241787.5957310.43 71349.1104169.789363.32
River Rch & RM=10395,211,24111.63
25697.4241841.84 57387.171447.01104312.689475.38
River Rch & RM=10395,211,23951.39
25698.9941844.5357390.9171451.89104319.8   89481
River Rch & RM=10395,211,23450.23
25702.1241849.9157398.5471461.66  10433489492.25
River Rch & RM=10395,211,23002.94
26010.7242381.6358154.6372432.27105751.190615.82
River Rch & RM=10395,211,22555.66
26016.44 42391.458168.4572449.95105776.990636.05
River Rch & RM=10395,211,22108.37
26029.5142413.6458199.8572489.99105835.490681.66
River Rch & RM=10395,211,21661.09
26048.6442445.9558245.2372547.64105919.690746.63
River Rch & RM=10395,211,20724.07
26197.9942699.0258601.4973000.98106581.4 91259.7
River Rch & RM=10395,211,19914.83
26294.4342860.0458826.1373284.56106995.591574.11
River Rch & RM=10395,211,18850.02
26327.2142914.3358901.4773379.24107133.791677.83
River Rch & RM=10395,211,17525.35
26630.7343419.3459604.4474264.86108426.792653.53
River Rch & RM=10395,211,16038.96
26774.7843655.1959929.36 74670.4109018.8 93089.2
River Rch & RM=10395,211,14164.92
39646.8864940.1689447.95  111723163115.5132238.3
River Rch & RM=10395,211,13227.89
39660.7664962.85 89479.2111761.9163172.4132277.6
River Rch & RM=10395,211,12290.87
39800.6465191.15 89793.2  112153163743.3132671.4
River Rch & RM=10395,211,11353.85
39805.1365198.4689803.26112165.5163761.6  132684
River Rch & RM=10395,211,10416.83
39822.2165226.3189841.52112213.1163831.1132731.8
River Rch & RM=10395,211,9479.807
39849.1665270.3789902.19112288.7163941.5132808.1
River Rch & RM=10395,211,7605.764
39849.8265271.4489903.65112290.5163944.2132809.9
Boundary for River Rch & Prof#=10395,211,1
Up Type= 0
Dn Type= 2
Boundary for River Rch & Prof#=10395,211,2
Up Type= 0
Dn Type= 2
Boundary for River Rch & Prof#=10395,211,2
Up Type= 0
Dn Type= 2
Boundary for River Rch & Prof#=10395,211,2
Up Type= 0
Dn Type= 2
Boundary for River Rch & Prof#=10395,211,2
Up Type= 0
Dn Type= 2
Boundary for River Rch & Prof#=10395,211,2
Up Type= 0
Dn Type= 2

--- 10395_ras.g01 (geometry) ---

Geom Title=10395
Program Version=4.10

River Reach=10395,211
Reach XY= 30
607552.352739841799658.186770827604701.038300037799258.846299529
599217.704966635794385.929632857595601.283446044794543.425636217
593932.880668044796022.592302918590890.418283939790897.013599217
588233.065781444790203.629963413589223.751617104791860.555265859
588372.137726158795809.188784286586338.704396009797190.357671246
584358.897225499796302.569586307583650.711501241798120.444751039
588046.510943025802014.555371046588249.793284088803270.603008911
584791.199069113803045.355449334585036.590276688805815.241612867
578629.194775015809884.906665057579860.997104228815596.569941923
578937.579366207818468.915852502583736.652329892818977.692915156
584725.987464994822179.906851098586235.524620712823361.278645471
583491.601009488824030.115451053583725.976009548826347.823784381
581974.703797549826785.873834074577812.444984674836895.544948921
575290.482156068837730.553977206 574267.12184307 841192.55758068
575892.457384795843279.619469002574687.260731876843963.390913993

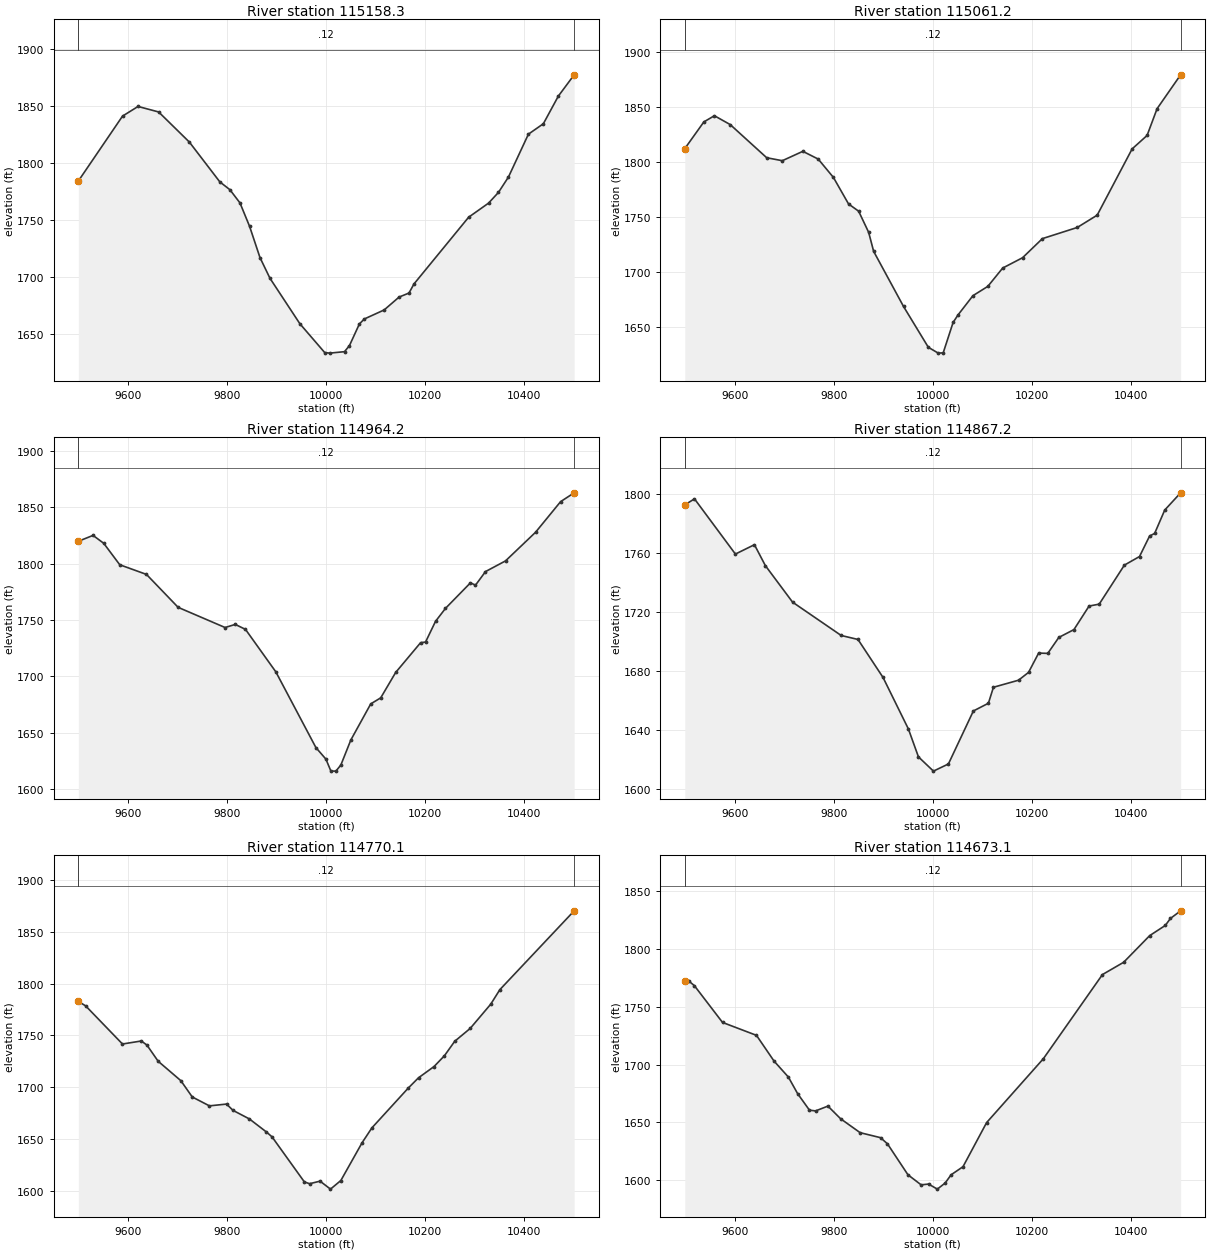
Type RM Length L Ch R = 1 ,115158.3,97.031000,97.031000,97.031000
XS GIS Cut Line= 6
607656.571625012799170.248803228607597.369532389799361.327126972
607567.187790776799504.121928615607554.694897118799608.213002249
607533.660839257799901.497233868607504.031462908800156.745231419
#Sta/Elev= 30
9499.0531784.1919588.3531841.0069619.7131849.4569661.3341844.642 9723.461818.271
9784.9991783.4689805.3391776.621 9825.681765.0669845.1271744.5419866.1551717.195
9886.2981699.1339946.7291659.3489996.8581634.15910006.881633.63810036.93 1634.91
10046.951640.25410066.991659.169   100771663.52310117.08 1671.4310147.181682.676
10167.251686.21610177.291694.16110287.771752.55210327.991764.865 10348.11774.306
10368.251787.72610408.551825.20910438.781834.34710469.011858.50310500.99 1877.13
#Mann= 3 , 0 , 0
9499.053    0.12       09499.053    0.12       010500.99    0.12       0
#XS Ineff= 2 , 0
       0                               0
Bank Sta=9499.053,10500.99
Exp/Cntr=0.3,0.1

Type RM Length L Ch R = 1 ,115061.2,97.031100,97.031100,97.031100
XS GIS Cut Line= 6
607569.231371136799168.852118113607503.759252416799357.882532752
607467.459204359799513.592391934607456.908824204799603.821160087
607440.307324736799874.027916101607406.191167071800152.189654554
#Sta/Elev= 30
9499.071 1812.079537.5781836.3259558.8841841.9579590.8421833.9049664.5731803.768
9696.1221801.0719737.6011809.5949768.6771802.5449799.3561785.8899829.9571761.756
9850.3581755.1759870.6081735.9319880.6771718.6589941.0851668.5559991.197 1631.45
10011.221626.16510021.231626.43410041.251654.08510051.261660.93810081.291678.378
10111.351686.82710141.441703.49410181.571712.874 10221.7 1730.2510292.121740.384
10332.361751.57310402.941811.775 10433.21824.02210453.381848.32610500.981879.131
#Mann= 3 , 0 , 0
9499.071    0.12       09499.071    0.12       010500.98    0.12       0
#XS Ineff= 2 , 0
       0                               0
Bank Sta=9499.071,10500.98
Exp/Cntr=0.3,0.1

Type RM Length L Ch R = 1 ,114964.2,97.031000,97.031000,97.031000
XS GIS Cut Line= 6
607499.866132522799167.443240287607416.891570037799379.081191181
607380.253284403799506.580218706607363.845017534799600.461755204
607328.138736235799901.443916371607291.259025186800142.096470767
#Sta/Elev= 30
9499.0511819.7869528.7981824.9999550.3881817.9849582.7741798.9449636.7471790.386
9700.7231761.1689795.5641743.2839816.2051746.0239836.8451741.6199898.1191703.967
9979.1761636.7329999.3511626.52410009.421615.91910019.491615.87810029.551621.292
10049.691643.48610089.96 1675.5410110.091680.88610140.291703.40510190.631729.795
 10200.71730.41110220.83 1748.7410240.961760.25710291.471782.94910301.581780.826
10321.821792.89710362.281802.37510422.981827.78210473.571854.93610500.981862.763
#Mann= 3 , 0 , 0
9499.051    0.12       09499.051    0.12       010500.98    0.12       0
#XS Ineff= 2 , 0
       0                               0
Bank Sta=9499.051,10500.98
Exp/Cntr=0.3,0.1

Type RM Length L Ch R = 1 ,114867.2,97.031100,97.031100,97.031100
XS GIS Cut Line= 6
607437.821503554799167.216773155607322.801014934799416.644805955
607281.287523452799529.355658639607267.411836879799592.403916006
607233.070729193799821.984342208607173.332544056800126.529643181
#Sta/Elev= 30
9499.0611792.8239518.6441796.913 9601.321759.4779639.7771765.8229661.8011751.667
9716.861 1726.869815.0651704.2659849.033 1701.569899.6981675.7749950.8951640.863
9971.1991621.939 10001.51612.27510031.76 1617.1310082.191653.06810112.591658.311
10122.731669.15110173.421673.92510193.711679.25110214.091692.32810232.571692.125
10254.861702.94610285.431708.259   103161724.21810336.471725.51410387.331751.969
10417.911757.80210438.29 1771.7210448.481773.46610468.86 1789.3110500.99    1801
#Mann= 3 , 0 , 0
9499.061    0.12       09499.061    0.12       010500.99    0.12       0
#XS Ineff= 2 , 0
       0                               0
Bank Sta=9499.061,10500.99
Exp/Cntr=0.3,0.1

Type RM Length L Ch R = 1 ,114770.1,97.031000,97.031000,97.031000
XS GIS Cut Line= 6
607394.425757941799171.831512466607310.976891544799332.127153369
 607214.88172019799498.425439999607185.901862137799559.734801146
607087.212787497799874.022313139607026.762003431800097.854325987
#Sta/Elev= 30
9499.0371782.7359513.7861778.4789588.2351741.6619626.2871744.5699637.6351740.636
9660.331 1725.039706.1851706.2799729.2841690.5389763.9321681.9669798.581  1683.7
9811.6361677.6059844.7791669.3389879.2231656.7189890.4611652.0619955.8211608.554
9966.3961606.8489987.5451609.314 10008.61601.61610029.521609.92710072.461646.403
10092.29 1660.7510165.531699.03110186.451709.06510217.841719.90410238.761730.286
10259.681744.31110290.92  1756.710332.491780.13810350.821794.09410500.991870.179
#Mann= 3 , 0 , 0
9499.037    0.12       09499.037    0.12       010500.99    0.12       0
#XS Ineff= 2 , 0
       0                               0
Bank Sta=9499.037,10500.99
Exp/Cntr=0.3,0.1

Type RM Length L Ch R = 1 ,114673.1,97.031000,97.031000,97.031000
XS GIS Cut Line= 6
607369.272665285799168.075385189  607248.4632622799375.468824736
607095.275566348799552.732362568607004.091611522 799690.55189424
606934.848213147799830.273159654606867.065907616800024.497001369
#Sta/Elev= 30
 9499.071772.1669506.9591772.4249518.3531768.4179575.3211736.5139643.9191725.326
9679.4451703.0139708.3361689.2159727.0061674.8739750.9621660.5229763.293 1659.88
9788.2731664.0449813.8961653.094 9853.391641.024 9894.611636.6929908.6011631.358
9949.9771604.555 9976.621595.8379991.6331596.51510009.361592.12810025.131597.396
10037.16 1604.5410061.211611.54710108.951649.77110223.621705.109   103431777.989
10385.791788.60710438.431811.71210469.95 1820.5210480.461826.62410500.941833.189
#Mann= 3 , 0 , 0
 9499.07    0.12       0 9499.07    0.12       010500.94    0.12       0
#XS Ineff= 2 , 0
       0                               0
Bank Sta=9499.07,10500.94
Exp/Cntr=0.3,0.1

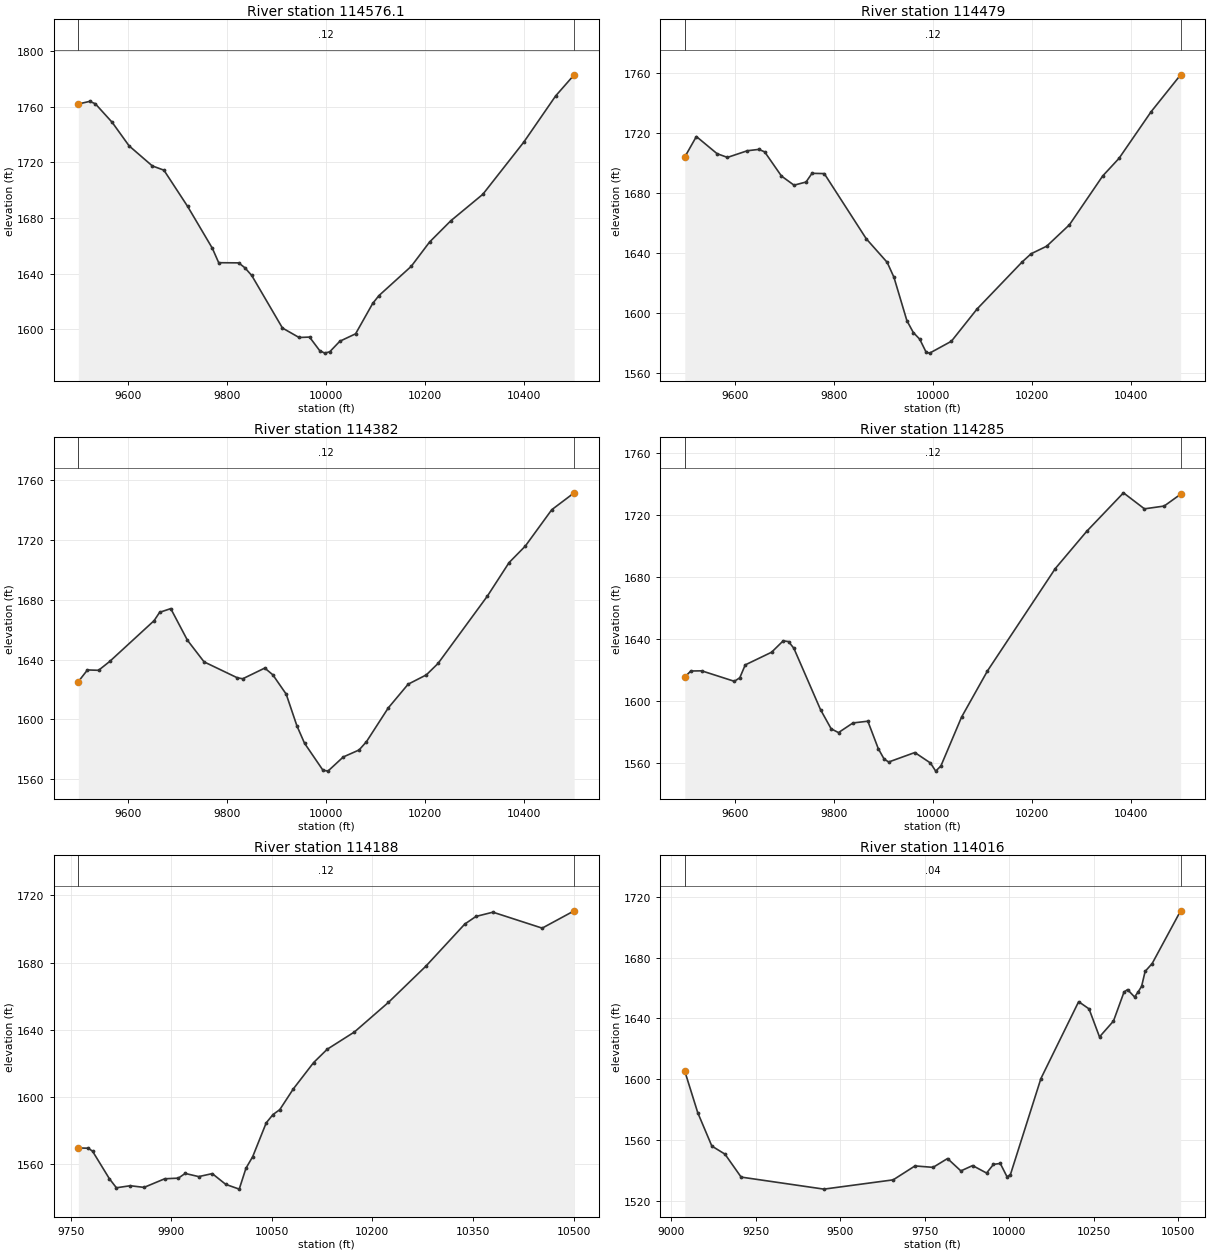
Type RM Length L Ch R = 1 ,114576.1,97.031100,97.031100,97.031100
XS GIS Cut Line= 6
 607360.99459039 799144.95603949607167.419997422799431.383048157
 607095.67633164799480.786248436606963.226102996799519.725964088
606890.686613345799583.004819452606746.522987348799880.133732374
#Sta/Elev= 30
9499.1741761.8299522.002 1763.719533.3911762.0449567.5581748.6659601.7241731.784
9648.6091717.3889672.077 1714.329720.0691688.2519769.9731658.2229782.7451647.901
9823.1451647.7779835.7061644.2369849.4941638.7199911.5741601.0019945.0971594.204
9966.2671594.5049986.6581584.8439996.8531582.97610007.081583.93910027.561591.532
10059.31 1596.8410093.85 1618.64 10106.41624.25410171.681645.26910208.781662.738
 10251.81678.036 10316.41697.01710399.331734.56210463.43 1767.6110500.881782.776
#Mann= 3 , 0 , 0
9499.174    0.12       09499.174    0.12       010500.88    0.12       0
#XS Ineff= 2 , 0
       0                               0
Bank Sta=9499.174,10500.88
Exp/Cntr=0.3,0.1

Type RM Length L Ch R = 1 ,  114479,97.031000,97.031000,97.031000
XS GIS Cut Line= 6
607306.167675043799014.599177217607131.113177552799291.251268741
606929.703984624799469.580409692606873.870145694799534.750959025
606805.068896084799652.672901322606735.718409423799820.656345039
#Sta/Elev= 30
9499.0631704.1369522.4451717.7969564.3191706.3269585.2561703.8479625.4861708.296
9648.806  1709.29660.4661707.5269694.3651691.3899719.7341685.2929743.9781687.384
  9756.11693.2059780.8641693.0329865.6631649.5069907.9551633.7479921.6671623.757
9947.8121594.7829960.786 1586.859973.7611582.3929986.7351573.6549993.8161573.081
10037.731581.01610089.631602.58910180.621633.97310198.891639.48810230.261644.518
10276.261658.84410343.561691.49710376.421703.21610441.241734.357 10500.91759.013
#Mann= 3 , 0 , 0
9499.063    0.12       09499.063    0.12       0 10500.9    0.12       0
#XS Ineff= 2 , 0
       0                               0
Bank Sta=9499.063,10500.9
Exp/Cntr=0.3,0.1

Type RM Length L Ch R = 1 ,  114382,97.031100,97.031100,97.031100
XS GIS Cut Line= 6
607140.887884788798898.592289626 606969.30143157799239.329363336
606940.932177585799309.305684816606905.574876377 799427.81883261
606802.835630065799617.645531138606725.038591562  799807.3047954
#Sta/Elev= 30
9499.0481625.3029517.4611633.1089539.9061632.868 9562.351638.7679652.1271666.064
9663.3491671.6469685.7931674.121 9719.461652.9949753.126 1638.519820.1771627.875
9831.2921627.2169875.751 1634.369892.0121629.8659919.0541616.9279940.6351595.798
9956.0711584.1099993.1581566.12610003.391565.44510034.371574.91610066.281579.584
10081.211585.12510125.161607.65410165.411623.56410202.261629.822 10225.81637.428
10325.721682.56710369.421704.90810402.141715.92110455.641740.256 10500.91751.551
#Mann= 3 , 0 , 0
9499.048    0.12       09499.048    0.12       0 10500.9    0.12       0
#XS Ineff= 2 , 0
       09946.999                       0
Bank Sta=9499.048,10500.9
Exp/Cntr=0.3,0.1

Type RM Length L Ch R = 1 ,  114285,97.031000,97.031000,97.031000
XS GIS Cut Line= 6
607017.845850161798883.895306437 606939.90616413799054.561416828
606894.283910466799168.756063153606831.035707533799357.801921688
606783.952896682799511.148692282606673.955718935799823.963660637
#Sta/Elev= 30
9499.0381615.6199511.2461619.4459533.2331619.5529599.194 1612.819610.1871615.106
9621.1811623.3759674.3971631.526  9697.91638.8649708.6681638.3729719.4371634.067
 9773.281594.6049794.8171582.241 9809.631579.8129838.8641586.0259868.9441587.147
9890.036 1569.479901.8411562.7749911.1281560.8999963.8581566.9859995.4951560.241
10006.031555.01910016.511558.31710058.351589.81110110.651619.50310247.671685.345
10311.271709.34910385.471734.09110427.88 1723.7910467.691725.57810500.981733.185
#Mann= 3 , 0 , 0
9499.038    0.12       09499.038    0.12       010500.98    0.12       0
#XS Ineff= 2 , 0
       09940.583                       0
Bank Sta=9499.038,10500.98
Exp/Cntr=0.3,0.1

Type RM Length L Ch R = 1 ,  114188,171.951700,171.951700,171.951700
XS GIS Cut Line= 6
606801.341869899799070.761123777606783.355746726799129.027422777
 606761.53068213799228.138478733606734.632404953799438.694205863
606718.958085339799526.732541024606640.844415266799790.470214338
#Sta/Elev= 30
9761.5671569.6819776.5031569.5229782.7871567.7279807.8791551.3649818.337 1545.97
    98391547.1949859.5981546.2059890.3511551.3289910.7041551.708 9920.881554.502
9941.0971552.6259961.2891554.4019981.4131548.00310001.491545.16810011.541557.614
10021.581564.49110041.771584.63310051.871589.56610061.961592.48310082.161604.829
10112.461620.51210132.661628.41910173.271638.71210224.05 1656.3510279.971677.949
10337.881702.96510354.581707.49810379.831710.02110453.251700.52710500.941710.827
#Mann= 3 , 0 , 0
9761.567    0.12       09761.567    0.12       010500.94    0.12       0
#XS Ineff= 2 , 0
       09968.945                       0
Bank Sta=9761.567,10500.94
Exp/Cntr=0.3,0.1

Type RM Length L Ch R = 1 ,  114016,119.141400,119.141400,119.141400
XS GIS Cut Line= 6
 606996.25119257798482.116942301606709.832113594 798958.42867431
606616.071090966799198.677690759606588.645624638 799302.28976661
 606569.42979455799519.949696228606483.400061786799835.878888905
#Sta/Elev= 30
9039.6851605.1939078.0551577.8619119.7331555.8899158.5421550.5759206.4111535.447
9451.4551527.5189656.4231533.6239721.0591542.8019774.5571541.8619817.3541547.669
 9856.831539.5189891.6051543.0379932.9481538.1159953.3341543.8289973.5041544.432
9993.5421535.61610003.541537.11510093.761600.37210205.441651.00110236.181646.259
10267.191627.79710308.531638.24110339.751657.34810350.161658.95510370.991654.095
 10381.41657.36210391.821661.11510402.231670.95510423.06 1676.1310507.291710.842
#Mann= 3 , 0 , 0
9039.685    0.04       09039.685    0.04       010507.29    0.04       0
#XS Ineff= 2 , 0
       09964.885                       0
Bank Sta=9039.685,10507.29
Exp/Cntr=0.3,0.1

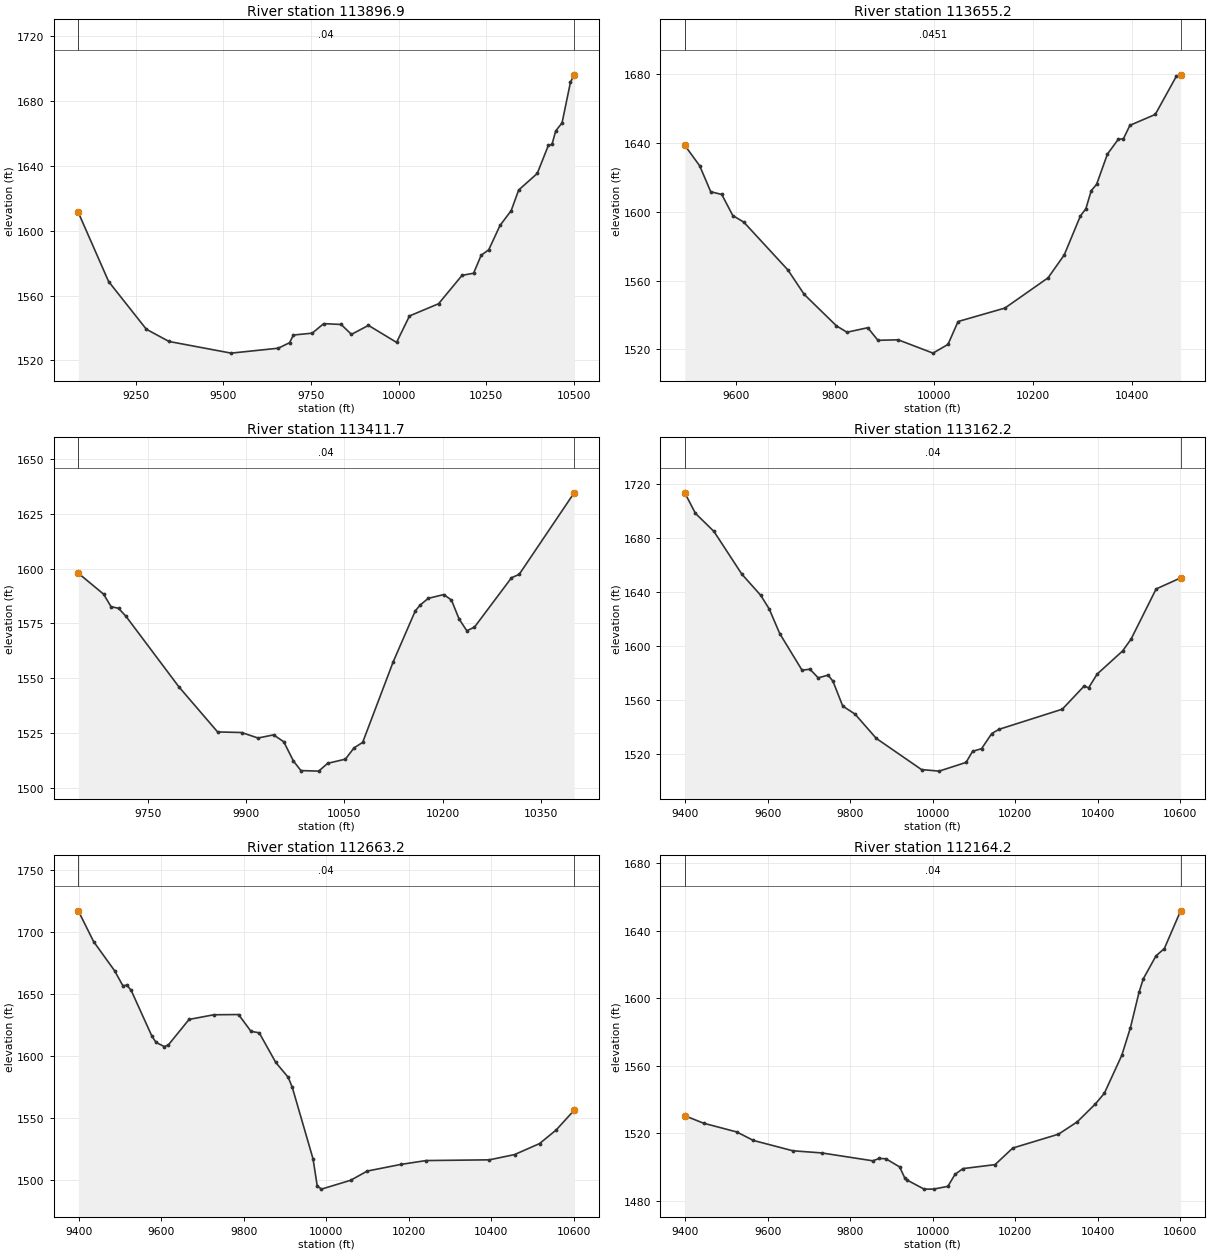
Type RM Length L Ch R = 1 ,113896.9,241.704100,241.704100,241.704100
XS GIS Cut Line= 6
606855.310536027798484.589585394 606587.80001989799154.764387801
606539.557862759799236.700548843606446.459316492799351.632208243
606395.367604911 799439.82472983606274.286753327799765.070484877
#Sta/Elev= 30
9086.6191611.3179173.0911568.674 9280.631539.2539345.1531531.7049522.4591524.501
9657.0151527.5419689.2771530.9539700.0311535.668  9753.81536.8349786.5821542.706
9836.3061542.1869865.6721536.0869914.2151541.6299994.4181531.12810031.221547.454
10114.221554.98910181.211572.51710214.061573.82210235.711584.93910257.211588.275
10289.461603.29710321.391612.50610342.641625.18810395.691635.41910427.251652.672
10437.77 1653.4110448.281661.62210466.391666.63410490.361691.66510500.951696.296
#Mann= 3 , 0 , 0
9086.619    0.04       09086.619    0.04       010500.95    0.04       0
#XS Ineff= 2 , 0
       09951.067                       0
Bank Sta=9086.619,10500.95
Exp/Cntr=0.3,0.1

Type RM Length L Ch R = 1 ,113655.2,243.451100,243.451100,243.451100
XS GIS Cut Line= 6
 606502.48020775798718.026664081 606366.72645695799008.026707512
606343.164336532 799088.69726117606326.022584433799221.871809271
606312.285052129799278.337736935606159.703329964799653.294641286
#Sta/Elev= 30
9496.4591638.6419526.545 1626.759548.8531611.6579571.1611610.0719593.4691597.791
9615.7761593.9619704.8951566.1329737.7761551.9439802.8031533.6759824.1581529.943
9866.1351532.5649886.7721525.237 9927.591525.5439998.0391517.788 10028.31522.867
10048.621536.16810143.291543.99610230.46 1561.5710263.191574.90610295.921597.632
10306.831601.71810317.741612.25810328.651615.98910350.481633.57410372.191642.073
10382.911642.54410395.871650.27710447.151656.61310489.571678.73810498.371679.652
#Mann= 3 , 0 , 0
9496.459  0.0451       09496.459  0.0451       010498.37  0.0451       0
#XS Ineff= 2 , 0
       0                               0
Bank Sta=9496.459,10498.37
Exp/Cntr=0.3,0.1

Type RM Length L Ch R = 1 ,113411.7,249.508400,249.508400,249.508400
XS GIS Cut Line= 6
606313.453769909798801.428981339606190.760230161799007.723360276
606057.541851685 799162.47406584605998.715070411799242.199604734
605942.021714151799340.423583842605901.578288631799432.742750748
#Sta/Elev= 30
9643.2771597.8789681.8051588.3599693.2811582.6319704.7581581.8949716.2351578.185
9796.962 1546.099856.1341525.5239892.7931525.2539917.9471522.7489941.6881524.179
9957.2591521.0489972.0791512.2569983.4561507.90510010.681507.65110024.351511.204
10051.481513.10910064.68 1518.2410077.881520.759 10124.51557.45210158.331580.727
 10165.91583.40810178.091586.40310201.881588.15310213.611585.62210225.351576.956
10237.08 1571.63 10248.81573.30210305.361595.81410317.081597.33810401.141634.525
#Mann= 3 , 0 , 0
9643.277    0.04       09643.277    0.04       010401.14    0.04       0
#XS Ineff= 2 , 0
       0                               0
Bank Sta=9643.277,10401.14
Exp/Cntr=0.3,0.1

Type RM Length L Ch R = 1 ,113162.2,499.016700,499.016700,499.016700
XS GIS Cut Line= 6
606260.673781497  798422.1048608606070.815035063798757.143855387
605871.954463078798997.101173364605800.708766633799105.409852094
 605736.17267706799266.407827046605700.681536382799463.879382301
#Sta/Elev= 30
9399.0411713.7769424.7921698.5529469.7821685.078 9537.511653.3059583.056 1637.69
9603.7571627.4739629.1341609.2729683.2861582.0489702.3371582.8179722.4951576.355
9746.2321578.413  9758.11573.9239781.8361555.4379811.8351549.405 9863.061531.452
9972.8191508.256 10015.51507.10510080.821513.59210096.541521.79510118.451523.796
10142.941534.97810160.591538.138 10314.11553.10610367.311570.38210377.751568.929
10398.611579.19610460.16 1596.3310480.671605.09310541.491642.38810600.881650.604
#Mann= 3 , 0 , 0
9399.041    0.04       09399.041    0.04       010600.88    0.04       0
#XS Ineff= 2 , 0
       0                               0
Bank Sta=9399.041,10600.88
Exp/Cntr=0.3,0.1

Type RM Length L Ch R = 1 ,112663.2,499.016800,499.016800,499.016800
XS GIS Cut Line= 6
605497.579090348798128.439493485 605468.94314592798376.953374714
605474.505667486798611.544474478605504.342456851 798841.93324015
605568.325954112799156.279396393605590.181034287799318.314807053
#Sta/Elev= 30
9399.081 1717.089436.1381692.298 9486.791668.9289506.9461656.8159517.0241657.116
9527.1031653.0719577.2671616.2619587.2961611.1749607.3541607.7489617.3831609.124
9667.4771629.6199727.4791633.3749787.519 1633.55 9817.561620.0439837.5881618.842
9877.6441594.9919907.7651583.0319917.8131574.8089968.0531517.2889978.162 1495.55
9988.3071492.95410059.171500.08810099.531507.50710180.761512.85810242.111515.958
10395.43 1516.5510456.381520.75610517.091529.63710557.36 1540.5910600.97  1556.5
#Mann= 3 , 0 , 0
9399.081    0.04       09399.081    0.04       010600.97    0.04       0
#XS Ineff= 2 , 0
       0                               0
Bank Sta=9399.081,10600.97
Exp/Cntr=0.3,0.1

Type RM Length L Ch R = 1 ,112164.2,499.016700,499.016700,499.016700
XS GIS Cut Line= 6
604883.851304348798589.493187717604890.539269091798749.665283001
604940.980395157798878.684799073605334.898414932799218.929551686
 605421.92263405799367.063087723605474.984303798799563.725459348
#Sta/Elev= 30
9399.0651530.5069444.6411526.052 9524.881520.8869565.4591515.8359660.8871509.725
9730.8811508.4529854.7531503.7829870.5541505.1929886.5971504.9819919.7531500.171
9931.8981493.8169938.8151492.2469979.0041487.02310001.961487.004 10036.7 1488.65
10054.211495.79710073.311499.163 10151.11501.52110194.111511.35810304.84 1519.55
10350.341526.863 10394.51537.53310415.941543.758 10458.31566.28710479.281582.677
10499.961603.528 10510.3 1611.5710541.061625.15210561.431629.54310600.891651.878
#Mann= 3 , 0 , 0
9399.065    0.04       09399.065    0.04       010600.89    0.04       0
#XS Ineff= 2 , 0
       0                               0
Bank Sta=9399.065,10600.89
Exp/Cntr=0.3,0.1

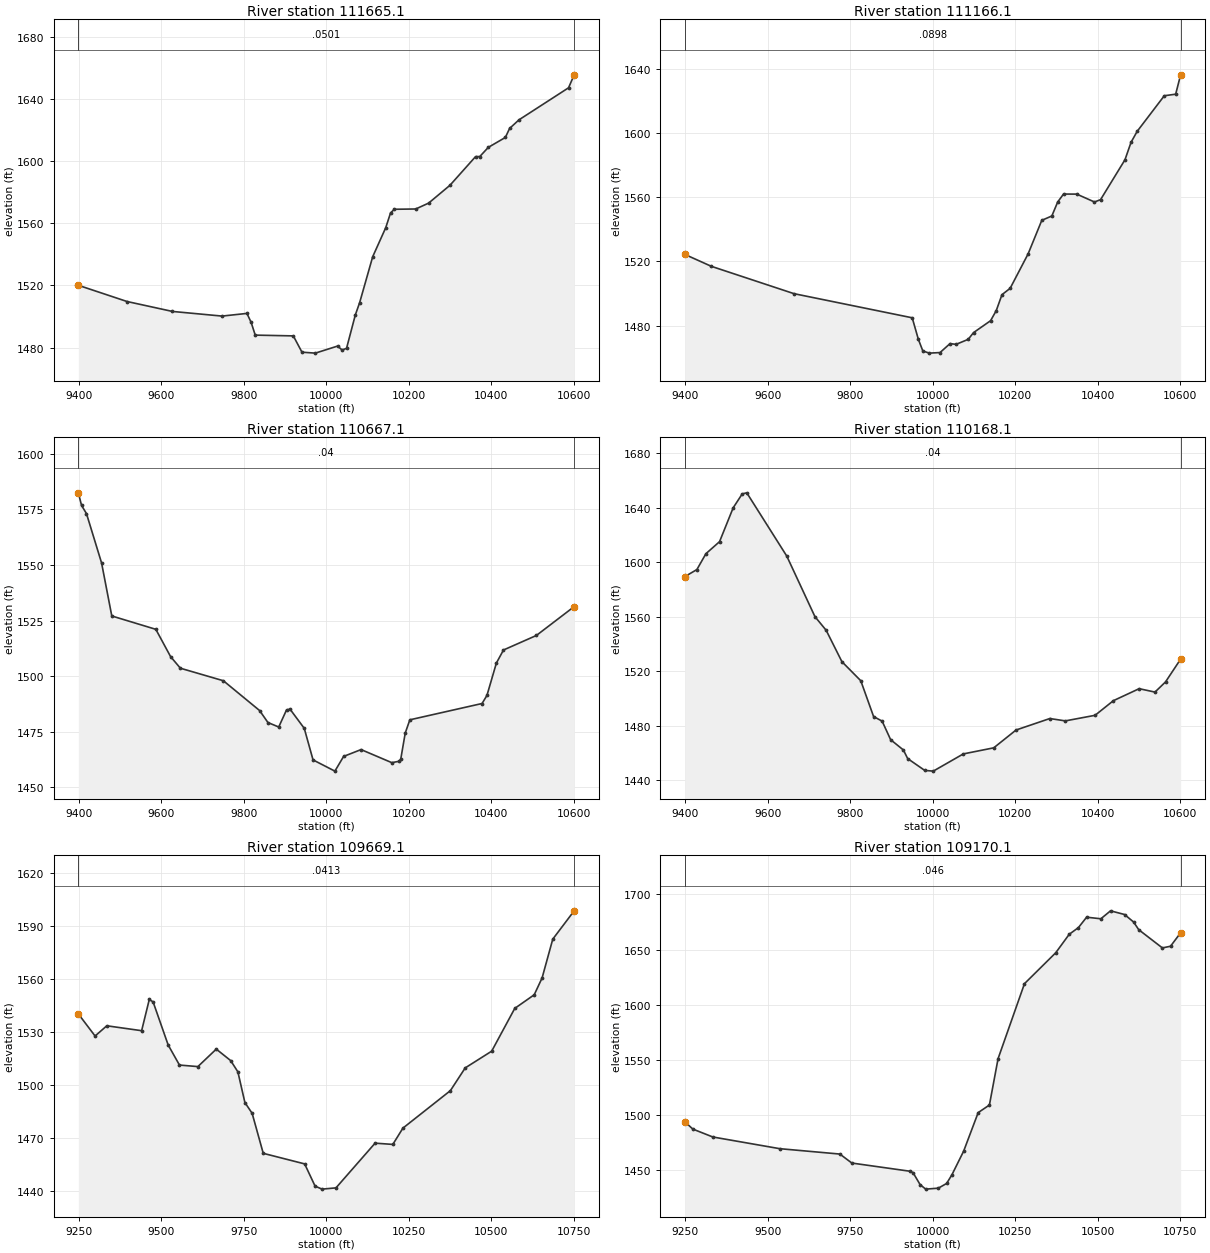
Type RM Length L Ch R = 1 ,111665.1,499.016700,499.016700,499.016700
XS GIS Cut Line= 6
604832.786081636798687.999585298604818.176816167798799.471569935
 604802.61946612799061.201855167604788.277947531799158.232707227
604695.571025218799424.098082582604581.614893203 799856.51474859
#Sta/Elev= 30
9399.0771520.0999517.0651509.6659627.2591503.2649747.4711500.2769807.7721501.996
9817.8481496.3059827.9241488.0229920.2151487.5219941.182 1477.039973.5671476.426
10027.611480.97610038.421478.42610049.231479.51510070.471500.969   100811508.939
 10112.61538.47610144.191557.153 10155.91566.69310165.091569.04510216.981569.231
10248.121572.99910299.911584.48310361.881602.919 10372.21602.99210392.861608.901
10434.171615.28110444.491621.09110467.28 1626.6410587.411647.25910600.971655.604
#Mann= 3 , 0 , 0
9399.077  0.0501       09399.077  0.0501       010600.97  0.0501       0
#XS Ineff= 2 , 0
       0                               0
Bank Sta=9399.077,10600.97
Exp/Cntr=0.3,0.1

Type RM Length L Ch R = 1 ,111166.1,499.016800,499.016800,499.016800
XS GIS Cut Line= 6
604787.809519917798601.799464265604723.527957364798700.088751853
604665.644749721 798759.72452994604375.248720497798953.876771223
604073.662225754799258.905555508603927.278378433799425.309432168
#Sta/Elev= 30
9399.0821524.3219463.6151516.8789663.8741499.8699950.3351484.8559965.2991471.395
9976.126 1464.199991.8371462.86210017.791463.21710042.041468.79410056.64 1468.32
10086.061471.43510098.941475.62410140.311483.046 10154.1 1489.3610167.89 1499.24
10187.721503.20310231.281524.64110264.431545.522 10288.81548.23510302.961556.923
10317.12 1561.8810349.131561.84410392.09 1556.9510406.871558.38310466.031583.205
10480.811594.10310495.631600.91310561.381623.07110588.95 1624.0410600.961636.093
#Mann= 3 , 0 , 0
9399.082  0.0898       09399.082  0.0898       010600.96  0.0898       0
#XS Ineff= 2 , 0
       0                               0
Bank Sta=9399.082,10600.96
Exp/Cntr=0.3,0.1

Type RM Length L Ch R = 1 ,110667.1,499.016700,499.016700,499.016700
XS GIS Cut Line= 6
604758.337232723 798178.46577061604645.564750572798321.319637786
604543.887317893798405.802404347604410.849657232798477.906807058
604053.531794558798616.217055554603771.640838178798825.698706207
#Sta/Elev= 30
9399.1061582.4029406.9191576.7369418.8751573.049 9455.441550.8969480.2051527.061
9586.9391521.0559622.7391508.7859646.4581503.5779750.6811497.9439838.4621484.556
9858.648 1479.179884.8311477.1539903.7841484.8479912.3581485.1439946.7171476.554
9968.0131462.36910020.961457.32610042.111463.93510084.421467.01110158.881461.134
10176.631461.75410180.541462.63810191.491474.45910202.631480.38610377.691487.719
10389.531491.361 10412.41505.90610429.631511.76710509.29 1518.2910600.911531.259
#Mann= 3 , 0 , 0
9399.106    0.04       09399.106    0.04       010600.91    0.04       0
#XS Ineff= 2 , 0
       0                               0
Bank Sta=9399.106,10600.91
Exp/Cntr=0.3,0.1

Type RM Length L Ch R = 1 ,110168.1,499.016800,499.016800,499.016800
XS GIS Cut Line= 6
604106.888023996 797708.38283809603984.613110845797998.933217917
603882.966306863798358.165042919 603841.45272947798468.484477376
603762.554407279798605.224398607603618.771466665798793.689002198
#Sta/Elev= 30
9399.0471589.309 9428.321594.4879450.3161606.1669483.3091614.9929516.3021639.826
9538.2981650.0649549.2961650.8259646.2811604.3649714.4421559.9799741.7641549.899
9779.8921526.8769825.6181512.8929856.708 1486.589877.3551483.2469898.0031469.618
9928.9751462.0449939.2991455.7499980.6071447.07810001.371446.54210074.181459.179
10147.931463.64410202.031476.72510283.851485.14210321.531483.42410393.551487.516
10437.891498.24910500.431507.05810538.741504.56410564.281512.01310600.921528.745
#Mann= 3 , 0 , 0
9399.047    0.04       09399.047    0.04       010600.92    0.04       0
#XS Ineff= 2 , 0
       0                               0
Bank Sta=9399.047,10600.92
Exp/Cntr=0.3,0.1

Type RM Length L Ch R = 1 ,109669.1,499.016800,499.016800,499.016800
XS GIS Cut Line= 6
603755.938240396 797442.17207192603634.892558952797638.786139397
 603548.48973949797807.011441159603316.970961417798416.269373279
603229.685654238 798580.42404093603099.703747203798786.457683385
#Sta/Elev= 30
9249.0431540.4199299.7711527.9119335.3041533.6949440.7831530.9179463.9771548.581
9475.5741547.1839521.2121522.8179555.3821511.4859611.182 1510.619666.8831520.502
9710.5241514.0089732.3211507.6499753.5951490.2859775.5041484.2049809.1821461.559
9934.5841455.5849966.2281442.9979987.3241441.31510029.471442.02710147.95 1467.31
10201.681466.60610232.261475.81910376.041497.00910420.921509.87210501.111519.334
10571.071543.53310629.971551.22810653.821560.73710686.181582.69810750.961598.709
#Mann= 3 , 0 , 0
9249.043  0.0413       09249.043  0.0413       010750.96  0.0413       0
#XS Ineff= 2 , 0
       09785.821                       0
Bank Sta=9249.043,10750.96
Exp/Cntr=0.3,0.1

Type RM Length L Ch R = 1 ,109170.1,249.508300,249.508300,249.508300
XS GIS Cut Line= 6
603541.086074613797351.427599257603360.606502821797552.195833666
603197.859381512797717.721493084602768.434381723 798080.48941959
602594.758932984798245.253947744 602456.36229857798386.925549295
#Sta/Elev= 30
9249.0461494.0579273.3341487.3749333.8951480.2119536.7141469.609 9718.821464.732
9755.0161456.5919929.8891449.2179940.2471447.9699961.8531437.0379978.7061432.961
   100171433.82610042.111438.08910058.131445.92110093.791467.41910137.75 1502.29
10171.771509.16210198.02 1551.1810277.961619.11410372.691647.13910413.571663.875
10441.341669.903 10466.21679.34510509.381677.91610538.68 1685.1210581.191681.786
10608.481674.97710624.121668.01310695.681651.52410720.321653.01810750.971665.206
#Mann= 3 , 0 , 0
9249.046   0.046       09249.046   0.046       010750.97   0.046       0
#XS Ineff= 2 , 0
       09820.718                       0
Bank Sta=9249.046,10750.97
Exp/Cntr=0.3,0.1