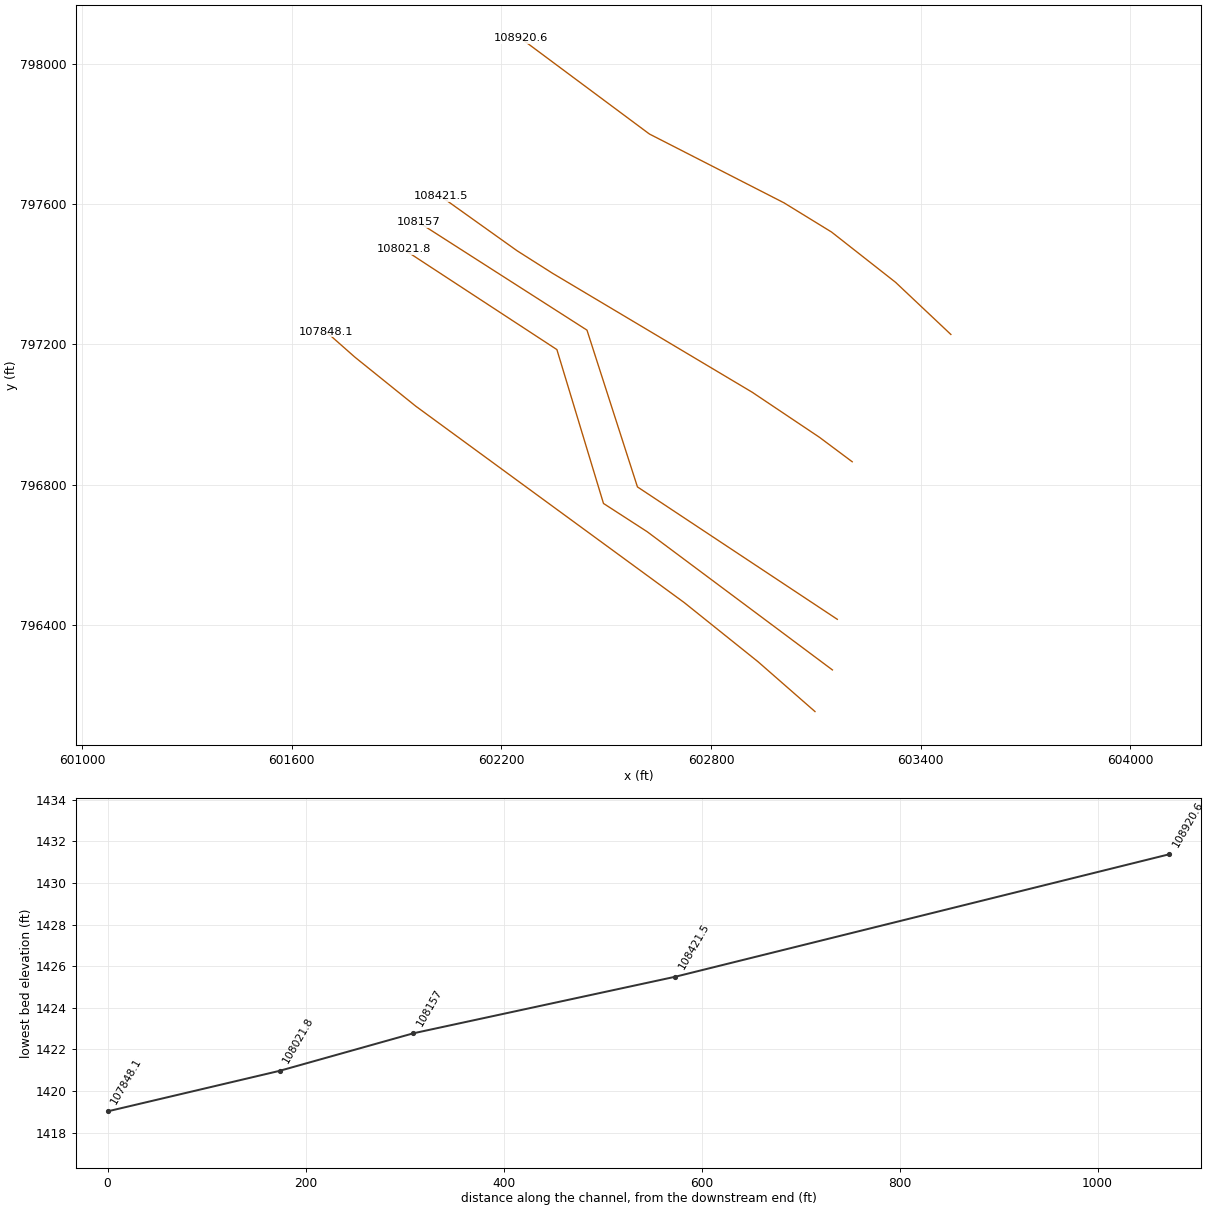
HEC-RAS study 10395_ras.prj: 10395

--- 10395_ras.g01 (geometry) --- (continued)

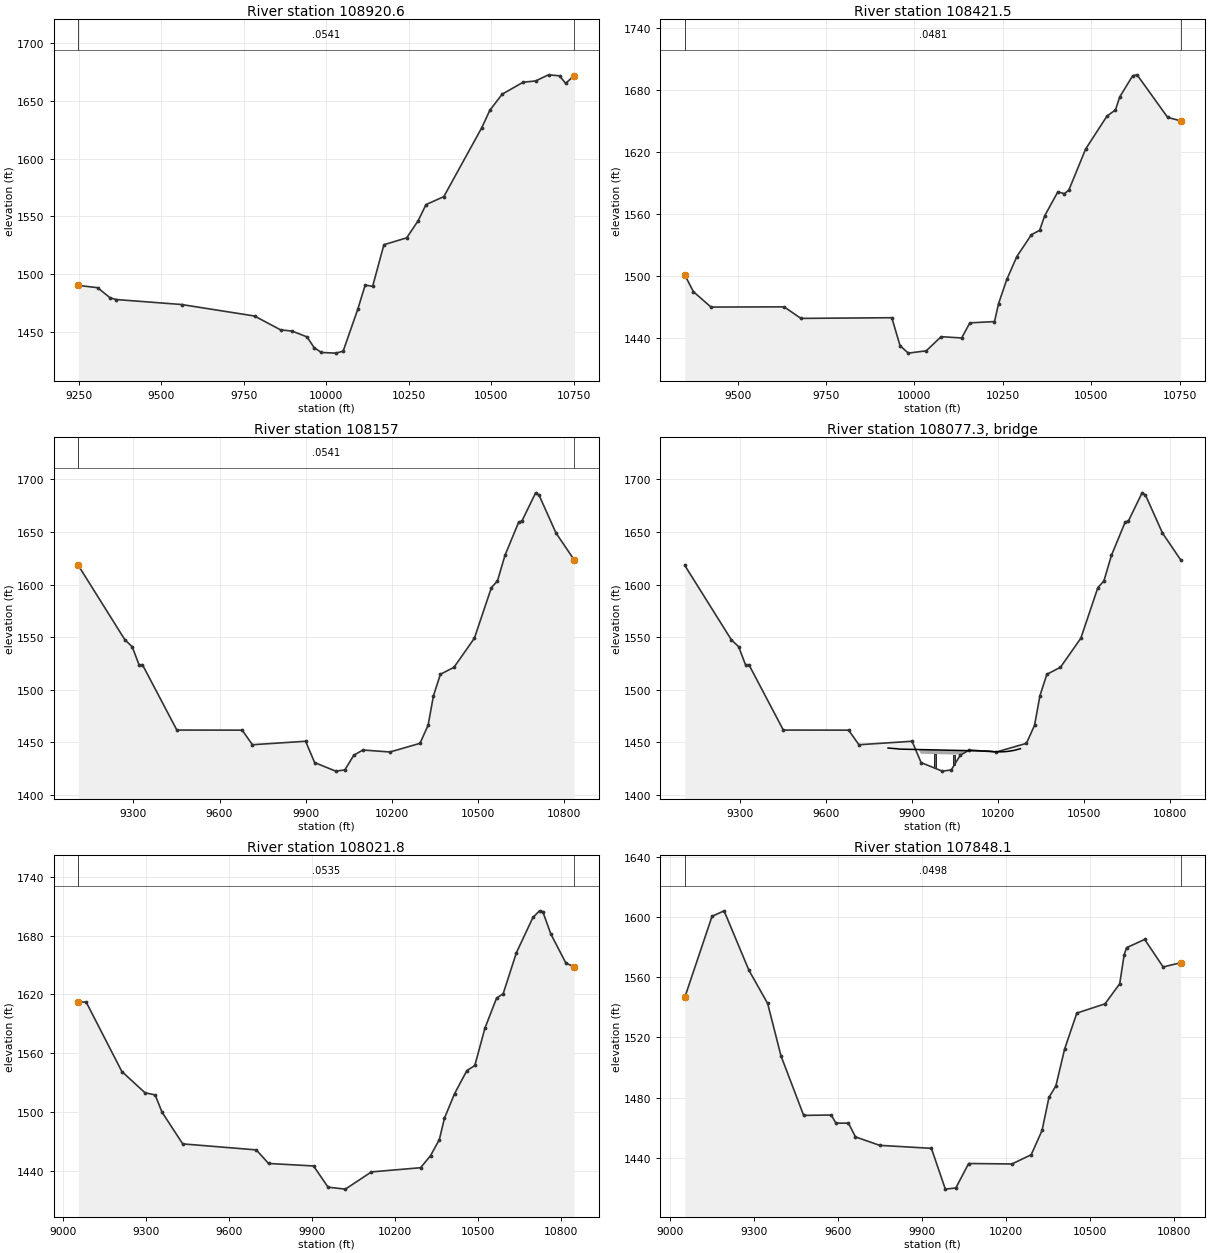
Type RM Length L Ch R = 1 ,108920.6,499.016800,499.016800,499.016800
XS GIS Cut Line= 6
603486.868127127797228.241709697603328.456608697797377.055265843
603145.292568522797520.391297015 603008.88498479797603.870303101
602623.710267748797800.120187697602255.171156885798073.269623843
#Sta/Elev= 30
9249.0681490.1079307.2891488.1579345.1391479.4339362.9121477.896 9561.62 1473.56
9782.7211463.5799861.6051451.5969897.0861450.4639941.7361445.4589963.6421436.047
9985.5471431.93710029.291431.38410051.171433.095 10095.61469.50610117.871490.361
10140.581489.36710174.65 1525.4110243.771531.40210278.651546.35310302.151560.221
10356.071567.11110471.121626.93610495.591642.02510532.881656.001 10596.21666.342
10634.271667.49510673.241672.78110706.661671.925 10725.21665.36610750.951672.173
#Mann= 3 , 0 , 0
9249.068  0.0541       09249.068  0.0541       010750.95  0.0541       0
#XS Ineff= 2 , 0
       09877.147                       0
Bank Sta=9249.068,10750.95
Exp/Cntr=0.3,0.1

Type RM Length L Ch R = 1 ,108421.5,264.575500,264.575500,264.575500
XS GIS Cut Line= 6
603204.386227949796865.100819967603110.275154315796935.078584783
602917.949418042797063.462222416602346.458072011797402.746057567
602244.971356632797466.990403431602026.136576882797622.535778609
#Sta/Elev= 30
9350.7031501.2439374.9921485.001 9424.771470.102 9631.461470.309 9678.991459.133
9936.0121459.7859959.2691432.7589982.5271425.49510033.391427.74910075.421441.423
10133.451440.18610156.661454.779 10226.31456.064 10237.91473.53310261.111496.844
10289.51 1519.0410330.751540.21110353.961544.39110368.091558.41810405.481581.716
10424.181579.84610436.611583.48910483.991623.10810544.211654.96210568.321661.032
10580.371673.588 10617.21694.20610629.511694.98310715.941653.74110752.55 1650.47
#Mann= 3 , 0 , 0
9350.703  0.0481       09350.703  0.0481       010752.55  0.0481       0
#XS Ineff= 2 , 0
       0 9920.33                       0
Bank Sta=9350.703,10752.55
Exp/Cntr=0.3,0.1

Type RM Length L Ch R = 1 ,  108157,135.213800,135.213800,135.213800
XS GIS Cut Line= 4
603161.708529383796415.563410372602589.486307114796793.341188177
602445.041862667797240.563410386601961.708529383 797548.89674373
#Sta/Elev= 30
9107.7451618.2939270.0751547.6269295.5251541.047 9319.491523.8269331.4731523.862
  9451.31461.8059678.9721461.729 9714.921447.8649900.2531451.1679931.7791430.893
10005.341422.77610036.871423.88910068.391437.90310099.92 1442.8510194.49 1440.98
10299.031449.18410327.421466.37710346.021494.352 10370.21514.83210417.641521.463
10488.811549.13410548.121597.21110569.141603.49710595.571627.96410643.011659.273
10654.871660.69610702.321687.31110714.181685.17510773.491649.065 10836.71623.651
#Mann= 3 , 0 , 0
9107.745  0.0541       09107.745  0.0541       0 10836.7  0.0541       0
#XS Ineff= 2 , 0
       09898.555                       0
Bank Sta=9107.745,10836.7
Exp/Cntr=0.3,0.1

Type RM Length L Ch R = 3 ,108077.3,,,
BEGIN DESCRIPTION:
END DESCRIPTION:
Bridge Culvert--1,0,-1,-1, 0
Deck Dist Width WeirC Skew NumUp NumDn MinLoCord MaxHiCord MaxSubmerge Is_Ogee
48.578050,38.057700,2.6,0, 35, 35, , , 0.95, 0, 0,0,,
 9816.61 9822.21 9824.45 9827.11 9836.02 9846.42 9848.50 9849.74 9849.74 9856.82
 9867.22 9870.9210110.9010110.9010135.2710137.6210139.7110148.0210158.4210168.82
10176.1110179.2210189.6210200.0210210.4210211.7210212.4910220.8410231.2510241.67
10248.2110252.0910262.5010272.9210278.15
 1444.75 1444.56 1444.52 1444.49 1444.25 1444.07 1443.99 1443.94 1443.94 1443.68
 1443.65 1443.61 1442.15 1442.15 1442.00 1442.00 1441.95 1441.80 1441.92 1441.76
 1441.57 1441.49 1441.21 1441.15 1441.10 1441.12 1441.13 1441.21 1441.46 1441.84
 1442.13 1442.27 1442.93 1443.75 1444.09
  444.75  444.56  444.52  444.49  444.25  444.07  443.99  443.94 1439.94 1439.68
 1439.65 1439.61 1438.15  442.15  442.00  442.00  441.95  441.80  441.92  441.76
  441.57  441.49  441.21  441.15  441.10  441.12  441.13  441.21  441.46  441.84
  442.13  442.27  442.93  443.75  444.09
 9816.61 9822.21 9824.45 9827.11 9836.02 9846.42 9848.50 9856.82 9867.22 9870.92
 9892.45 9892.4510135.2710137.6210139.7110148.0210153.6010153.6010158.4210168.82
10176.1110179.2210189.6210200.0210210.4210211.7210212.4910220.8410231.2510241.67
10248.2110252.0910262.5010272.9210278.15
 1444.75 1444.56 1444.52 1444.49 1444.25 1444.07 1443.99 1443.68 1443.65 1443.61
 1443.48 1443.48 1442.00 1442.00 1441.95 1441.80 1441.87 1441.87 1441.92 1441.76
 1441.57 1441.49 1441.21 1441.15 1441.10 1441.12 1441.13 1441.21 1441.46 1441.84
 1442.13 1442.27 1442.93 1443.75 1444.09
  444.75  444.56  444.52  444.49  444.25  444.07  443.99  443.68  443.65  443.61
  443.48 1439.48 1438.00 1438.00 1437.95 1437.80 1437.87  441.87  441.92  441.76
  441.57  441.49  441.21  441.15  441.10  441.12  441.13  441.21  441.46  441.84
  442.13  442.27  442.93  443.75  444.09
Pier Skew, UpSta & Num, DnSta & Num=  ,9914.03, 2 ,9956.74, 2 , 0 , 0 , 0 ,,
    4.00    4.00
  443.35 1443.35
    4.00    4.00
  443.09 1443.09
Pier Skew, UpSta & Num, DnSta & Num=  ,9980.32, 2 ,10023.03, 2 , 0 , 0 , 0 ,,
    4.00    4.00
  442.95 1442.95
    4.00    4.00
  442.69 1442.69
Pier Skew, UpSta & Num, DnSta & Num=  ,10046.61, 2 ,10089.32, 2 , 0 , 0 , 0 ,,
    4.00    4.00
  442.54 1442.54
    4.00    4.00
  442.28 1442.28
BR Coef=-1 , 0 , 0 ,, 0 ,,,0.8,0,1,0,
WSPro=,,,, 1 ,,,, 0 ,,,, 0 ,,,,-1 ,-1 ,-1 , 0 , 0 , 0 , 0 , 0
BC Design=,, 0 ,, 0 ,,,,,,

Type RM Length L Ch R = 1 ,108021.8,173.696100,173.696100,173.696100
XS GIS Cut Line= 5
603147.819640458796271.118965954602617.264084905796665.563410372
602492.264084905796746.118965939602358.930751562797185.007854834
601920.041862667797471.118965954
#Sta/Elev= 30
 9054.071612.5739082.5051612.1539211.4221541.2129295.2251519.4669331.7221517.326
9356.6441499.6679431.4091467.2379697.4821461.0779741.6741447.2069904.5311444.659
9956.7881422.964 10019.5 1420.9710113.561438.57610291.231442.85910327.281455.187
 10359.21471.68910377.511493.44610414.131518.56710458.59 1542.1310487.381547.375
   105241585.60510566.031616.295 10589.91620.79510637.651662.66810697.341698.704
10721.21 1705.5210733.151704.68110762.051681.91610816.991651.879 10846.51648.522
#Mann= 3 , 0 , 0
 9054.07  0.0535       0 9054.07  0.0535       0 10846.5  0.0535       0
#XS Ineff= 2 , 0
       09898.509                       0
Bank Sta=9054.07,10846.5
Exp/Cntr=0.3,0.1

Type RM Length L Ch R = 1 ,107848.1,424.548100,424.548100,424.548100
XS GIS Cut Line= 6
603097.856974465796152.392692702602934.548415376796294.710373951
602723.738379538796463.071269398601954.987503506 797023.46359702
601780.197927639797163.772771962601698.172088454797235.949786858
#Sta/Elev= 30
9051.8651546.7229149.1931600.6489192.2571604.2839280.8391564.7449347.8321542.635
9395.2831507.8339476.4771468.1059574.9721468.3619591.6951462.9539636.5391462.932
9661.4921453.7989747.9981448.1749932.8311446.1719982.5941419.02210020.111419.801
10065.78 1436.0810220.461435.76810289.291441.914 10328.11458.08810352.681480.088
10377.37 1487.6910408.621512.21710452.231536.19910553.071542.37810605.511555.751
10621.261574.90810629.951579.74110694.67 1585.2610760.711566.91310823.09 1569.72
#Mann= 3 , 0 , 0
9051.865  0.0498       09051.865  0.0498       010823.09  0.0498       0
#XS Ineff= 2 , 0
       09914.225                       0
Bank Sta=9051.865,10823.09
Exp/Cntr=0.3,0.1