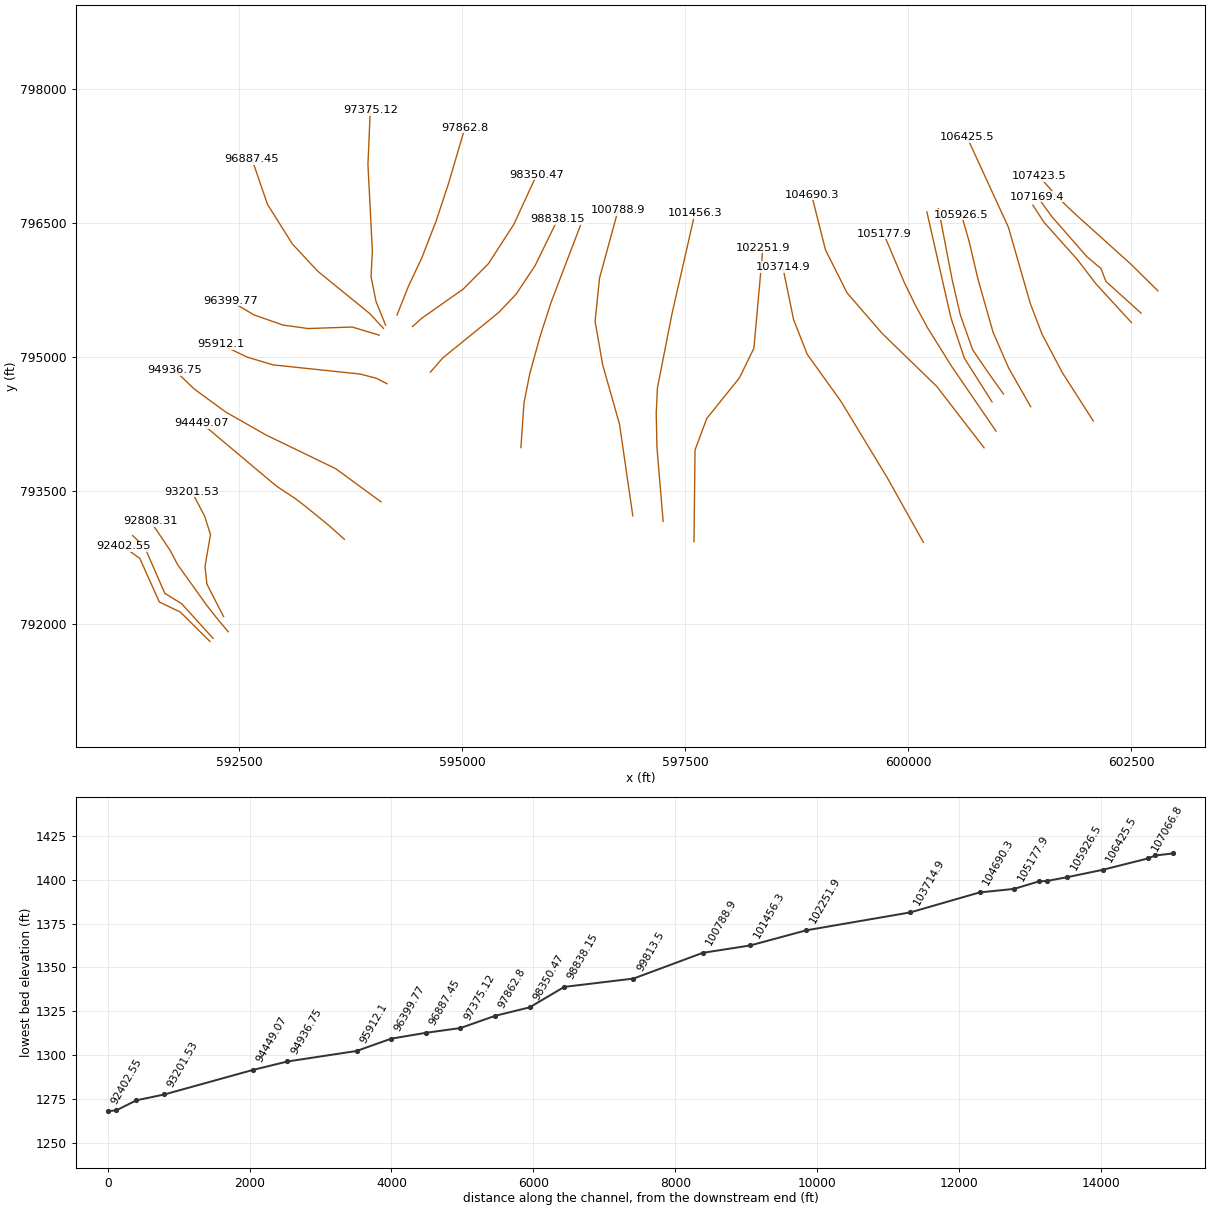
HEC-RAS study 10395_ras.prj: 10395

--- 10395_ras.g01 (geometry) --- (continued)

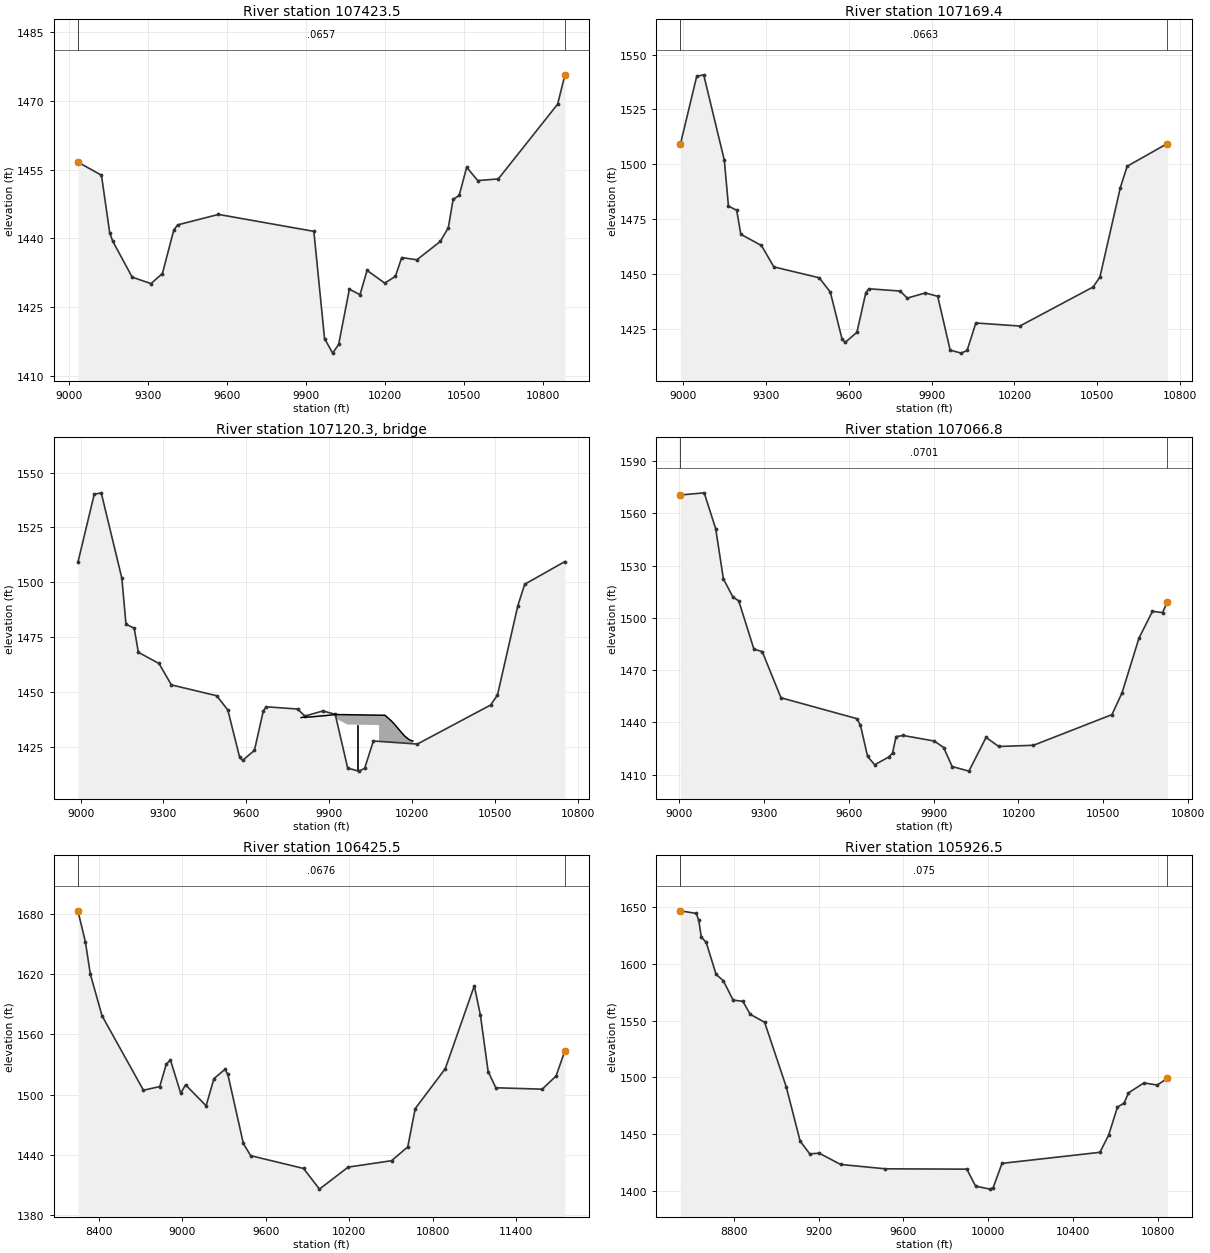
Type RM Length L Ch R = 1 ,107423.5,254.071600,254.071600,254.071600
XS GIS Cut Line= 6
602797.343327116795738.272890969602492.940705571796038.968258151
601889.412400021796581.970623072601768.002332738796695.825309601
601625.373659075796841.347844549601467.358031785797020.682182757
#Sta/Elev= 30
9033.8421456.6179123.3211453.7599154.746 1441.159166.2941439.3429239.9451431.526
9311.3011430.1149354.7191432.3179398.1361441.8399412.6081442.9259567.5761445.207
 9929.681441.5149970.2211418.138   100011414.94810023.731416.83610064.531428.899
10104.851427.69110131.731432.99210198.931430.22110239.25  1431.7 10263.21435.791
10320.811435.30810409.641439.30310440.081442.29310458.411448.48410481.481449.362
10509.861455.49610551.951452.58710629.951452.95410855.111469.25310882.911475.658
#Mann= 3 , 0 , 0
9033.842  0.0657       09033.842  0.0657       010882.91  0.0657       0
#XS Ineff= 2 , 0
       09910.326                       0
Bank Sta=9033.842,10882.91
Exp/Cntr=0.3,0.1

Type RM Length L Ch R = 1 ,107169.4,102.589500,102.589500,102.589500
XS GIS Cut Line= 6
602608.930751562 795488.43378076602214.486307144795843.989336312
602158.930751592 795988.43378076602000.597418219796121.767114118
601609.190864146 796569.45434919601447.658559531 796793.12975651
#Sta/Elev= 30
8990.3391509.0179049.4831540.0879074.824 1540.779149.5011501.8139164.4371480.877
9194.3081478.9679209.2441468.0069283.9221462.8989328.7281453.145 9493.021448.175
9533.1781441.6629575.6641420.2369586.7491418.6499629.606  1423.39661.7481441.339
9672.462 1443.159785.8671442.1189812.0141438.8989877.381 1441.259922.0271439.707
9967.1291415.17810006.981413.78910028.381414.99710060.111427.54610219.511426.142
10484.641443.96110509.311448.47110583.321489.33610607.991499.054 10753.71509.427
#Mann= 3 , 0 , 0
8990.339  0.0663       08990.339  0.0663       0 10753.7  0.0663       0
#XS Ineff= 2 , 0
       0 9921.68        10380.38       0
Bank Sta=8990.339,10753.7
Exp/Cntr=0.3,0.1

Type RM Length L Ch R = 3 ,107120.3,,,
BEGIN DESCRIPTION:
END DESCRIPTION:
Bridge Culvert--1,0,-1,-1, 0
Deck Dist Width WeirC Skew NumUp NumDn MinLoCord MaxHiCord MaxSubmerge Is_Ogee
33.250150,36.089200,2.6,0, 40, 40, , , 0.95, 0, 0,0,,
 9798.66 9805.18 9807.15 9812.57 9819.50 9822.25 9832.14 9838.60 9844.78 9854.95
 9857.42 9870.06 9871.30 9882.70 9887.65 9895.34 9897.57 9903.48 9908.59 9918.02
 9925.74 9925.7410080.5910080.5910102.2510109.4210114.0310122.8110129.0710136.20
10144.1110149.5910159.1510162.9710174.1910176.3610189.2310189.7510202.5310202.65
 1438.22 1438.37 1438.39 1438.38 1438.43 1438.46 1438.50 1438.56 1438.63 1438.78
 1438.81 1438.96 1438.97 1439.06 1439.13 1439.26 1439.28 1439.35 1439.39 1439.63
 1439.61 1439.61 1439.32 1439.32 1439.28 1438.47 1437.96 1436.97 1436.18 1435.21
 1434.06 1433.23 1431.83 1431.23 1429.71 1429.45 1428.18 1428.14 1427.49 1427.49
  438.22  438.37  438.39  438.38  438.43  438.46  438.50  438.56  438.63  438.78
  438.81  438.96  438.97  439.06  439.13  439.26  439.28  439.35  439.39  439.63
  439.61 1435.11 1434.82  439.32  439.28  438.47  437.96  436.97  436.18  435.21
  434.06  433.23  431.83  431.23  429.71  429.45  428.18  428.14  427.49  427.49
 9798.66 9805.18 9807.15 9812.57 9819.50 9822.25 9832.14 9838.60 9844.78 9854.95
 9857.42 9870.06 9871.30 9882.70 9887.65 9895.34 9897.57 9903.48 9908.59 9918.02
 9935.95 9935.9510090.8010090.8010102.2510109.4210114.0310122.8110129.0710136.20
10144.1110149.5910159.1510162.9710174.1910176.3610189.2310189.7510202.5310202.65
 1438.22 1438.37 1438.39 1438.38 1438.43 1438.46 1438.50 1438.56 1438.63 1438.78
 1438.81 1438.96 1438.97 1439.06 1439.13 1439.26 1439.28 1439.35 1439.39 1439.63
 1439.59 1439.59 1439.30 1439.30 1439.28 1438.47 1437.96 1436.97 1436.18 1435.21
 1434.06 1433.23 1431.83 1431.23 1429.71 1429.45 1428.18 1428.14 1427.49 1427.49
  438.22  438.37  438.39  438.38  438.43  438.46  438.50  438.56  438.63  438.78
  438.81  438.96  438.97  439.06  439.13  439.26  439.28  439.35  439.39  439.63
  439.59 1435.09 1434.80  439.30  439.28  438.47  437.96  436.97  436.18  435.21
  434.06  433.23  431.83  431.23  429.71  429.45  428.18  428.14  427.49  427.49
Pier Skew, UpSta & Num, DnSta & Num=  ,10003.16, 2 ,10013.38, 2 , 0 , 0 , 0 ,,
    4.00    4.00
  439.47 1439.47
    4.00    4.00
  439.45 1439.45
BR Coef=-1 , 0 , 0 ,, 0 ,,,0.8,0,1,0,
WSPro=,,,, 1 ,,,, 0 ,,,, 0 ,,,,-1 ,-1 ,-1 , 0 , 0 , 0 , 0 , 0
BC Design=,, 0 ,, 0 ,,,,,,

Type RM Length L Ch R = 1 ,107066.8,641.372500,641.372500,641.372500
XS GIS Cut Line= 5
602500.597418249795382.878225207 602103.37519604795816.211558551
601895.041862667 796088.43378076601521.256340861796505.908519417
601395.575226158 796699.37975651
#Sta/Elev= 30
9004.7471570.4569089.0191571.7059129.7161551.0569156.8481522.3959190.617 1511.92
 9211.111509.7479264.6121482.133 9294.211480.6339360.3331454.1889628.8451442.197
9641.4371438.3789666.6221420.5139691.8071415.7519742.1761420.2869754.7691422.515
9767.3611431.9149792.5461432.5469902.5481429.369 9935.451425.6569965.4331414.762
10024.741412.11310085.361431.45710130.34 1426.2410252.921426.93610530.441444.524
10566.211457.08810625.831488.34410673.531503.74910709.151503.01510726.451509.197
#Mann= 3 , 0 , 0
9004.747  0.0701       09004.747  0.0701       010726.45  0.0701       0
#XS Ineff= 2 , 0
       09921.574        10397.22       0
Bank Sta=9004.747,10726.45
Exp/Cntr=0.3,0.1

Type RM Length L Ch R = 1 ,106425.5,499.016700,499.016700,499.016700
XS GIS Cut Line= 6
602072.919588437794280.047381643 601726.50581596 794821.23546573
601497.803385732 795254.13145396601367.451290536795595.172009658
601121.442094318796451.495833354600657.289200929797462.336633043
#Sta/Elev= 30
8249.0421683.2428302.8621652.323 8338.781619.8888422.5871578.5578720.3491504.255
8837.5831507.9428884.3821530.3018914.6721534.3338988.4251501.2579023.0751509.693
9170.9091488.7459227.1131515.7989305.079 1524.959327.1891520.1379438.6931451.163
9491.3571438.9739871.5061426.2169985.9551405.59810192.291427.56310504.151433.948
10620.791447.73910674.241485.87510890.751525.84911099.22 1608.4511143.441578.979
11198.711522.91711253.981506.73311587.231505.31111687.25 1518.4711750.961543.812
#Mann= 3 , 0 , 0
8249.042  0.0676       08249.042  0.0676       011750.96  0.0676       0
#XS Ineff= 2 , 0
       0 9863.61        10331.13       0
Bank Sta=8249.042,11750.96
Exp/Cntr=0.3,0.1

Type RM Length L Ch R = 1 ,105926.5,287.679200,287.679200,287.679200
XS GIS Cut Line= 6
601371.153272093794440.720233186601124.994743802794872.692216204
600950.406407028795272.307833324600781.703922449795864.842807262
600682.311151768796289.077474727600595.113978584796591.168065648
#Sta/Elev= 30
8546.6121646.9388621.9071644.6448633.6211638.4538645.3351623.8568668.7621619.086
8714.9951590.9858749.6131585.2568795.7691568.1888841.9251567.068 8876.461555.689
8944.4911548.6289046.4881491.749 9112.261443.829 9157.781432.4969202.1361433.151
9303.3631423.187  9514.81419.3419899.4071419.0459940.8891404.07510009.34 1401.42
10024.071402.84710065.581424.14810528.081433.89610569.541449.26710611.021473.921
10642.141477.22610662.881486.33810735.71 1495.1210798.461493.25410846.741499.184
#Mann= 3 , 0 , 0
8546.612   0.075       08546.612   0.075       010846.74   0.075       0
#XS Ineff= 2 , 0
       0 9744.08        10141.53       0
Bank Sta=8546.612,10846.74
Exp/Cntr=0.3,0.1

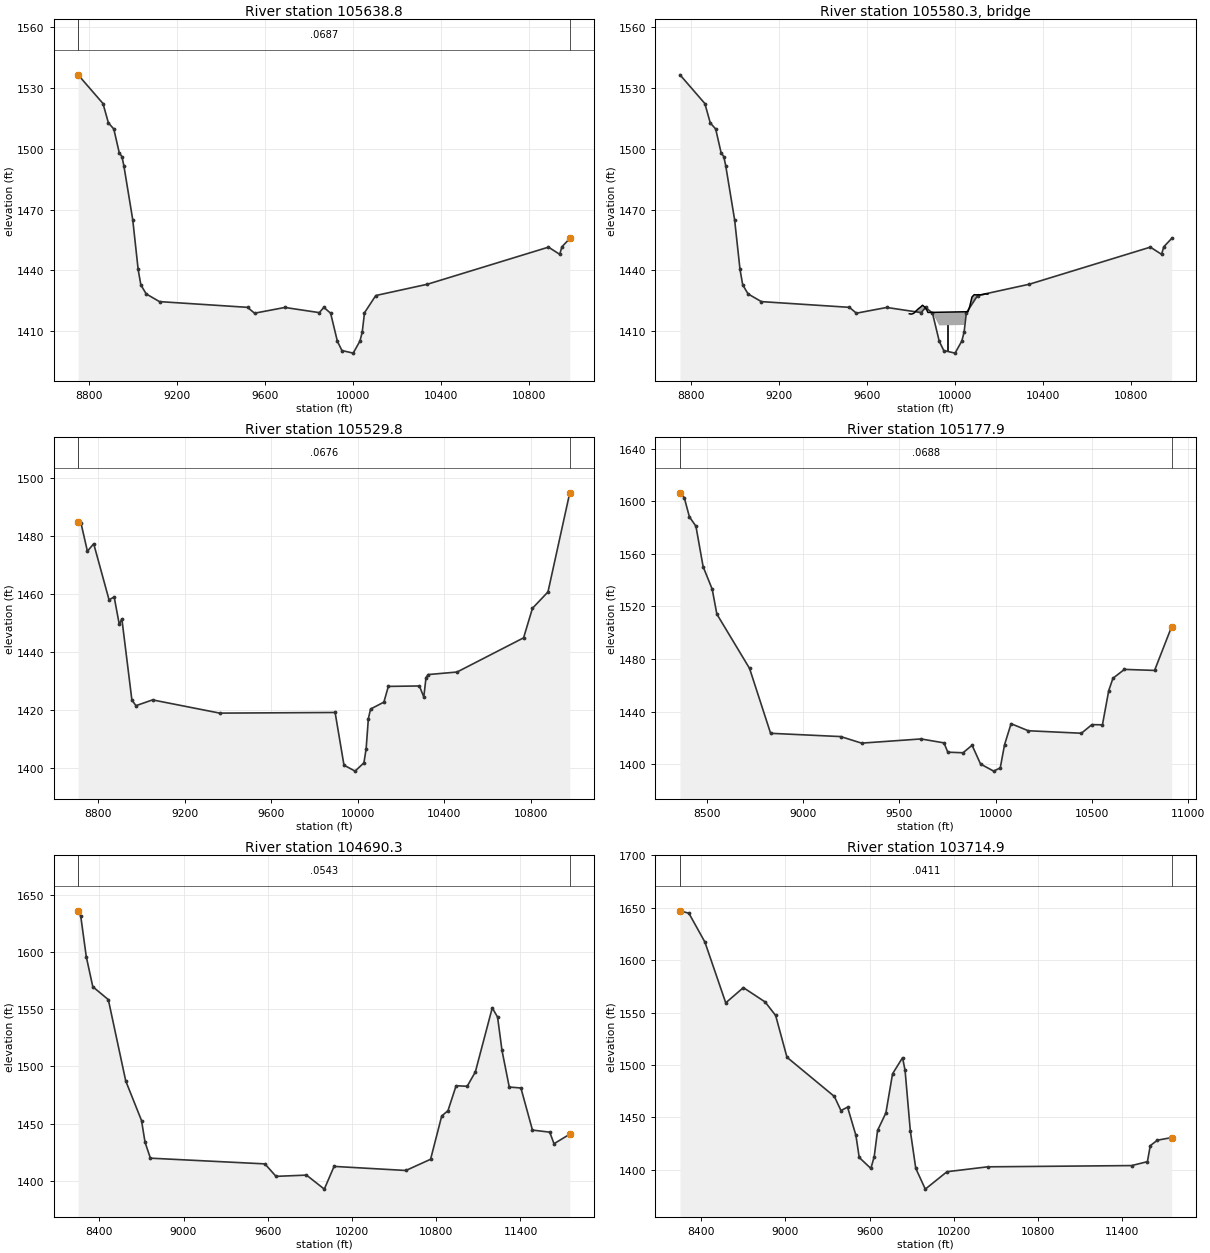
Type RM Length L Ch R = 1 ,105638.8,108.944000,108.944000,108.944000
XS GIS Cut Line= 6
601065.736307114794583.017114103600899.069640458794816.350447446
600721.291862667795077.461558536600582.402973771795469.128225222
600490.736307114795866.350447431 600337.59342541 796659.90901624
#Sta/Elev= 30
8749.6881536.4118862.7261522.2558887.3041512.7098911.8821509.715 8936.461498.032
8948.7491496.0898957.411 1491.698997.9051464.9849022.484 1440.469034.7731432.869
9058.9941428.4329119.4831424.6329519.468 1421.819551.2991418.924 9689.231421.752
9845.7471419.2019866.2731421.7939897.061 1418.92 9927.851405.0599948.3751400.518
 9999.691399.24110030.481405.24110040.741409.611   100511419.14110102.321427.635
10337.121433.20210887.081451.48310938.011447.94410948.191451.66410983.741455.747
#Mann= 3 , 0 , 0
8749.688  0.0687       08749.688  0.0687       010983.74  0.0687       0
#XS Ineff= 2 , 0
       09716.102        10119.94       0
Bank Sta=8749.688,10983.74
Exp/Cntr=0.3,0.1

Type RM Length L Ch R = 3 ,105580.3,,,
BEGIN DESCRIPTION:
END DESCRIPTION:
Bridge Culvert--1,0,-1,-1, 0
Deck Dist Width WeirC Skew NumUp NumDn MinLoCord MaxHiCord MaxSubmerge Is_Ogee
39.216100,30.511800,2.6,0, 29, 29, , , 0.95, 0, 0,0,,
 9791.81 9795.11 9800.78 9810.99 9821.20 9831.41 9841.62 9844.70 9851.83 9862.04
 9864.07 9864.07 9872.25 9876.4210058.6010064.2010064.2010066.2310076.4410086.65
10092.6510096.8610107.0710117.2810127.4910137.7010142.2410147.9110149.53
 1418.63 1418.57 1418.47 1418.80 1419.91 1420.97 1421.84 1422.13 1422.85 1421.92
 1421.59 1421.59 1420.27 1419.29 1419.65 1421.56 1421.56 1422.25 1426.88 1428.06
 1427.98 1427.96 1428.04 1428.00 1428.12 1428.47 1428.39 1428.29 1428.41
  418.63  418.57  418.47  418.80  419.91  420.97  421.84  422.13  422.85  421.92
  421.59 1415.09 1413.77 1412.79 1413.15 1415.06  421.56  422.25  426.88  428.06
  427.98  427.96  428.04  428.00  428.12  428.47  428.39  428.29  428.41
 9791.81 9795.11 9800.78 9810.99 9821.20 9831.41 9841.62 9844.70 9851.83 9862.04
 9870.89 9870.89 9872.25 9876.4210058.6010066.2310071.0310071.0310076.4410086.65
10092.6510096.8610107.0710117.2810127.4910137.7010142.2410147.9110149.53
 1418.63 1418.57 1418.47 1418.80 1419.91 1420.97 1421.84 1422.13 1422.85 1421.92
 1420.48 1420.48 1420.27 1419.29 1419.65 1422.25 1424.43 1424.43 1426.88 1428.06
 1427.98 1427.96 1428.04 1428.00 1428.12 1428.47 1428.39 1428.29 1428.41
  418.63  418.57  418.47  418.80  419.91  420.97  421.84  422.13  422.85  421.92
  420.48 1413.98 1413.77 1412.79 1413.15 1415.75 1417.93  424.43  426.88  428.06
  427.98  427.96  428.04  428.00  428.12  428.47  428.39  428.29  428.41
Pier Skew, UpSta & Num, DnSta & Num=  ,9964.14, 2 ,9970.96, 2 , 0 , 0 , 0 ,,
    4.00    4.00
  419.47 1419.47
    4.00    4.00
  419.48 1419.48
BR Coef=-1 , 0 , 0 ,, 0 ,,,0.8,0,1,0,
WSPro=,,,, 1 ,,,, 0 ,,,, 0 ,,,,-1 ,-1 ,-1 , 0 , 0 , 0 , 0 , 0
BC Design=,, 0 ,, 0 ,,,,,,

Type RM Length L Ch R = 1 ,105529.8,351.901900,351.901900,351.901900
XS GIS Cut Line= 6
600937.958529383794494.128225192600626.847418249794985.794891879
600476.847418219795438.572669655600326.847418249796099.683780774
600249.176056653796442.013115242600208.055675252796623.247388839
#Sta/Elev= 30
8707.2571484.7458720.1231484.4878750.194 1474.688779.2921477.2538850.2951457.966
8873.9631458.952 8897.631449.4878909.4641451.4448955.9121423.4968974.6141421.553
 9051.471423.5429361.9911418.9929895.7061419.2139936.7221401.0949987.9931399.038
10029.011401.89410039.261406.81810049.521417.13710059.771420.396 10121.31422.778
10141.811428.18310285.361428.33510305.871424.54210316.131431.23610326.381432.256
10459.681433.12910767.311444.88910808.331455.05210880.111460.68610980.851494.769
#Mann= 3 , 0 , 0
8707.257  0.0676       08707.257  0.0676       010980.85  0.0676       0
#XS Ineff= 2 , 0
       09705.268        10111.27       0
Bank Sta=8707.257,10980.85
Exp/Cntr=0.3,0.1

Type RM Length L Ch R = 1 ,105177.9,487.675500,487.675500,487.675500
XS GIS Cut Line= 6
600982.371933042 794166.49053867600484.885359783794892.843603428
600215.369724848795324.868064729600078.911953216795577.006637219
599953.604379733795834.906614716599723.785076145796377.399977302
#Sta/Elev= 30
 8361.391606.3728383.7461602.6288410.2021588.1488444.1341580.9948481.5331550.232
8528.6781533.0828552.8331514.1458722.6211472.842 8831.831423.5169195.8611421.022
9304.2621416.0399612.7791419.2289731.8671416.2419751.9221409.1579830.9011408.721
9877.9231414.4319921.8781400.149 9990.111394.752 10024.21397.24610046.581414.912
10080.341430.81410169.811425.45410445.421423.56310500.131430.11610554.641429.962
10587.34 1455.9710609.141465.33410668.851472.10910825.341471.32810913.871504.599
#Mann= 3 , 0 , 0
 8361.39  0.0688       0 8361.39  0.0688       010913.87  0.0688       0
#XS Ineff= 2 , 0
       09632.485        10112.05       0
Bank Sta=8361.39,10913.87
Exp/Cntr=0.3,0.1

Type RM Length L Ch R = 1 ,104690.3,975.350900,975.350900,975.350900
XS GIS Cut Line= 6
600848.766506372793979.931943446600318.165061462 794667.96416909
599708.208118247795259.591178984599313.162766514795715.937831051
599071.764447078796196.598539905598915.328883366 796815.15072748
#Sta/Elev= 30
8249.0581635.7548267.5761631.3068307.1451595.6768353.6051569.4718464.2131558.194
8588.3071487.1538700.5931452.6268725.8061433.626  8763.81419.7519579.3631414.759
9658.6131403.8739875.7171404.95410002.641392.71410072.111412.56410583.641408.994
10759.541418.78610838.881456.60810883.321461.20710941.441483.00311020.24 1482.53
11078.341495.06111198.841551.01511236.72 1542.9711268.181513.82511319.991481.839
 11402.91481.05311485.171444.27711608.061442.47211638.761432.362 11750.91440.709
#Mann= 3 , 0 , 0
8249.058  0.0543       08249.058  0.0543       0 11750.9  0.0543       0
#XS Ineff= 2 , 0
       09587.451        10124.31       0
Bank Sta=8249.058,11750.9
Exp/Cntr=0.3,0.1

Type RM Length L Ch R = 1 ,103714.9,1463.026400,1463.026400,1463.026400
XS GIS Cut Line= 6
600168.933105698792919.480921516599762.907875986793646.150546522
 599245.45692951794499.349887507598866.616248482795028.043983168
598713.961745027795416.630723009598593.118859458796005.134189609
#Sta/Elev= 30
8249.0411647.0798312.4111644.7828426.5531617.2468574.937 1559.238700.4931573.766
8855.4471560.0748930.4441547.1589011.0551507.2729348.6061469.8559395.6171456.394
9442.7181459.6249502.0561432.7219525.7921411.5829608.8651401.069  9632.61412.513
9656.3351437.4059715.6731454.1489763.1431491.4889834.3491506.8659852.3091494.772
 9889.45 1437.289928.3881401.2369996.3571381.36210150.871397.98310440.031402.648
11466.51 1403.8511578.441407.60711598.791422.86911649.561428.086 11750.91430.571
#Mann= 3 , 0 , 0
8249.041  0.0411       08249.041  0.0411       0 11750.9  0.0411       0
#XS Ineff= 2 , 0
       0                10581.66       0
Bank Sta=8249.041,11750.9
Exp/Cntr=0.3,0.1

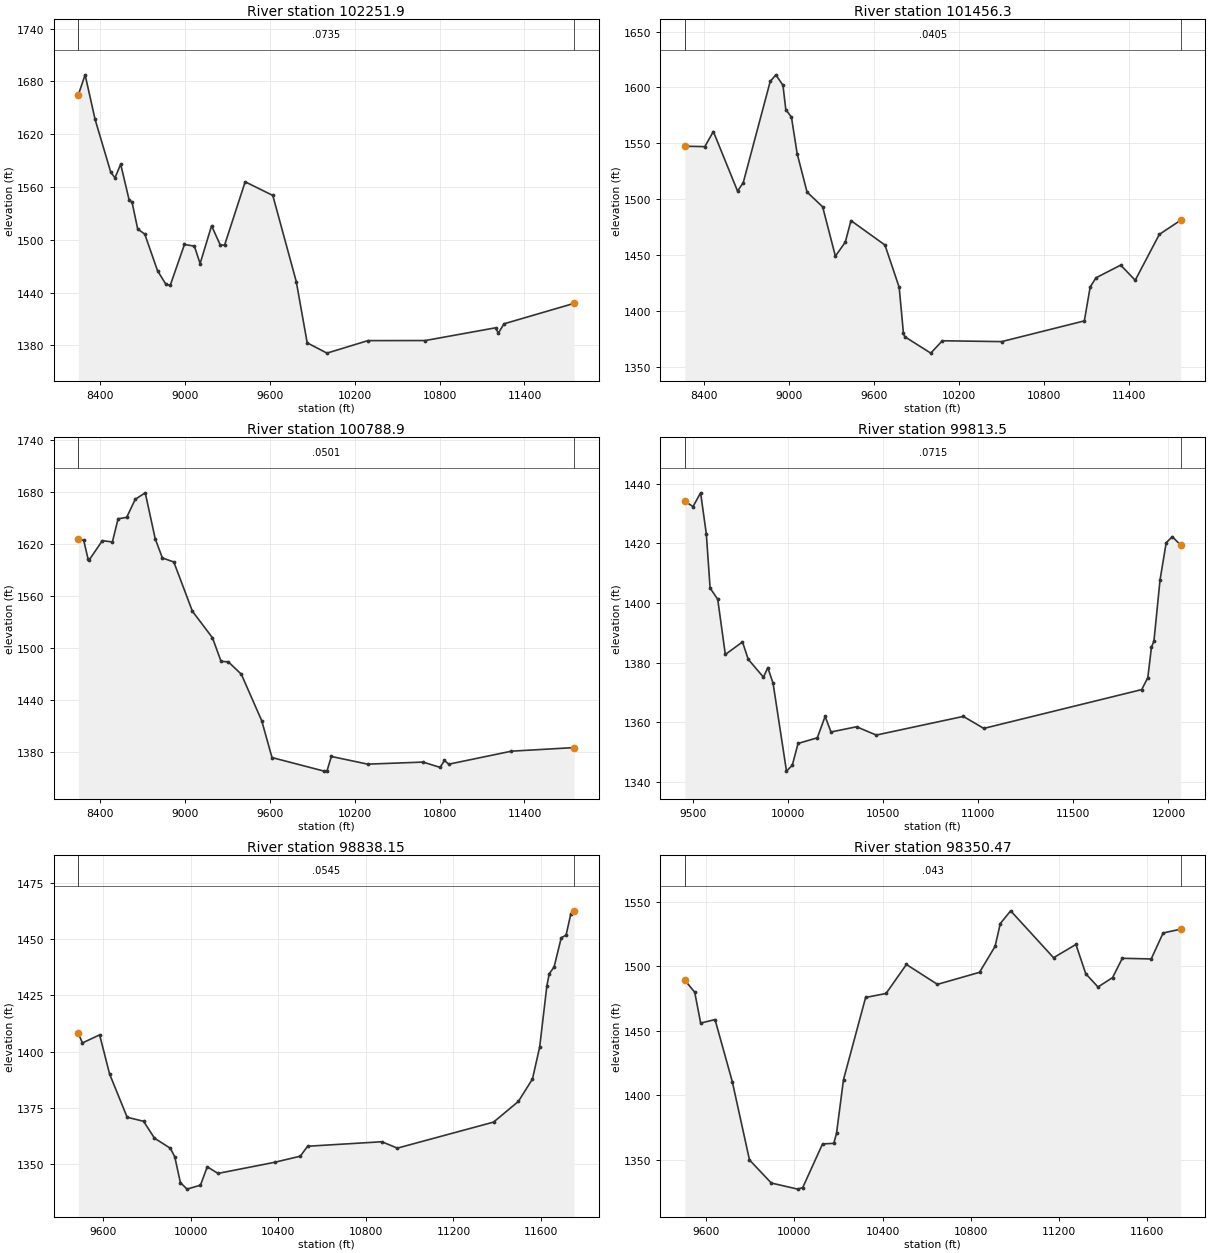
Type RM Length L Ch R = 1 ,102251.9,795.577100,795.577100,795.577100
XS GIS Cut Line= 6
597597.821674087792927.476938901597609.571867663793955.121629167
597741.352618373794308.526477547598107.843915896794764.501933521
598269.361722409795094.911459316 598370.23731333796220.399311778
#Sta/Elev= 30
8249.1661664.6648297.0161687.4158367.4981636.7488478.0211576.8358508.1221570.347
8548.2141585.9118608.2841544.9598628.3071542.9028668.3541512.2268718.3791506.439
8808.3811464.8858868.401 1449.18 8898.421448.269 8998.641494.6739068.8481492.701
9109.2321472.9179190.1631515.9169251.2931494.0779281.8581493.8119427.4231565.856
 9622.551550.3719788.2091452.5689865.4751382.88310005.091371.18710294.481385.402
10699.111385.49111195.371399.95211215.381393.86711255.411404.49911750.871427.766
#Mann= 3 , 0 , 0
8249.166  0.0735       08249.166  0.0735       011750.87  0.0735       0
#XS Ineff= 2 , 0
       0                10438.97       0
Bank Sta=8249.166,11750.87
Exp/Cntr=0.3,0.1

Type RM Length L Ch R = 1 ,101456.3,667.449300,667.449300,667.449300
XS GIS Cut Line= 6
597252.170186504793154.679899754597182.654659132793985.255925264
597174.655012265794370.619704513597188.478743548 794653.07011772
597352.156677732 795485.64278542597607.876512216796607.906114808
#Sta/Elev= 30
8261.8731547.487 8403.271547.1278463.6161560.6358634.4021507.3998674.5561514.861
8865.0641605.3798905.118 1611.328955.1851601.9428975.2121580.2829015.2651573.411
9055.3191540.9349125.3861506.4849235.4351493.3229325.4751449.2079395.4791461.746
 9435.481480.9989675.632 1459.169775.9981421.3629806.2411380.0739815.5531377.211
9999.0511362.52510080.781373.58410499.711372.81711083.821391.35211124.891421.591
11165.951429.85911340.471441.19911443.131427.67411613.261468.655 11763.81481.322
#Mann= 3 , 0 , 0
8261.873  0.0405       08261.873  0.0405       0 11763.8  0.0405       0
#XS Ineff= 2 , 0
       0                10372.14       0
Bank Sta=8261.873,11763.8
Exp/Cntr=0.3,0.1

Type RM Length L Ch R = 1 ,100788.9,975.351000,975.351000,975.351000
XS GIS Cut Line= 6
596912.175036492793217.090237098596763.112393877794244.799247185
596574.711027573794908.349170211596489.502277603795396.437004424
596538.941638277795879.468246058596746.750831598796640.828452715
#Sta/Elev= 30
8249.0621625.9448287.3741624.2558317.6911602.8848327.7971602.261 8418.751624.035
8489.4921622.4768529.9121649.2018590.447 1650.858650.981 1671.698721.6041679.145
8792.2281626.0998842.6731604.0698923.3861599.429 9054.661542.6779196.4231512.062
9257.3581484.7769308.2581484.3479400.1981470.0419544.1181416.5099616.7511373.981
9984.9781358.33510005.311358.52110035.921375.25310292.331366.38910683.581368.755
10804.431362.62810834.851370.67410865.28 1366.3411307.431381.329 11750.91385.481
#Mann= 3 , 0 , 0
8249.062  0.0501       08249.062  0.0501       0 11750.9  0.0501       0
#XS Ineff= 2 , 0
       0                10446.02       0
Bank Sta=8249.062,11750.9
Exp/Cntr=0.3,0.1

Type RM Length L Ch R = 1 , 99813.5,975.350900,975.350900,975.350900
XS GIS Cut Line= 6
595657.913191617793981.872796133595693.169821382794488.208430976
 595759.84381181794818.990512565595873.334939212795229.664333239
595997.279088944  795612.4361628596330.636714458796485.852211669
#Sta/Elev= 30
9455.214 1434.179498.3471432.3139538.3571436.9279568.3641423.2169588.3821405.029
9628.4291401.2549668.504 1382.779758.7771386.9679788.906 1381.169869.3111375.145
 9891.871378.3689919.6431373.1599990.3271343.687 10020.81345.64510051.191352.959
10152.541354.85210193.581362.03110224.541356.80510358.991358.54710462.74 1355.77
10920.911362.02211028.56    135811859.471371.00311891.66 1375.0211910.711385.172
11923.851387.29611956.041407.79811988.221420.18912020.41 1422.2412064.241419.441
#Mann= 3 , 0 , 0
9455.214  0.0715       09455.214  0.0715       012064.24  0.0715       0
#XS Ineff= 2 , 0
       0                10913.43       0
Bank Sta=9455.214,12064.24
Exp/Cntr=0.3,0.1

Type RM Length L Ch R = 1 ,98838.15,487.675500,487.675500,487.675500
XS GIS Cut Line= 6
594644.301778528 794828.42566263594783.182629156794987.264388649
595407.702196066795494.570927006595603.266339752795699.342697022
 595817.22279217796021.203829534596069.887883442796538.817565077
#Sta/Elev= 30
9487.7061408.145 9506.431403.8869584.8531407.4669630.4741390.0599710.6451370.871
9785.4981369.0939835.1831361.5979907.6861357.0979927.792 1353.349953.5061341.858
9984.0531338.95210045.31 1340.7210076.211348.872 10125.31345.92910384.27 1350.88
10500.781353.58510534.29    1358 10873.21359.99610943.771357.159   113831368.719
11496.231377.88911560.621387.85511593.651402.12111626.461429.277 11637.41434.634
11659.271437.61411692.081450.62311713.951451.74811735.821461.27711750.931462.558
#Mann= 3 , 0 , 0
9487.706  0.0545       09487.706  0.0545       011750.93  0.0545       0
#XS Ineff= 2 , 0
       0                               0
Bank Sta=9487.706,11750.93
Exp/Cntr=0.3,0.1

Type RM Length L Ch R = 1 ,98350.47,487.675400,487.675400,487.675400
XS GIS Cut Line= 6
594443.471998101795338.104996694594541.116796437795427.023804553
595010.684904468795757.496466511595294.185906297796043.004867777
595578.449894579796483.000826474595834.452814548797038.156713375
#Sta/Elev= 30
9503.9651489.142    95491479.7169575.8571455.8789640.9391458.5999719.1371410.576
9797.1331349.8989895.9921332.03110015.691327.30510038.39 1328.5410128.171362.292
10179.031362.77310191.45 1370.4110223.251412.15410323.41 1475.7210415.891478.796
10508.221501.26710648.851485.87410839.521495.18210910.211515.32810933.721532.986
10980.731542.80411175.071506.49611276.451516.76611321.031494.08811376.481483.835
11442.641491.112 11486.61506.05311617.53 1505.5411671.681525.65911750.91  1528.6
#Mann= 3 , 0 , 0
9503.965   0.043       09503.965   0.043       011750.91   0.043       0
#XS Ineff= 2 , 0
       0                               0
Bank Sta=9503.965,11750.91
Exp/Cntr=0.3,0.1

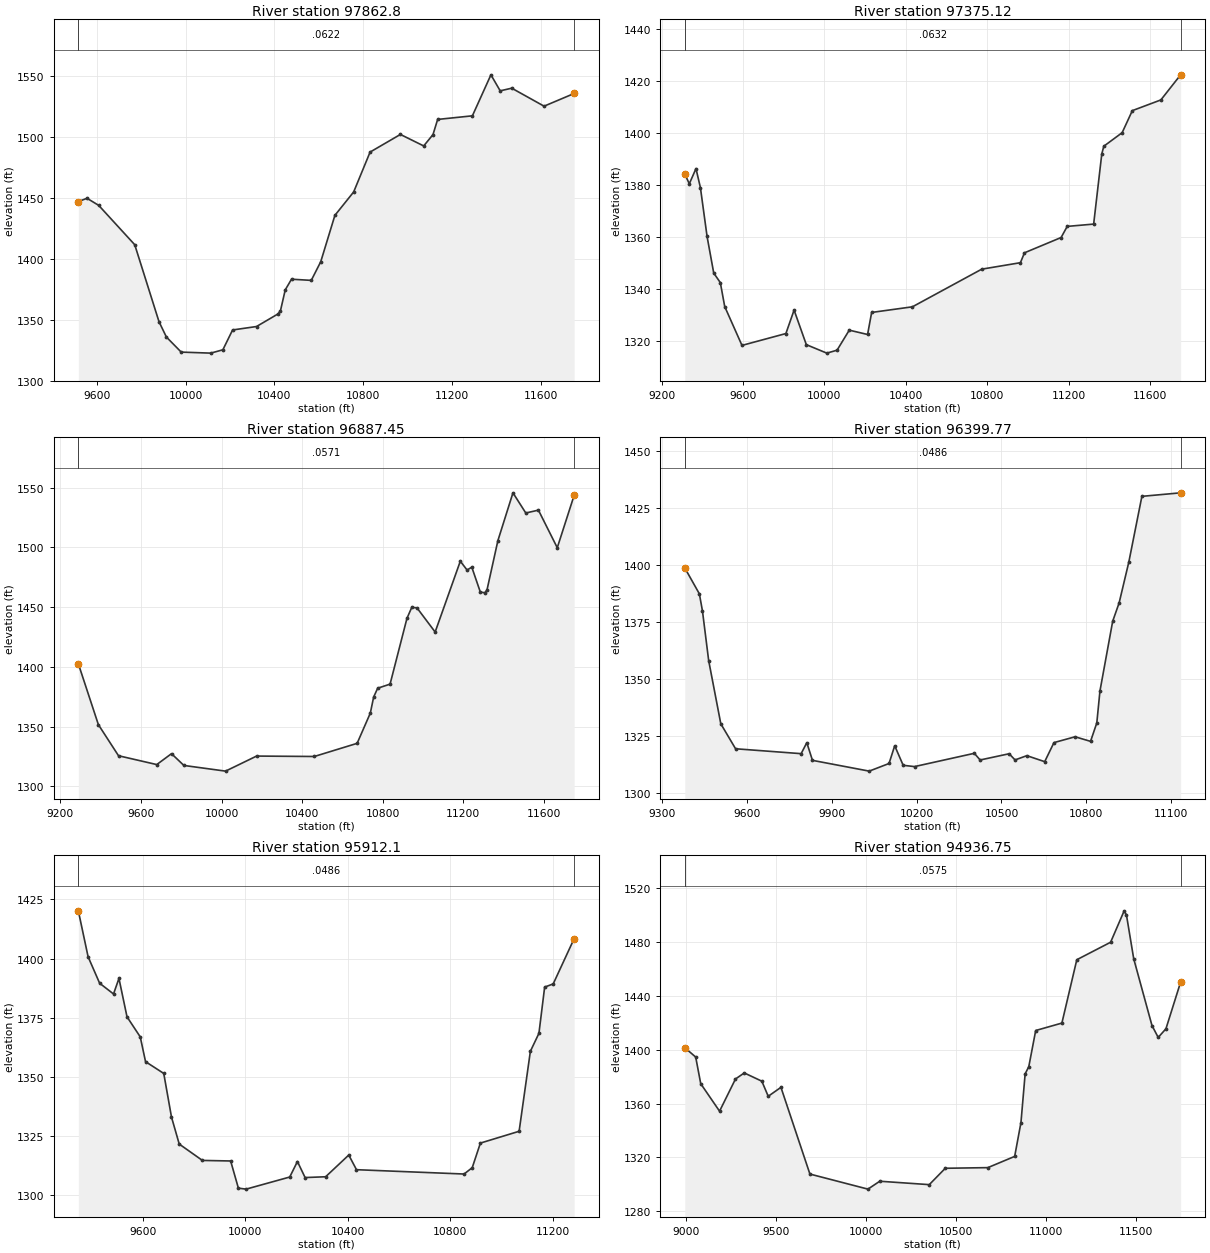
Type RM Length L Ch R = 1 , 97862.8,487.675500,487.675500,487.675500
XS GIS Cut Line= 6
594269.671449132795467.838855996594395.920704226795786.330664504
594546.484608582796105.612452318594709.105602887796524.524119776
594844.211643745796933.347335232595030.366244584797565.292139345
#Sta/Elev= 30
9516.2521446.7429555.3551449.4889608.1161443.6529770.5031411.3819879.8541348.252
9913.2031335.675  9979.91323.32110112.941322.47810167.681325.20910211.481341.472
10319.371344.30310416.461354.65810427.251357.222 10448.81374.34910477.011383.101
 10566.11382.14710608.76 1397.4310672.641435.49610757.221454.67810831.231487.377
10967.881501.83811072.891492.41411114.771501.73311135.661514.148 11292.31517.109
11375.841550.73211417.611537.59711469.66 1539.7811615.361525.01811750.96 1535.44
#Mann= 3 , 0 , 0
9516.252  0.0622       09516.252  0.0622       011750.96  0.0622       0
#XS Ineff= 2 , 0
       0                               0
Bank Sta=9516.252,11750.96
Exp/Cntr=0.3,0.1

Type RM Length L Ch R = 1 ,97375.12,487.675500,487.675500,487.675500
XS GIS Cut Line= 6
594141.250843985795354.659344044594033.913075473 795620.05761615
593978.530348727795897.495297907593993.333945903796184.368704038
593943.822311334797154.217195458593969.951258472797761.727321918
#Sta/Elev= 30
9313.4711384.2739335.6721380.5489368.4161386.3859390.2451379.0829422.9891360.318
9455.7331346.2669488.1491342.595 9509.681333.4149594.5431318.4929810.4741323.044
9850.7251332.0499910.9231318.77810011.551315.52410061.941316.64810121.971324.343
10212.031322.68210232.051331.14910432.491333.30910773.211347.76410963.381350.249
10983.381354.04811163.411359.91811193.411364.18611323.431365.07311363.431392.036
11373.441394.97911463.511400.17411513.551408.63911653.851412.75111750.971422.388
#Mann= 3 , 0 , 0
9313.471  0.0632       09313.471  0.0632       011750.97  0.0632       0
#XS Ineff= 2 , 0
       0                               0
Bank Sta=9313.471,11750.97
Exp/Cntr=0.3,0.1

Type RM Length L Ch R = 1 ,96887.45,487.675400,487.675400,487.675400
XS GIS Cut Line= 6
594117.708570425795317.740778678593964.396632399795483.199267839
 593379.65347002795959.524058152593096.087602039796264.848473108
592817.481508056796708.672520703592643.056773486797216.815503127
#Sta/Elev= 30
9288.936  1402.79388.4581351.7139488.448 1325.699678.3871318.2979751.5661327.421
9813.0051317.56410019.971312.81110174.021325.41110460.521325.062 10673.31336.065
10738.861361.41210755.431374.86110775.341382.19510836.871385.62510920.741440.686
10944.481449.82710970.311449.49311060.691429.22311185.631488.49211219.251481.115
11242.631483.52911285.091462.63911307.031462.10911318.011464.33711372.221505.704
11447.051545.72411510.78 1528.84 11573.5 1531.2411667.091499.78511750.951543.667
#Mann= 3 , 0 , 0
9288.936  0.0571       09288.936  0.0571       011750.95  0.0571       0
#XS Ineff= 2 , 0
       0                               0
Bank Sta=9288.936,11750.95
Exp/Cntr=0.3,0.1

Type RM Length L Ch R = 1 ,96399.77,487.675500,487.675500,487.675500
XS GIS Cut Line= 6
594069.588785475795242.280206803593767.712323335795333.032481653
593273.591380933795316.061259634592991.972766697795355.064543234
  592666.3918455795469.196266326592400.821023538795626.367777463
#Sta/Elev= 30
9380.6021398.7279432.0451387.3699443.0211379.8599464.9731358.0549507.9041330.265
9560.1141319.3059791.8891317.1579811.9041321.984 9831.921314.21910032.521309.486
10102.62 1312.8410122.621320.63210152.621312.04210192.631311.47710404.151317.315
10424.581314.37910527.191317.12110548.061314.40910589.811316.27510652.871313.642
10685.621322.01210760.281324.57310814.961322.56610837.071330.65910848.21  1344.7
10893.221375.31610916.041383.39510950.261401.31510996.461430.17211133.381431.717
#Mann= 3 , 0 , 0
9380.602  0.0486       09380.602  0.0486       011133.38  0.0486       0
#XS Ineff= 2 , 0
       0                               0
Bank Sta=9380.602,11133.38
Exp/Cntr=0.3,0.1

Type RM Length L Ch R = 1 , 95912.1,975.350900,975.350900,975.350900
XS GIS Cut Line= 6
594157.281661657794697.574671265594036.684340545794759.220446475
593854.596736943794806.283420488592879.143933554794908.906872667
 592589.22216391794996.320262987592293.536995068 795138.46265178
#Sta/Elev= 30
 9347.191420.1679385.3941400.7249430.4671389.5439484.7271385.0089505.9051391.577
9537.394 1375.349589.1741366.8489609.7651356.387 9680.971351.4049711.2291332.944
9741.4881321.5269831.9791314.6139942.3731314.3819972.5691302.889 10002.81302.477
10173.231307.59110203.271314.15310233.311307.36910313.461307.70610403.87 1316.89
10434.081310.69510854.511308.86610886.351311.54710918.211321.94811069.541326.938
11113.491360.75411146.971368.365 11169.31387.90711202.781389.26611284.611408.424
#Mann= 3 , 0 , 0
 9347.19  0.0486       0 9347.19  0.0486       011284.61  0.0486       0
#XS Ineff= 2 , 0
       0                               0
Bank Sta=9347.19,11284.61
Exp/Cntr=0.3,0.1

Type RM Length L Ch R = 1 ,94936.75,487.675500,487.675500,487.675500
XS GIS Cut Line= 6
594090.201907524 793373.86186115 593581.63118886793746.031130933
592802.134978217794122.830724451592348.396468358794381.150823035
591995.412152558794639.731953404591778.129335626794849.209390531
#Sta/Elev= 30
8990.8911401.5839051.5221394.623 9079.651374.8129184.3861354.4059273.0531378.326
9322.0071382.8199419.7491376.6899455.3161365.4739526.0591372.1239687.383 1307.68
10010.341296.483 10076.21302.35110351.761299.81610440.981311.97910677.861312.457
10827.221320.80410862.181345.99210885.491382.14110905.781387.50310944.241414.351
11090.051419.87311173.041466.948 11361.21479.939 11436.71503.28411449.521500.155
11489.871467.65111591.45 1418.07 11626.11409.22511669.221415.63811750.961450.336
#Mann= 3 , 0 , 0
8990.891  0.0575       08990.891  0.0575       011750.96  0.0575       0
#XS Ineff= 2 , 0
       0                               0
Bank Sta=8990.891,11750.96
Exp/Cntr=0.3,0.1

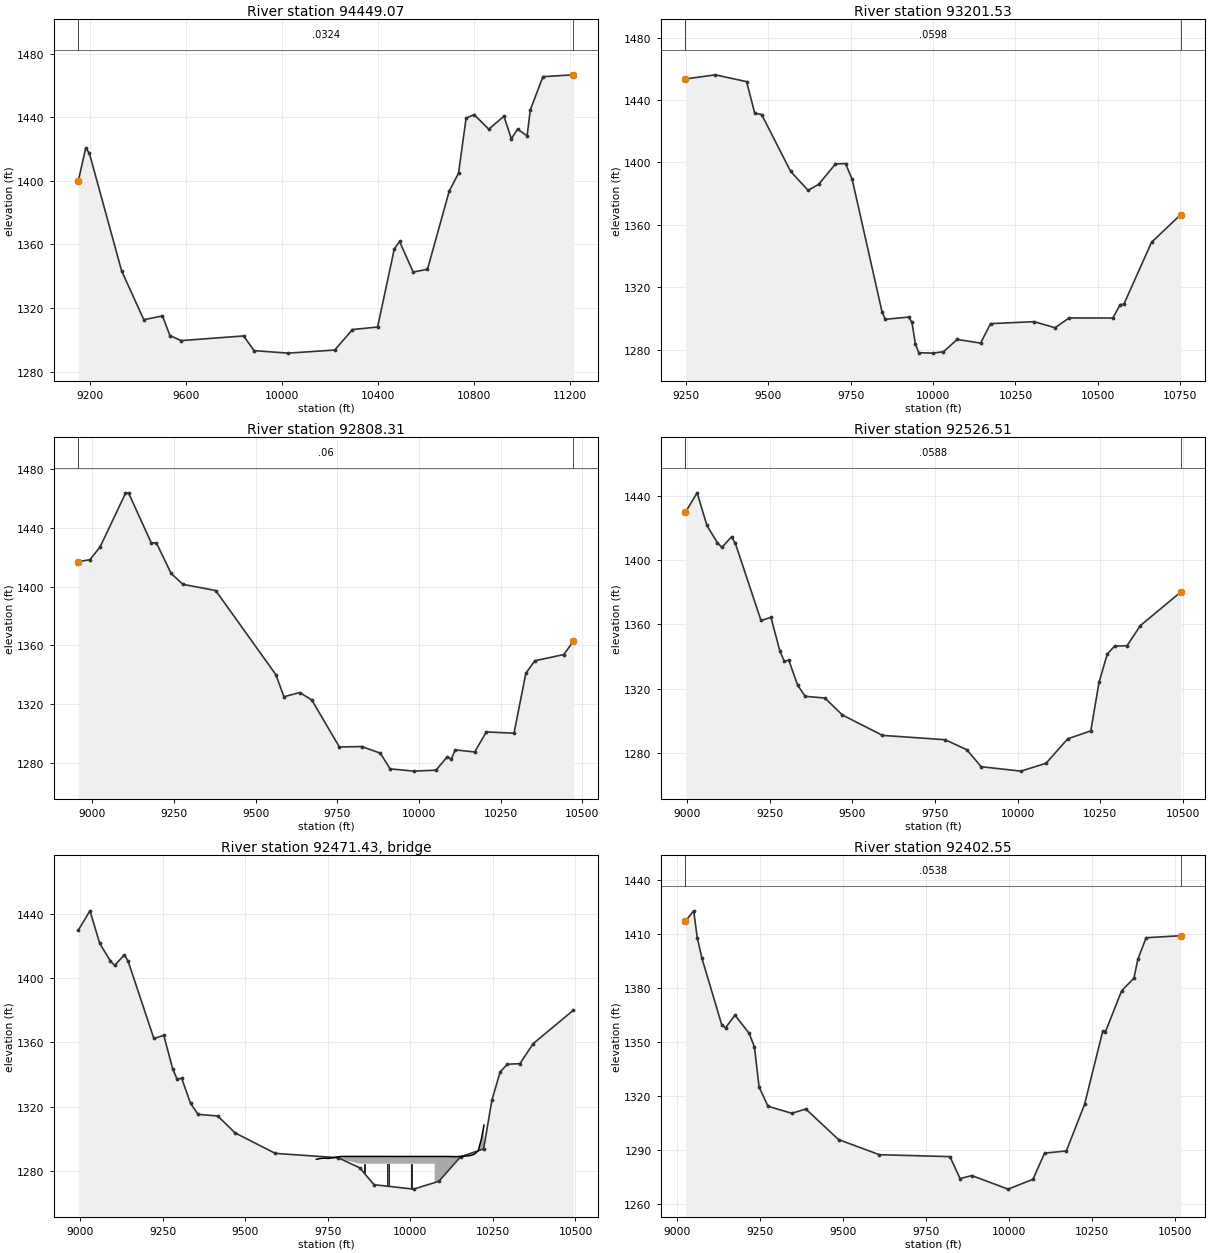
Type RM Length L Ch R = 1 ,94449.07,1247.541900,1247.541900,1247.541900
XS GIS Cut Line= 6
593679.514247844 792954.35721676593494.222637414793119.143304698
593237.381537606793328.424534284593126.906425278793412.687640508
592919.473838095 793549.28473325592079.246628796794254.537915907
#Sta/Elev= 30
9149.7321399.9569180.4371420.4149195.3121417.6069330.4861343.2839422.746 1312.68
9500.5321315.0389531.7561302.6969578.3391299.5349838.8171302.4729882.4351293.232
10024.561291.66310218.521293.607 10292.51306.49410397.151308.07410466.711357.111
10488.671361.88210545.261342.65810605.071344.36810695.611393.46210734.471404.813
   107661439.32910799.091441.61910860.611432.43310923.671440.57510954.511426.422
10980.831432.46211020.321428.23311033.481444.43111086.131465.44811213.651466.604
#Mann= 3 , 0 , 0
9149.732  0.0324       09149.732  0.0324       011213.65  0.0324       0
#XS Ineff= 2 , 0
       0                               0
Bank Sta=9149.732,11213.65
Exp/Cntr=0.3,0.1

Type RM Length L Ch R = 1 ,93201.53,393.221600,393.221600,393.221600
XS GIS Cut Line= 6
 592325.43086151792088.067903921592139.077730026792451.645793471
592117.755232614792650.847009618592179.101074155793006.754743359
592115.084476845793210.076394314591971.402702907793485.601950384
#Sta/Elev= 30
9249.1431453.488 9339.531456.1549434.5361451.7919459.2761431.5759480.2121430.699
9568.067 1394.249621.1631382.0699652.6661385.8939704.1481398.9829734.6371399.266
 9754.861389.0429845.0451304.352 9855.051299.3849925.8271300.833 9936.051297.459
9946.3041283.7089956.7911277.9699999.3791277.71110031.53  1278.610073.27 1286.49
10144.251284.12810174.271296.62110306.611297.88610369.931293.99910412.771300.278
10545.181300.20910567.511308.86410578.671309.10210662.521348.75910750.87 1366.51
#Mann= 3 , 0 , 0
9249.143  0.0598       09249.143  0.0598       010750.87  0.0598       0
#XS Ineff= 2 , 0
       0                               0
Bank Sta=9249.143,10750.87
Exp/Cntr=0.3,0.1

Type RM Length L Ch R = 1 ,92808.31,281.801800,281.801800,281.801800
XS GIS Cut Line= 6
592378.237854552791917.655789746592264.054163181 792052.66103697
592137.387822312792213.688829246591811.517435381792669.050073689
591727.273290417792829.035548497591508.400947531793155.648097197
#Sta/Elev= 30
8956.8611417.0498992.6741418.4529023.8161427.2329101.2431463.5969110.5471463.978
9180.0591429.9769196.023 1429.889240.9771409.078 9277.171401.6279377.3341397.425
9561.7851340.0629586.2161325.0899635.0771327.9059671.7221322.8359756.0031290.834
9824.2971291.1349881.2021286.6549911.4051275.9179984.209 1274.3910051.811275.046
10086.651284.25510098.581282.47610110.511288.88410170.141287.41810206.021301.084
10290.631300.24410326.891341.05910354.171349.56710443.181353.82310472.731362.944
#Mann= 3 , 0 , 0
8956.861    0.06       08956.861    0.06       010472.73    0.06       0
#XS Ineff= 2 , 0
       0                               0
Bank Sta=8956.861,10472.73
Exp/Cntr=0.3,0.1

Type RM Length L Ch R = 1 ,92526.51,123.957400,123.957400,123.957400
XS GIS Cut Line= 5
592208.710844159791843.237021491591855.933066398792232.125910386
591667.044177473792348.792577058591439.266399741792871.014799282
591305.933066368792996.014799282
#Sta/Elev= 30
8994.4891429.8189029.7791441.8729059.5461421.542 9091.381410.7129104.8811407.896
9133.9641414.5189145.386 1410.529223.2651362.4329253.3981364.3619280.4011343.462
9293.9031337.0159307.4041337.7649334.4071322.0599357.2181315.2469416.7521314.193
9469.422 1303.679591.167 1290.949781.0631288.2449846.5221281.9829890.1621271.439
10010.171268.69910086.541273.594   101521288.80410221.921293.72410246.931324.023
10272.011341.62310293.83 1346.4410331.751346.74910371.971359.25110494.061380.084
#Mann= 3 , 0 , 0
8994.489  0.0588       08994.489  0.0588       010494.06  0.0588       0
#XS Ineff= 2 , 0
       0                               0
Bank Sta=8994.489,10494.06
Exp/Cntr=0.3,0.1

Type RM Length L Ch R = 3 ,92471.43,,,
BEGIN DESCRIPTION:
END DESCRIPTION:
Bridge Culvert--1,0,-1,-1, 0
Deck Dist Width WeirC Skew NumUp NumDn MinLoCord MaxHiCord MaxSubmerge Is_Ogee
42.949850,38.057700,2.6,0, 33, 33, , , 0.95, 0, 0,0,,
 9715.51 9718.62 9723.80 9730.37 9742.13 9742.81 9752.14 9755.87 9757.70 9768.60
 9779.51 9780.94 9789.40 9791.35 9791.3510073.8310073.8310113.3410117.5710128.47
10131.8910139.3810150.2910156.9610161.1910172.1010182.0310183.0010193.9110204.81
10207.0910215.7210223.00
 1287.26 1287.38 1287.62 1287.84 1287.97 1287.95 1287.82 1287.93 1287.99 1288.33
 1288.71 1288.76 1289.04 1289.04 1289.04 1289.02 1289.02 1289.02 1288.98 1288.91
 1288.92 1288.94 1289.01 1289.08 1289.15 1289.38 1289.64 1289.67 1290.47 1292.43
 1293.66 1300.42 1308.51
  287.26  287.38  287.62  287.84  287.97  287.95  287.82  287.93  287.99  288.33
  288.71  288.76  289.04  289.04 1284.54 1284.52  289.02  289.02  288.98  288.91
  288.92  288.94  289.01  289.08  289.15  289.38  289.64  289.67  290.47  292.43
  293.66  300.42  308.51
 9715.51 9718.62 9723.80 9730.37 9742.13 9742.81 9752.14 9755.87 9757.70 9768.60
 9779.51 9780.94 9789.40 9835.01 9835.0110113.3410117.4910117.4910117.5710128.47
10131.8910139.3810150.2910156.9610161.1910172.1010182.0310183.0010193.9110204.81
10207.0910215.7210223.00
 1287.26 1287.38 1287.62 1287.84 1287.97 1287.95 1287.82 1287.93 1287.99 1288.33
 1288.71 1288.76 1289.04 1289.04 1289.04 1289.02 1288.98 1288.98 1288.98 1288.91
 1288.92 1288.94 1289.01 1289.08 1289.15 1289.38 1289.64 1289.67 1290.47 1292.43
 1293.66 1300.42 1308.51
  287.26  287.38  287.62  287.84  287.97  287.95  287.82  287.93  287.99  288.33
  288.71  288.76  289.04  289.04 1284.54 1284.52 1284.48  288.98  288.98  288.91
  288.92  288.94  289.01  289.08  289.15  289.38  289.64  289.67  290.47  292.43
  293.66  300.42  308.51
Pier Skew, UpSta & Num, DnSta & Num=  ,9860.97, 2 ,9904.63, 2 , 0 , 0 , 0 ,,
    4.00    4.00
  289.04 1289.04
    4.00    4.00
  289.03 1289.03
Pier Skew, UpSta & Num, DnSta & Num=  ,9932.59, 2 ,9976.25, 2 , 0 , 0 , 0 ,,
    4.00    4.00
  289.03 1289.03
    4.00    4.00
  289.03 1289.03
Pier Skew, UpSta & Num, DnSta & Num=  ,10004.21, 2 ,10047.87, 2 , 0 , 0 , 0 ,,
    4.00    4.00
  289.03 1289.03
    4.00    4.00
  289.02 1289.02
BR Coef=-1 , 0 , 0 ,, 0 ,,,0.8,0,1,0,
WSPro=,,,, 1 ,,,, 0 ,,,, 0 ,,,,-1 ,-1 ,-1 , 0 , 0 , 0 , 0 , 0
BC Design=,, 0 ,, 0 ,,,,,,

Type RM Length L Ch R = 1 ,92402.55,199.052600,199.052600,199.052600
XS GIS Cut Line= 5
592172.599733084791809.903688163591842.044177473792137.681465939
591605.933066368792251.570354819 591386.48862192792740.459243715
591200.377510816792873.792577043
#Sta/Elev= 30
 9025.751417.0739050.5351422.7259061.3921407.6939075.5941396.2569135.0321359.465
9146.6051357.7649175.0091364.8049217.6161354.6779233.6121347.1589247.6951324.898
9274.4251314.1989346.2751310.2849388.5231312.6579487.1031295.6949610.1121287.285
9822.9361286.2029853.3671274.0119888.7031275.6839998.3151268.16110073.15 1273.62
10107.931288.13910173.691289.375 10228.51315.16810283.311355.79210291.121355.367
10340.331378.29310377.231385.30310389.531395.96510414.14 1407.7810518.231408.905
#Mann= 3 , 0 , 0
 9025.75  0.0538       0 9025.75  0.0538       010518.23  0.0538       0
#XS Ineff= 2 , 0
       0                               0
Bank Sta=9025.75,10518.23
Exp/Cntr=0.3,0.1