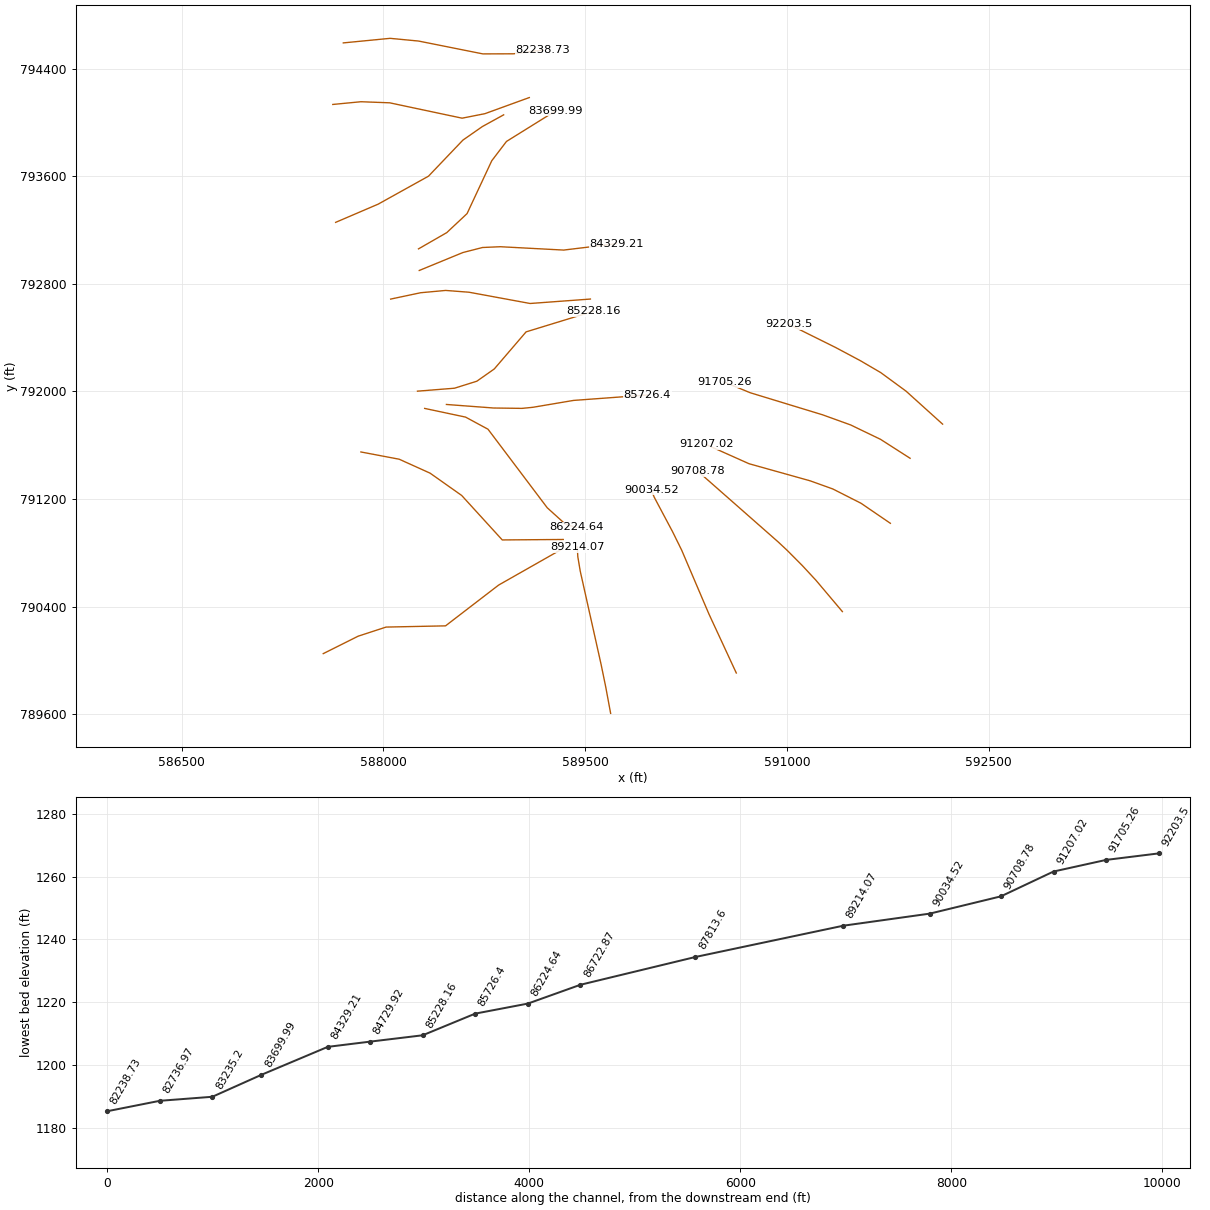
HEC-RAS study 10395_ras.prj: 10395

--- 10395_ras.g01 (geometry) --- (continued)

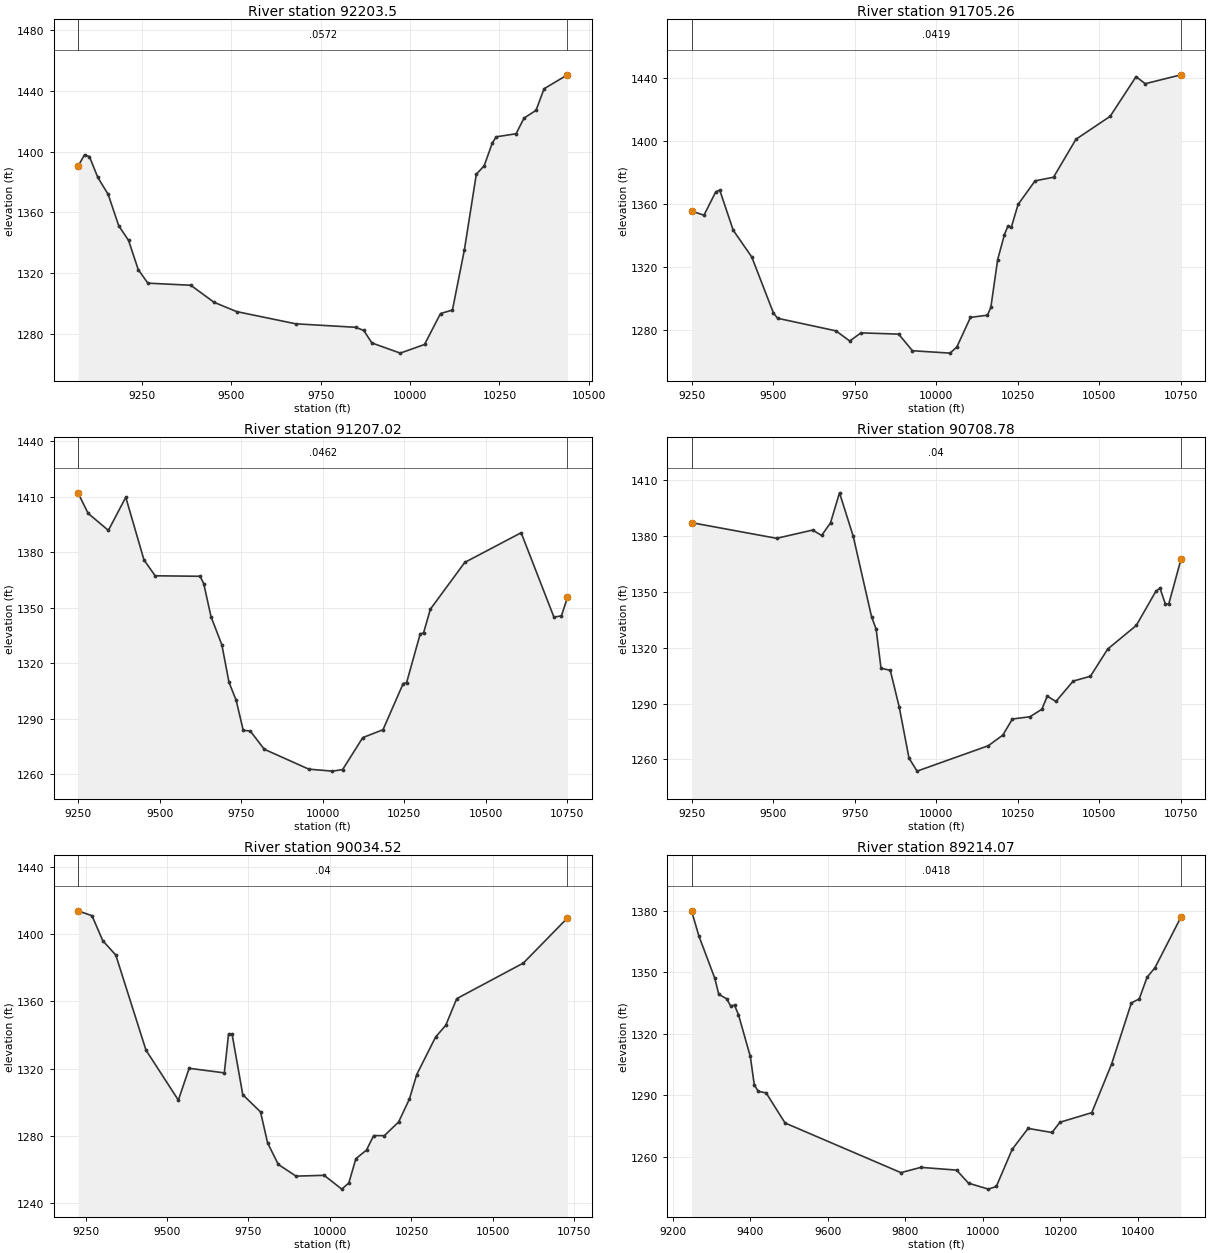
Type RM Length L Ch R = 1 , 92203.5,498.238400,498.238400,498.238400
XS GIS Cut Line= 6
 592158.15976138791756.698632497591886.089489191792002.187899103
591698.555689606792139.675052873591547.170915229792228.220464578
591362.009106545792326.948442569591016.861167945792498.154814981
#Sta/Elev= 30
9070.517 1390.29 9088.711397.9599102.535 1396.719125.987 1382.979154.9521371.824
9184.3731351.2599212.0661341.503 9239.071322.3089266.0741313.3999386.0921312.027
9451.0781300.8299514.2851294.689 9679.86 1286.649847.5631284.3469870.2441282.251
9892.9251274.0419972.3081267.33810040.251273.033   100851293.39610118.391295.712
10151.781335.26210185.171385.06110207.431390.79310229.691405.51410240.821409.734
10296.46 1411.7610318.721422.06310352.341427.16310374.841441.40310440.24 1450.55
#Mann= 3 , 0 , 0
9070.517  0.0572       09070.517  0.0572       010440.24  0.0572       0
#XS Ineff= 2 , 0
       0                               0
Bank Sta=9070.517,10440.24
Exp/Cntr=0.3,0.1

Type RM Length L Ch R = 1 ,91705.26,498.238400,498.238400,498.238400
XS GIS Cut Line= 6
591916.520535734791502.815951015591696.960169313791643.449395019
591474.247957351791750.780685495591264.704855772791826.411274246
590728.900303828791989.714393519590534.103741659792069.659019974
#Sta/Elev= 30
9249.0521355.3469287.269 1352.729323.6421367.6059335.7661368.5619376.9931343.204
 9433.921326.2469500.5991290.6399513.2641287.3819692.2131279.3939734.672 1272.96
9768.9951278.1279884.7241277.3229926.972  1266.8 10042.51265.27310063.36 1269.19
10105.091287.93310157.251289.33410167.691294.36610188.551324.58810209.421340.453
10219.85 1345.7910230.28 1344.9910251.141359.50910303.311374.50110359.971376.799
10428.711400.84710533.851415.42510613.211440.56410641.291436.08810750.971441.716
#Mann= 3 , 0 , 0
9249.052  0.0419       09249.052  0.0419       010750.97  0.0419       0
#XS Ineff= 2 , 0
       0                               0
Bank Sta=9249.052,10750.97
Exp/Cntr=0.3,0.1

Type RM Length L Ch R = 1 ,91207.02,498.238400,498.238400,498.238400
XS GIS Cut Line= 6
591769.791840449791019.295939677591551.479439714791168.382870769
591341.393236476791274.786085166591173.590958594791335.085807004
590718.619365476791462.424371691590398.923350977791605.349253115
#Sta/Elev= 30
9249.0671412.1729280.0351401.0779342.2641391.8549395.6171409.7819451.4491375.912
9485.6891367.2869623.7681367.0159634.9291362.986 9657.251345.1229690.4851329.936
9712.4021309.6499734.3191299.9539756.0921283.6449777.5611283.306  9820.51273.436
 9957.331262.64510029.951261.58410060.951262.41310122.951279.73310184.961283.985
10246.961308.99910257.371309.47310299.08  1335.8 10309.51336.42610330.351349.227
10435.93 1374.53 10608.91390.57710709.491344.92410732.481345.59610750.95 1355.57
#Mann= 3 , 0 , 0
9249.067  0.0462       09249.067  0.0462       010750.95  0.0462       0
#XS Ineff= 2 , 0
       0                               0
Bank Sta=9249.067,10750.95
Exp/Cntr=0.3,0.1

Type RM Length L Ch R = 1 ,90708.78,674.256300,674.256300,674.256300
XS GIS Cut Line= 6
591412.899562432790362.847220118591216.292783058790595.884892541
591114.747014761790705.243128514591004.085118691790816.674286843
590934.744374046790881.504469038590337.340329045791407.074228218
#Sta/Elev= 30
9249.0481387.3359510.2141378.9049621.007 1383.369648.2991380.4259675.5921387.245
9703.2171403.3689745.1541380.0959801.5281336.7389815.6211330.072 9830.581309.021
9858.9631307.9329886.3881288.2599916.3791260.7539941.1481253.70510159.541267.343
10204.371273.07410233.681281.74110287.511282.93710324.37 1287.0110340.731294.056
10367.241291.15910420.261302.12510473.291304.73210526.311319.38310613.821332.028
10673.661350.30910686.491352.15110703.351343.52210713.551343.55210750.971367.534
#Mann= 3 , 0 , 0
9249.048    0.04       09249.048    0.04       010750.97    0.04       0
#XS Ineff= 2 , 0
       0                               0
Bank Sta=9249.048,10750.97
Exp/Cntr=0.3,0.1

Type RM Length L Ch R = 1 ,90034.52,820.458800,820.458800,820.458800
XS GIS Cut Line= 6
590624.168418802789906.128906234590419.411023357790347.577814629
590218.074932655790819.609106053590151.111988113790955.290254313
590014.404881218791212.329876536589991.774730235791267.508247557
#Sta/Elev= 30
9226.8541413.9659269.7761411.0489302.902 1396.17 9342.791387.6229435.4091331.019
9534.7891301.2099567.8541320.183 9675.811317.4579688.6841340.3339699.6681340.504
9732.4611304.4669786.9231294.1939808.7081275.7379841.385 1262.939895.7481255.964
9982.1971256.437 10036.31248.21610057.941251.90610079.58 1266.3610112.241271.507
10134.121280.10210166.951280.05110210.711288.22810243.861301.86810266.16  1316.4
10324.031338.74510355.371345.80510389.03 1361.6610593.561382.86810728.791409.697
#Mann= 3 , 0 , 0
9226.854    0.04       09226.854    0.04       010728.79    0.04       0
#XS Ineff= 2 , 0
       0                               0
Bank Sta=9226.854,10728.79
Exp/Cntr=0.3,0.1

Type RM Length L Ch R = 1 ,89214.07,1400.470100,1400.470100,1400.470100
XS GIS Cut Line= 6
589689.836556176789605.977331489589653.139177796789803.260188341
589618.961028375 789969.60128647589463.765975864 790663.85926672
589445.667506022790771.518254959589442.059546735790841.934274882
#Sta/Elev= 30
9249.0091379.9579268.3581367.5189309.0441347.1069319.2161339.3029339.5591337.109
 9349.731333.6889359.9021333.9799370.0731329.3589400.5881308.994 9410.761295.272
9420.9311292.0069441.2741291.2799490.1161276.6039788.9091252.4029840.1231254.976
 9932.311253.6429963.0381247.27710014.241244.376 10034.71245.65710075.68 1263.77
 10116.71273.95810178.231271.96910198.741276.94810280.781281.62210332.051305.367
10382.89 1335.09 10403.2 1337.06 10423.41347.61510443.581352.19410510.681376.896
#Mann= 3 , 0 , 0
9249.009  0.0418       09249.009  0.0418       010510.68  0.0418       0
#XS Ineff= 2 , 0
       0                               0
Bank Sta=9249.009,10510.68
Exp/Cntr=0.3,0.1

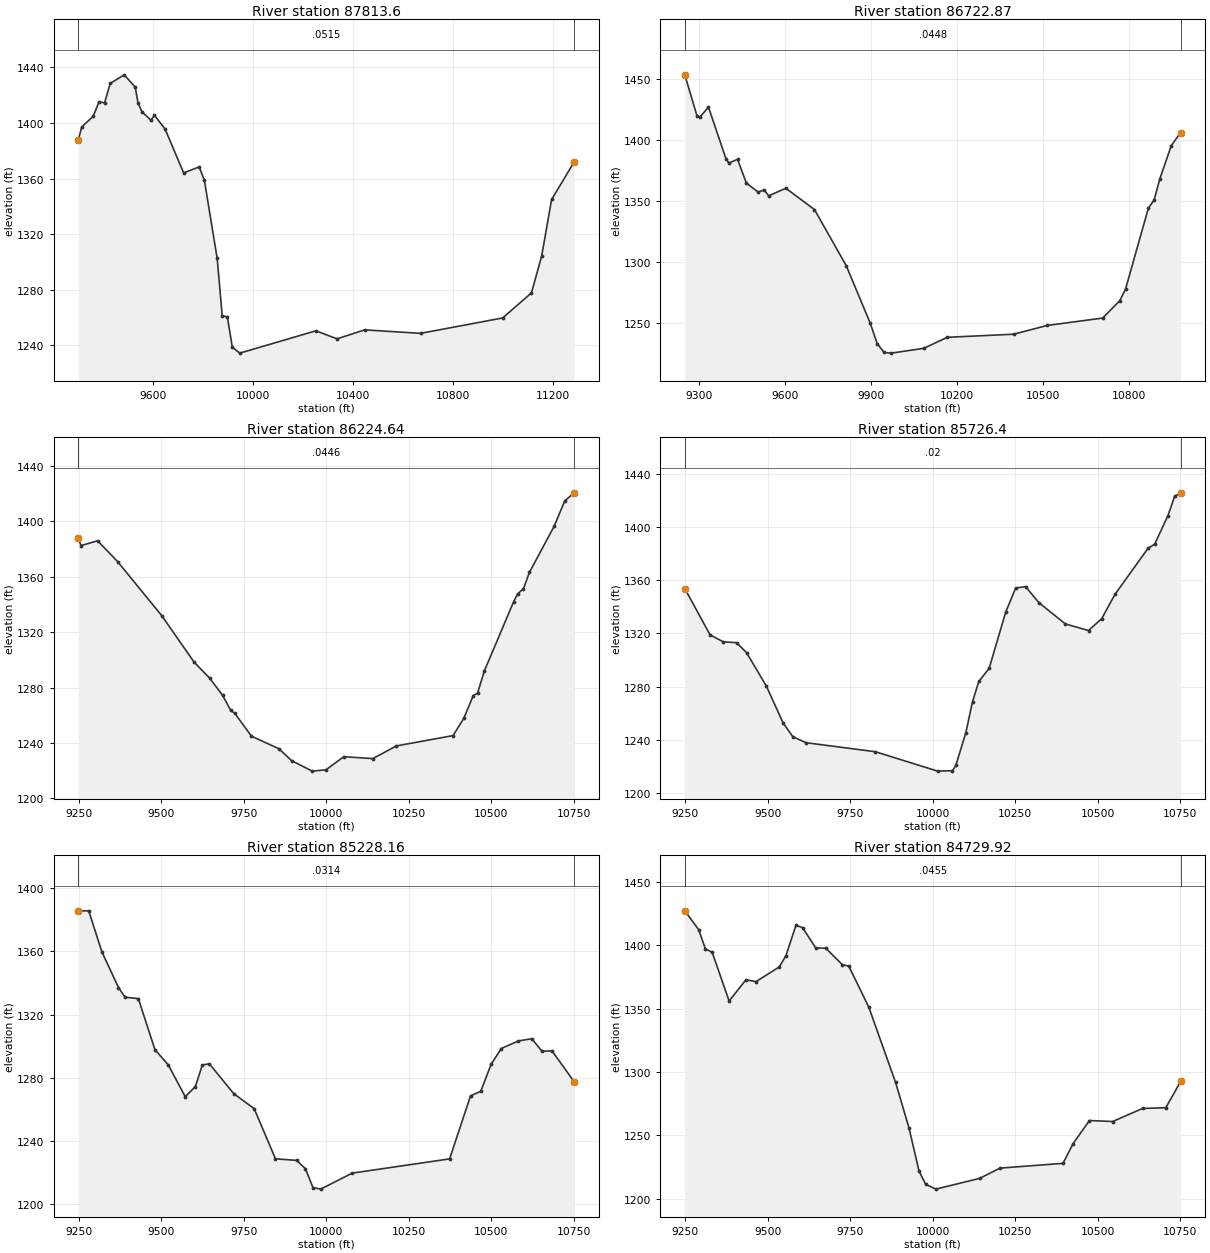
Type RM Length L Ch R = 1 , 87813.6,1090.721900,1090.721900,1090.721900
XS GIS Cut Line= 6
587553.053103626790050.285509542587812.210709453 790179.86361146
588020.043818355  790247.6751284588462.251572818790256.722911686
588856.851651549790559.897897363589313.275603354790819.185544997
#Sta/Elev= 30
9302.5761387.9669316.2871397.2229362.1951404.8469384.9581415.1849407.4481414.484
9429.937 1428.459485.8681434.6569529.7491425.797 9540.721414.6919556.3651408.134
9592.5121402.0139606.6951405.5029649.1451395.6249723.1951364.1119785.3881368.406
9806.1191358.729 9857.151302.6099877.3811261.1759897.5641260.6859917.6111238.624
9947.6821234.44910251.411250.50310335.871244.72710446.391251.18510669.721248.673
10997.49 1259.76 11112.51277.80611153.091304.14211193.011344.97411283.031372.004
#Mann= 3 , 0 , 0
9302.576  0.0515       09302.576  0.0515       011283.03  0.0515       0
#XS Ineff= 2 , 0
       0                               0
Bank Sta=9302.576,11283.03
Exp/Cntr=0.3,0.1

Type RM Length L Ch R = 1 ,86722.87,498.238300,498.238300,498.238300
XS GIS Cut Line= 6
587832.769709771791549.767451242588118.023826711791495.717540396
588347.534207858791392.000196406588582.223288399791226.355844305
588883.958938763790895.625062017589337.581158906790899.046656102
#Sta/Elev= 30
9249.081  1453.89291.5491420.2419301.6051419.0379331.8121427.3659392.608 1385.19
 9402.741381.5059433.4031384.5039464.2411365.0289505.1481357.698 9526.491359.379
9542.1521354.5589602.0861360.7989702.1961343.3139813.1561297.312 9897.041250.143
9921.4041233.3189945.7681226.1639970.1331225.61610083.811229.53710166.191238.591
10397.621241.11510515.151248.30210708.871254.35510768.871268.58910788.871278.033
10868.881344.53810888.881351.14910908.88 1368.5410948.881395.78810981.461406.496
#Mann= 3 , 0 , 0
9249.081  0.0448       09249.081  0.0448       010981.46  0.0448       0
#XS Ineff= 2 , 0
       0                               0
Bank Sta=9249.081,10981.46
Exp/Cntr=0.3,0.1

Type RM Length L Ch R = 1 ,86224.64,498.238400,498.238400,498.238400
XS GIS Cut Line= 6
 588307.09840466 791873.53491679588611.179863331791808.943635518
588778.142404889791718.668677507589218.345056155 791134.89065367
589352.190448418791013.917248491589432.929390959790988.329215935
#Sta/Elev= 30
9249.0831387.8759257.0641382.5689307.5661386.0339368.3921370.9029501.7221331.944
9599.8781298.3479646.682 1286.889686.3931274.2879710.3321263.5869722.6571261.509
9773.5791244.8759856.4761235.8279895.3471227.1689957.7091219.641    9999 1220.58
10053.261230.05610141.061228.69210212.481237.83810384.061245.31210416.481257.675
10445.341274.19610458.32 1275.9510479.191292.19310567.241341.78510579.931347.788
 10597.31351.34210615.411363.19810690.631396.65310722.451414.86910750.951420.673
#Mann= 3 , 0 , 0
9249.083  0.0446       09249.083  0.0446       010750.95  0.0446       0
#XS Ineff= 2 , 0
       0                               0
Bank Sta=9249.083,10750.95
Exp/Cntr=0.3,0.1

Type RM Length L Ch R = 1 , 85726.4,498.238400,498.238400,498.238400
XS GIS Cut Line= 6
588468.704914688791902.929638662 588819.21817047791876.597251173
589031.371078091791873.825647754589112.033903628791881.963682089
589413.864612998791933.012246623589963.073800145 791973.45726989
#Sta/Elev= 30
9249.0781353.8119325.6361318.9629365.7741313.7079405.912 1313.089436.0151305.628
9496.1551280.435 9546.261252.9979576.3231242.3619616.3841237.8299826.531 1231.05
10014.791216.45910059.871216.78310070.041220.714 10100.41245.36810120.581268.735
10139.651283.89310171.021293.84210221.351336.21810251.461354.25210281.571355.196
10321.711343.18110401.841327.17810471.951322.21810512.011331.19310552.071349.428
10652.311384.10510672.381387.18510712.611408.69410732.751423.06610750.961425.804
#Mann= 3 , 0 , 0
9249.078    0.02       09249.078    0.02       010750.96    0.02       0
#XS Ineff= 2 , 0
       0                               0
Bank Sta=9249.078,10750.96
Exp/Cntr=0.3,0.1

Type RM Length L Ch R = 1 ,85228.16,498.238400,498.238400,498.238400
XS GIS Cut Line= 6
588253.587385095 792001.81168215588528.909346742792023.843472996
588694.896542726 792075.86167616588824.706049886792167.071208813
589061.160015226792442.706309199589560.472718525792595.765968281
#Sta/Elev= 30
9249.1381385.5569280.584 1385.669320.6251359.6469370.6761337.1439390.6971331.007
9430.8781330.1279481.1351297.8589521.6141288.1599572.8821268.0669603.6961274.494
9624.698 1288.089645.9461288.9039719.8231269.9899781.6411260.5189846.2921228.761
9910.1931227.7719936.909 1222.529959.6871210.5649983.256 1209.5810078.441219.694
10373.731228.72310437.051268.58910468.111271.48410499.131288.44610530.151298.541
10581.641303.30210622.551304.75910653.24 1296.8610683.921297.01710750.891277.514
#Mann= 3 , 0 , 0
9249.138  0.0314       09249.138  0.0314       010750.89  0.0314       0
#XS Ineff= 2 , 0
       0                               0
Bank Sta=9249.138,10750.89
Exp/Cntr=0.3,0.1

Type RM Length L Ch R = 1 ,84729.92,400.708500,400.708500,400.708500
XS GIS Cut Line= 6
588054.125032262792686.550260373588277.555521798792733.774495948
588463.345923033792750.798324759588637.117868308792737.478208266
589091.225806926792653.736425976589539.411947864792686.796319734
#Sta/Elev= 30
9249.0691427.3429291.0141412.5229311.5371397.238 9332.061394.5749383.3561356.106
9434.208 1372.889464.7181371.4449535.4391383.0669555.6161392.0049585.7551415.949
9605.8091414.0599645.8441397.9699675.8661397.8769725.888 1384.919745.9011383.635
9806.2531351.3499887.395 1291.899928.0941255.9919958.6181221.6889978.9671211.315
10009.471207.56410142.621216.10210203.951224.15310394.651227.93210424.681243.293
10474.74 1261.7410545.041260.95910635.511271.27710706.121271.85810750.911292.621
#Mann= 3 , 0 , 0
9249.069  0.0455       09249.069  0.0455       010750.91  0.0455       0
#XS Ineff= 2 , 0
       0                               0
Bank Sta=9249.069,10750.91
Exp/Cntr=0.3,0.1

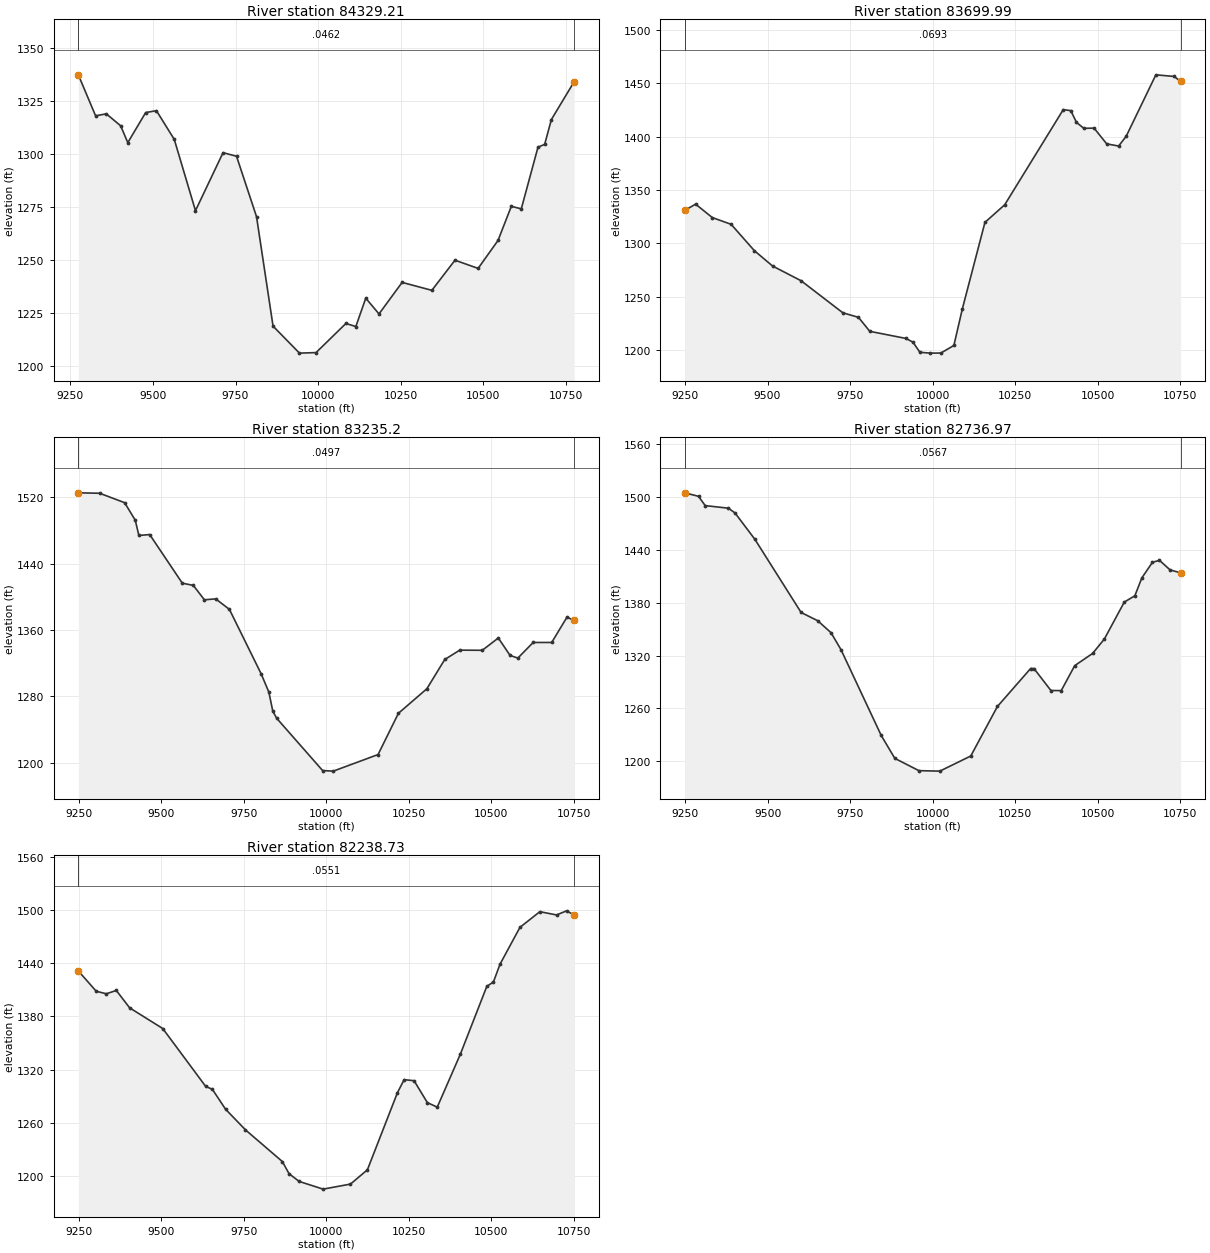
Type RM Length L Ch R = 1 ,84329.21,629.218000,629.218000,629.218000
XS GIS Cut Line= 6
588266.776581886792899.223289812588591.212060964793032.624144177
588737.548352981793070.116533743588869.484701954793075.866767549
589340.005252102 793050.99619103589732.717362682793098.163687042
#Sta/Elev= 30
9273.9331337.4939326.209 1318.129358.7311319.0449402.0931313.3959423.774 1305.43
9477.9771319.6659510.499 1320.549564.5261306.9659628.7211273.2659712.2971300.689
 9753.121298.9979813.6511270.448 9863.751218.669 9943.811205.9089993.9841206.163
10084.431219.93210114.511218.48210144.591231.89510184.681224.44310254.72 1239.35
10344.741235.594 10414.81249.84510484.911245.97110545.19 1259.1810585.411275.318
10615.66 1274.1210666.241303.27510686.481304.614 10706.81316.347 10775.81334.257
#Mann= 3 , 0 , 0
9273.933  0.0462       09273.933  0.0462       0 10775.8  0.0462       0
#XS Ineff= 2 , 0
       0                10159.35       0
Bank Sta=9273.933,10775.8
Exp/Cntr=0.3,0.1

Type RM Length L Ch R = 1 ,83699.99,464.788700,464.788700,464.788700
XS GIS Cut Line= 6
 588261.16388089793059.861050357588471.048502553793180.531392148
588622.163226418793321.980412045588805.838679474793714.960357658
588915.462019215793858.866962759589282.621487688794087.188350373
#Sta/Elev= 30
9249.3681330.9529282.1231336.7729332.632  1324.29389.7051317.8519460.1871293.098
9515.3351278.7259601.6291264.921 9728.031234.8719775.4521230.5849809.6051217.484
9919.171  1210.89940.3551207.3229961.5391197.8239993.3151197.02810025.141197.115
10064.351204.22710090.191238.75510158.431319.65610218.431336.23710395.691425.461
10418.551424.48210435.661413.47410457.86 1407.9110488.971408.104 10527.21393.329
10563.361391.29110586.331400.48310676.151458.08810731.581456.56910751.121451.889
#Mann= 3 , 0 , 0
9249.368  0.0693       09249.368  0.0693       010751.12  0.0693       0
#XS Ineff= 2 , 0
       0                               0
Bank Sta=9249.368,10751.12
Exp/Cntr=0.3,0.1

Type RM Length L Ch R = 1 , 83235.2,498.238300,498.238300,498.238300
XS GIS Cut Line= 6
587645.112011611 793257.07755908 587962.11698022793392.827344198
588335.376748673793600.316028687 588591.51946818793868.737134835
588736.522303414793969.688922232588894.480436884794056.585536829
#Sta/Elev= 30
9249.0521525.0789313.6651524.5629389.1881513.2269421.555 1492.089432.4191473.746
9465.1741474.853 9564.021416.3069597.2171413.6779630.838  1396.39665.0341397.411
9706.5971384.8099802.5481307.3929826.1351285.1739837.9331262.4449849.7311253.735
9988.9741190.72810021.331190.05510156.871210.00410218.551259.68810304.721289.231
 10358.91324.45310404.291335.70110472.511335.51710521.091350.30210556.781329.307
 10580.31326.15710626.621344.912 10682.81344.94310728.821375.22910750.81 1371.71
#Mann= 3 , 0 , 0
9249.052  0.0497       09249.052  0.0497       010750.81  0.0497       0
#XS Ineff= 2 , 0
       0                               0
Bank Sta=9249.052,10750.81
Exp/Cntr=0.3,0.1

Type RM Length L Ch R = 1 ,82736.97,498.238400,498.238400,498.238400
XS GIS Cut Line= 6
587623.839961831794133.697048911587833.058010148  794153.9548684
588046.725067905794145.918842582588585.292413973794031.663908959
588755.315287034794065.242709701589085.030881112 794185.03373524
#Sta/Elev= 30
9249.0851504.8139290.6351500.8599310.8241490.3059381.2261487.3629401.2581481.917
9461.3531452.0359601.4381368.915 9651.581359.579 9691.811346.0719722.0841326.791
9843.9961229.3099885.1771203.2749958.1541189.30810021.571188.774 10115.31205.962
10195.931262.16810296.421305.24210306.641305.29910358.051280.31710389.29 1280.21
10430.071308.57210484.33 1322.4210519.961338.84410580.271380.74310612.261387.906
10633.581408.33410665.561425.91710686.881428.15310718.861417.30110750.881413.926
#Mann= 3 , 0 , 0
9249.085  0.0567       09249.085  0.0567       010750.88  0.0567       0
#XS Ineff= 2 , 0
       0                               0
Bank Sta=9249.085,10750.88
Exp/Cntr=0.3,0.1

Type RM Length L Ch R = 1 ,82238.73,498.238400,498.238400,498.238400
XS GIS Cut Line= 6
587701.777522308794591.380990151588050.034935548794625.362381337
588261.864321222 794605.13543164588739.629059965794509.706075603
588966.660194012794510.299109122589187.630812433794538.552295541
#Sta/Elev= 30
9249.0941431.1499303.3411408.2849333.8681405.4529364.146 1409.199404.5171389.611
9504.8171366.3129634.9011301.1039654.9351297.9529695.0041275.4769755.3541252.203
9867.0151216.5319887.416  1202.8 9918.111194.1079990.6221185.462 10073.41191.146
10124.63  1207.2 10215.81294.175 10235.91308.73910266.061307.55210306.241282.875
10336.261277.78910406.311337.52510486.33 1413.7710506.361418.73910526.391438.795
10586.681480.22810647.051497.91210697.65 1494.2110728.011498.86210750.911494.094
#Mann= 3 , 0 , 0
9249.094  0.0551       09249.094  0.0551       010750.91  0.0551       0
#XS Ineff= 2 , 0
       0                               0
Bank Sta=9249.094,10750.91
Exp/Cntr=0.3,0.1