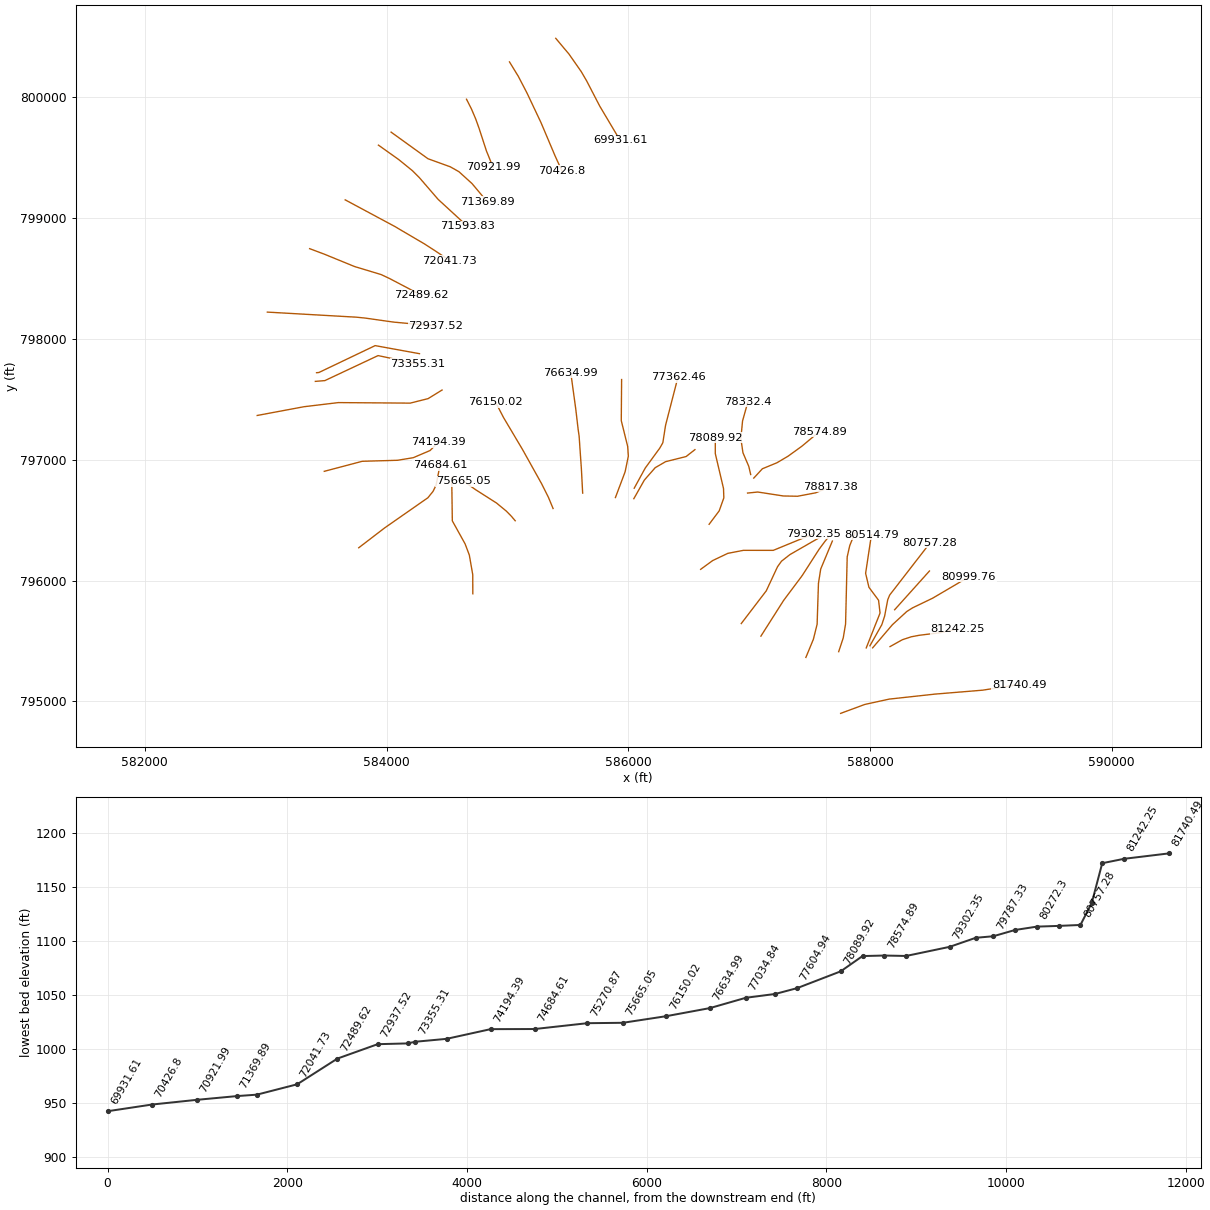
HEC-RAS study 10395_ras.prj: 10395

--- 10395_ras.g01 (geometry) --- (continued)

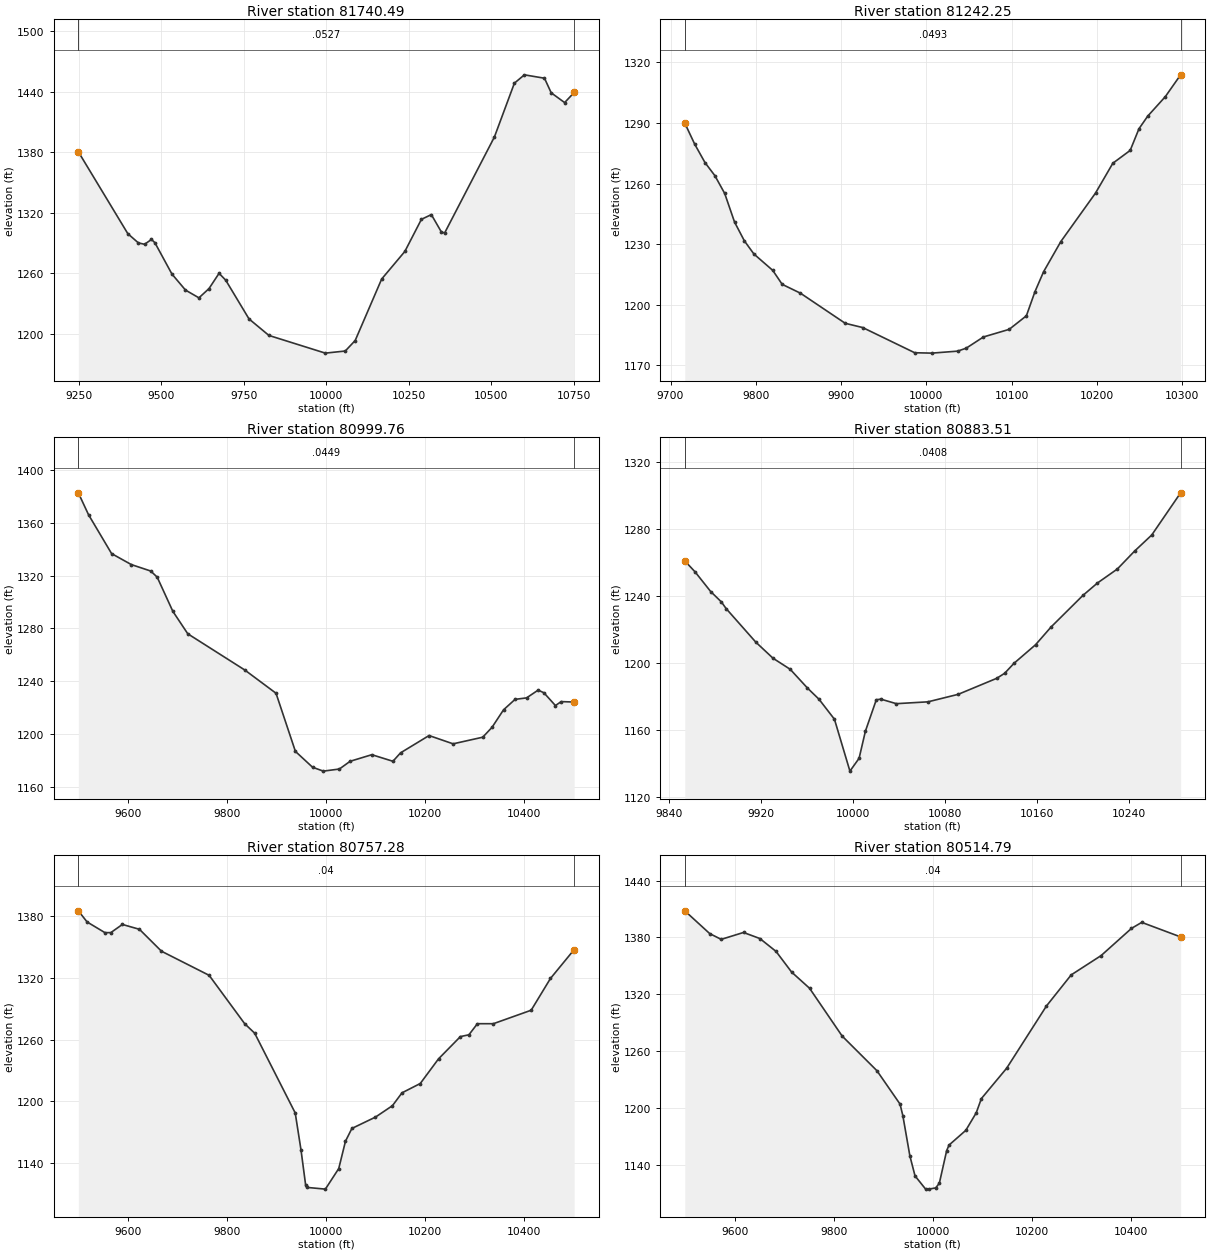
Type RM Length L Ch R = 1 ,81740.49,498.238400,498.238400,498.238400
XS GIS Cut Line= 6
587756.999782839794900.926899368587956.768341941794974.773459385
588158.821596276 795018.97876185588537.428599166795060.289941263
588930.851969223795092.821427532589233.387043045795139.387063432
#Sta/Elev= 30
9249.0781380.5799399.0761299.3669430.9851290.2689449.7791288.8949470.6681293.702
9480.9911290.4729532.6031259.4089573.6891243.5239614.374 1235.849644.8891244.998
9675.348 1260.139695.5131253.3379766.0921214.9439826.4161198.5769997.2631181.056
 10057.61183.14410087.681193.54110167.921254.48210238.121281.79910288.271313.601
10318.371318.319 10348.5 1301.2510358.551300.04710509.391395.18610569.961448.549
10600.281456.79710661.121453.42810681.451438.97310722.121429.28910750.981439.306
#Mann= 3 , 0 , 0
9249.078  0.0527       09249.078  0.0527       010750.98  0.0527       0
#XS Ineff= 2 , 0
       0                               0
Bank Sta=9249.078,10750.98
Exp/Cntr=0.3,0.1

Type RM Length L Ch R = 1 ,81242.25,242.487200,242.487200,242.487200
XS GIS Cut Line= 6
588165.491565141795453.415724821 588267.13276635795510.059511921
588340.802898061795534.366264166588407.438482721795547.016756132
 588576.74050979795567.997840482588722.423696574795598.569711706
#Sta/Elev= 30
9716.7641289.9039728.3631279.5029740.4421270.3739751.9941263.9299763.5461255.108
9775.0991240.9439786.6511231.6149797.8571225.1059819.9461217.005 9830.991210.103
9852.4421205.7139904.9361190.8189925.4311188.7159986.4231176.24910006.571176.056
10036.791177.04110046.861178.51310067.021184.05210097.261187.82610117.411194.532
10127.491206.49810137.571216.326 10157.81231.26810198.481255.26510218.821270.044
10239.161276.39510249.461287.10810259.771293.38210280.371303.00410298.321313.803
#Mann= 3 , 0 , 0
9716.764  0.0493       09716.764  0.0493       010298.32  0.0493       0
#XS Ineff= 2 , 0
       0                               0
Bank Sta=9716.764,10298.32
Exp/Cntr=0.3,0.1

Type RM Length L Ch R = 1 ,80999.76,116.257400,116.257400,116.257400
XS GIS Cut Line= 6
588021.754412981795443.024606625 588185.48705307795634.747056491
588303.910370908795743.458319571588351.516739438795773.633270208
588517.753513325 795853.67590038588817.459956049796029.881937237
#Sta/Elev= 30
9499.0731382.6469519.651  1366.1 9566.261336.6589606.1871328.3289645.3871323.452
9658.4541318.802 9689.981292.9999720.2271275.9539835.3751248.547 9898.531230.944
9937.6981186.9339972.354 1174.959994.047    117210026.531173.58710048.281179.449
10092.091184.43510134.761179.45110150.161185.83410207.761198.93310256.351192.662
10316.22 1197.6810334.921205.11510358.231218.38810381.54 1226.3110404.851227.447
10428.161233.31410439.821231.31110463.121221.62710474.781224.62310500.961224.293
#Mann= 3 , 0 , 0
9499.073  0.0449       09499.073  0.0449       010500.96  0.0449       0
#XS Ineff= 2 , 0
       0                10150.61       0
Bank Sta=9499.073,10500.96
Exp/Cntr=0.3,0.1

Type RM Length L Ch R = 1 ,80883.51,126.229800,126.229800,126.229800
XS GIS Cut Line= 2
588203.760417849795758.277757868588491.769670248796078.738756999
#Sta/Elev= 30
 9853.97 1260.829863.0081254.1749876.4531242.5329885.7451236.3359889.8981232.343
9915.6651212.3299930.6251202.7269945.5851196.1139960.5451184.9369970.5691178.272
9984.0141166.309 9997.461135.34810005.43 1143.01 10010.91159.15710020.391177.949
10024.351178.301 10037.81175.60410065.271176.70410091.581181.18210125.11 1190.76
10131.911193.73510140.071199.715 10158.8 1210.7910172.251221.36310199.911240.204
10212.581247.62810229.831255.96310244.791266.63210259.751276.27610284.831301.432
#Mann= 3 , 0 , 0
 9853.97  0.0408       0 9853.97  0.0408       010284.83  0.0408       0
#XS Ineff= 2 , 0
       0                               0
Bank Sta=9853.97,10284.83
Exp/Cntr=0.3,0.1

Type RM Length L Ch R = 1 ,80757.28,242.487200,242.487200,242.487200
XS GIS Cut Line= 6
587999.212395557795460.244826967588097.416105437795634.107638352
588120.693498226795704.910708865588146.544998795795840.863811454
588162.666498936795879.815079056588496.929719352796311.546467376
#Sta/Elev= 30
9499.148 1384.889516.8821374.0779552.9371363.7029564.8131363.7539588.1481371.662
9622.6151366.9619667.1441345.6939763.4371322.3159835.1371275.4519855.4531266.178
9937.3621188.8089949.0751152.8549958.3731119.0229960.9221116.5899998.3031114.906
10025.311134.86510038.941161.43410051.871173.77810099.431184.75310133.781195.845
10153.111208.32510190.021217.36410226.921241.28810271.141262.88810288.311264.624
10305.481275.387 10337.71275.37810414.091288.45110453.041319.25110500.951347.271
#Mann= 3 , 0 , 0
9499.148    0.04       09499.148    0.04       010500.95    0.04       0
#XS Ineff= 2 , 0
       0                               0
Bank Sta=9499.148,10500.95
Exp/Cntr=0.3,0.1

Type RM Length L Ch R = 1 ,80514.79,242.487300,242.487300,242.487300
XS GIS Cut Line= 6
587968.742782257 795442.42620563588082.972321305795730.837548025
588070.753254226795836.610067902587991.128308245795943.854034724
587963.593071515  796059.5060543588011.876330909 796378.85525513
#Sta/Elev= 30
9499.1561408.0479549.4861383.9919572.7051377.8969617.793 1385.189650.8731378.771
9683.4671365.187 9715.031343.2919751.2481326.2199817.0381275.7579887.3211239.138
    99341203.8699939.7031191.6079953.8711149.1499964.2781128.0329985.562 1114.13
9991.5481114.03610005.991115.295 10013.4 1120.2610028.241154.76810033.021160.602
10066.82 1176.1110087.951194.65810098.331209.69310149.371241.74710229.791307.514
10279.831340.37610340.27 1360.7810401.531389.46810422.321395.84810500.861380.483
#Mann= 3 , 0 , 0
9499.156    0.04       09499.156    0.04       010500.86    0.04       0
#XS Ineff= 2 , 0
       0                               0
Bank Sta=9499.156,10500.86
Exp/Cntr=0.3,0.1

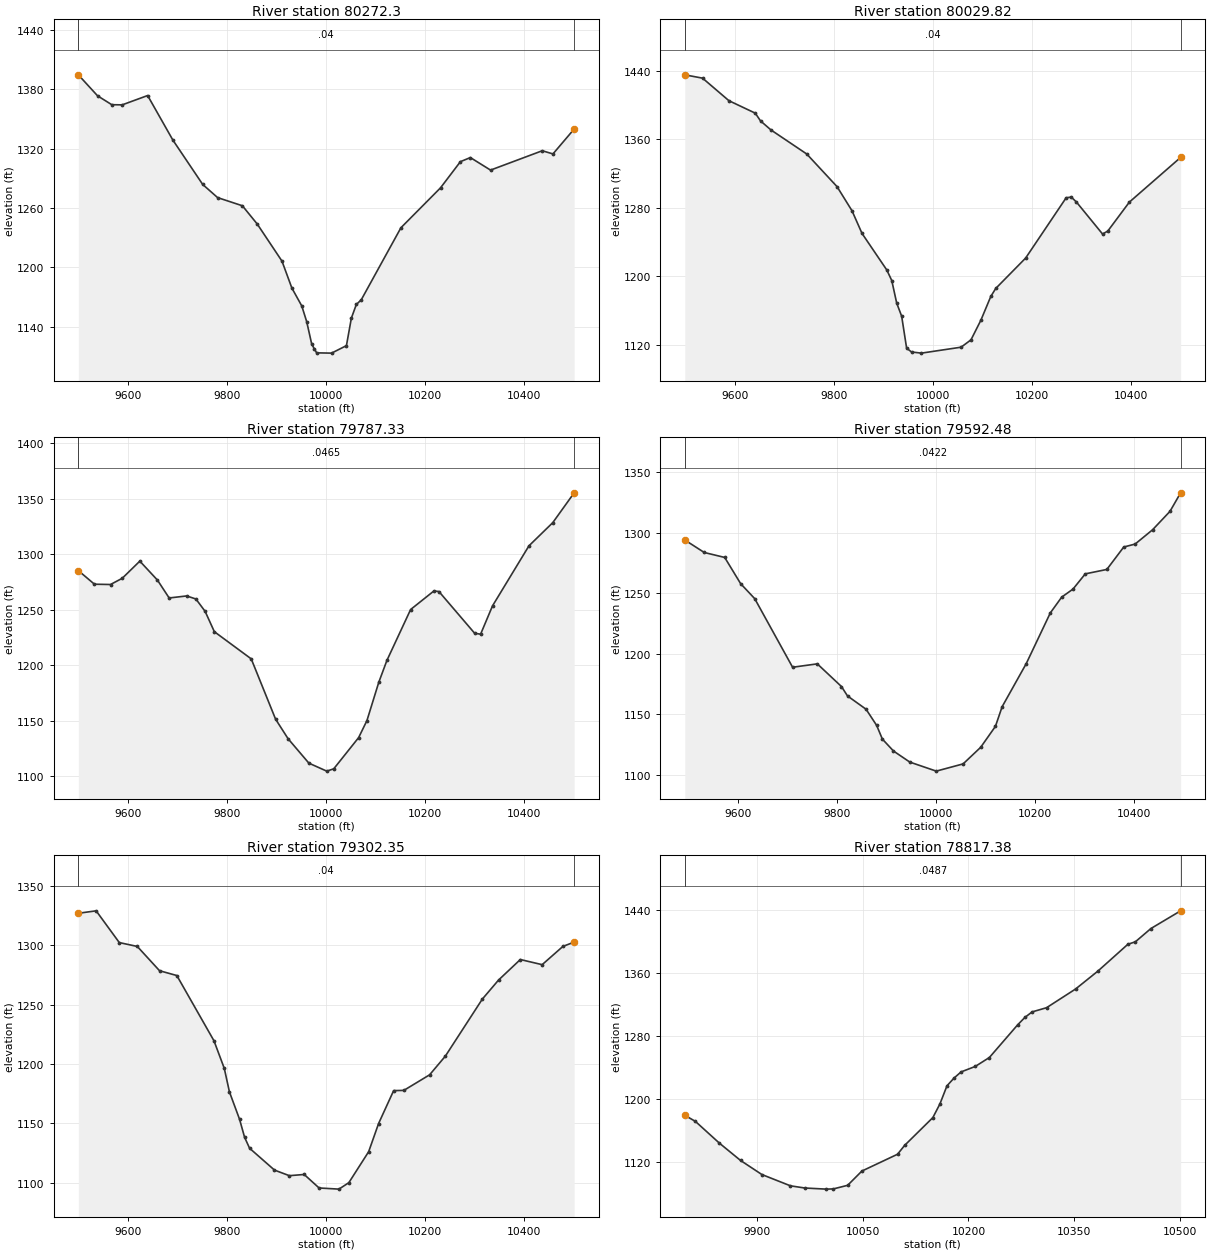
Type RM Length L Ch R = 1 , 80272.3,242.487200,242.487200,242.487200
XS GIS Cut Line= 6
587740.875784194795411.533191468587778.450175328795525.062058299
587797.779283709795640.106328534 587811.20294992796195.422099106
587832.403327601 796289.03837677587874.963737734796393.855567699
#Sta/Elev= 30
9499.0551394.551 9537.911373.3499566.6621364.3699587.6131364.2029639.0921373.624
9690.0071328.6899750.4071283.7729780.4651270.5059830.5341262.2549860.535 1243.82
9910.5371206.3369930.5371179.1069950.5381161.0579960.5391145.0759970.5591122.649
9975.692 1117.859980.5991113.64810010.711113.36110040.771120.91210050.78 1148.77
10060.791162.494 10070.81167.29410150.871240.024 10230.9 1280.3710271.091306.816
10291.211310.95810331.971298.29110436.491317.84310458.091314.63410500.93 1339.79
#Mann= 3 , 0 , 0
9499.055    0.04       09499.055    0.04       010500.93    0.04       0
#XS Ineff= 2 , 0
       0                               0
Bank Sta=9499.055,10500.93
Exp/Cntr=0.3,0.1

Type RM Length L Ch R = 1 ,80029.82,242.487200,242.487200,242.487200
XS GIS Cut Line= 6
587469.493105936795363.865696419 587531.45892254795513.991910689
587562.369897147795637.906996354587573.419332643795975.844650264
587592.053182338796094.918502393587688.634463592796326.649924232
#Sta/Elev= 30
9499.0661435.0369534.9641431.1579588.2181404.8469641.4341390.3119652.067 1381.28
9673.0851370.7419745.5081342.6279806.669 1304.569836.9571276.3459857.1361249.967
9907.2491207.2549917.2531194.9679927.2531168.5659937.2531153.3499947.2531116.056
9957.2531111.5849977.2541110.26410057.291117.18910077.311125.75910097.321148.689
10117.331176.38610127.33 1185.7410187.711221.18810269.631291.57610279.991292.361
10290.361286.59410343.14 1249.2610353.741252.72910397.34 1286.5110500.891338.647
#Mann= 3 , 0 , 0
9499.066    0.04       09499.066    0.04       010500.89    0.04       0
#XS Ineff= 2 , 0
       0                               0
Bank Sta=9499.066,10500.89
Exp/Cntr=0.3,0.1

Type RM Length L Ch R = 1 ,79787.33,194.850400,194.850400,194.850400
XS GIS Cut Line= 6
 587097.52938472795540.137375454587285.038348644795835.044829839
587439.231668924796041.363376151587578.527561601796258.191094014
587623.824889808796319.465339661587662.251530385796366.716348964
#Sta/Elev= 30
 9499.031285.2149531.5911272.9479564.0431272.6839587.7431278.2879623.2941293.749
9658.8441276.6959682.545 1260.559717.9661262.3769736.6041259.6289755.2411248.481
9773.8791230.1569848.4291205.6399897.6091151.3239922.9381133.6449964.9081111.654
   100011104.46510015.151106.53510065.471134.69310082.241150.04310106.111184.479
10122.591204.265 10170.51250.13310217.571266.86910227.711266.36610299.931228.709
10311.941227.91110335.981253.42210409.641307.55810457.781328.45510500.971355.324
#Mann= 3 , 0 , 0
 9499.03  0.0465       0 9499.03  0.0465       010500.97  0.0465       0
#XS Ineff= 2 , 0
       0                               0
Bank Sta=9499.03,10500.97
Exp/Cntr=0.3,0.1

Type RM Length L Ch R = 1 ,79592.48,290.124000,290.124000,290.124000
XS GIS Cut Line= 6
  586934.9755017795644.177672092 587141.94108281795915.139816848
587234.825791491796114.106265426587267.521619953796159.712693361
587337.549012478796214.613076116587593.337004104796361.679304517
#Sta/Elev= 30
9491.8321294.0689531.1321283.7369572.4651279.6349604.702 1257.959633.1371245.564
 9709.641188.8949759.5461191.6919808.4481172.9269820.5911165.1749858.085 1154.19
9879.5241140.809 9891.031129.5179913.4781119.6639946.5391110.4929999.9661103.041
10054.161109.01310089.691122.74410119.471140.04610132.991156.25410181.741191.905
10230.421233.82310253.411246.858 10276.21253.48410301.031266.07110344.551269.715
10378.721288.24410401.771290.71210436.961302.49210472.151317.72110493.661333.038
#Mann= 3 , 0 , 0
9491.832  0.0422       09491.832  0.0422       010493.66  0.0422       0
#XS Ineff= 2 , 0
       0                               0
Bank Sta=9491.832,10493.66
Exp/Cntr=0.3,0.1

Type RM Length L Ch R = 1 ,79302.35,484.974400,484.974400,484.974400
XS GIS Cut Line= 6
586598.861775365796092.565298499586698.331394305 796165.12417102
586823.470892099796224.700783214586952.764583692796249.705844967
587199.612478563796249.467512533587531.586499236796386.002146113
#Sta/Elev= 30
9499.1291326.7649535.116 1328.829581.8911302.1099618.2841298.8459663.2081278.427
9698.1331274.3759773.2031219.4589794.0331196.2429804.3851176.5339824.8391153.465
9835.047 1138.289845.1181129.0849895.4531110.6919925.4541105.9939955.463 1107.01
9985.5281095.65610025.621094.68110045.661100.10510085.741126.20710105.771149.881
10136.181177.55310156.771177.75510208.851190.85210240.641206.56210315.27 1254.51
 10348.1 1270.5710392.141287.84910436.241283.52810478.131298.87310500.891302.515
#Mann= 3 , 0 , 0
9499.129    0.04       09499.129    0.04       010500.89    0.04       0
#XS Ineff= 2 , 0
       0                               0
Bank Sta=9499.129,10500.89
Exp/Cntr=0.3,0.1

Type RM Length L Ch R = 1 ,78817.38,242.487200,242.487200,242.487200
XS GIS Cut Line= 6
586986.994130272796723.516827159587071.443920031 796732.09714693
587283.613178146796699.409217272587400.960673631796697.203180708
587550.292926015796725.493197459 587673.19703594796776.044829314
#Sta/Elev= 30
9797.8861179.8379812.8611172.1279846.9361144.5089876.9411122.5749907.1561104.739
9947.7181090.4169968.0451087.6449998.5021086.237 10008.61086.532 10028.81091.089
   100491109.16410099.491130.43410109.511141.614 10149.61176.917 10159.61194.196
10169.611217.16510179.611226.99910189.61 1234.7810209.621241.68710229.721253.034
10270.021294.65910280.091303.843 10290.31310.83910310.771316.14310351.951339.857
10383.511362.49710426.091396.55110436.741399.69610458.721416.48410500.881438.941
#Mann= 3 , 0 , 0
9797.886  0.0487       09797.886  0.0487       010500.88  0.0487       0
#XS Ineff= 2 , 0
       0                               0
Bank Sta=9797.886,10500.88
Exp/Cntr=0.3,0.1

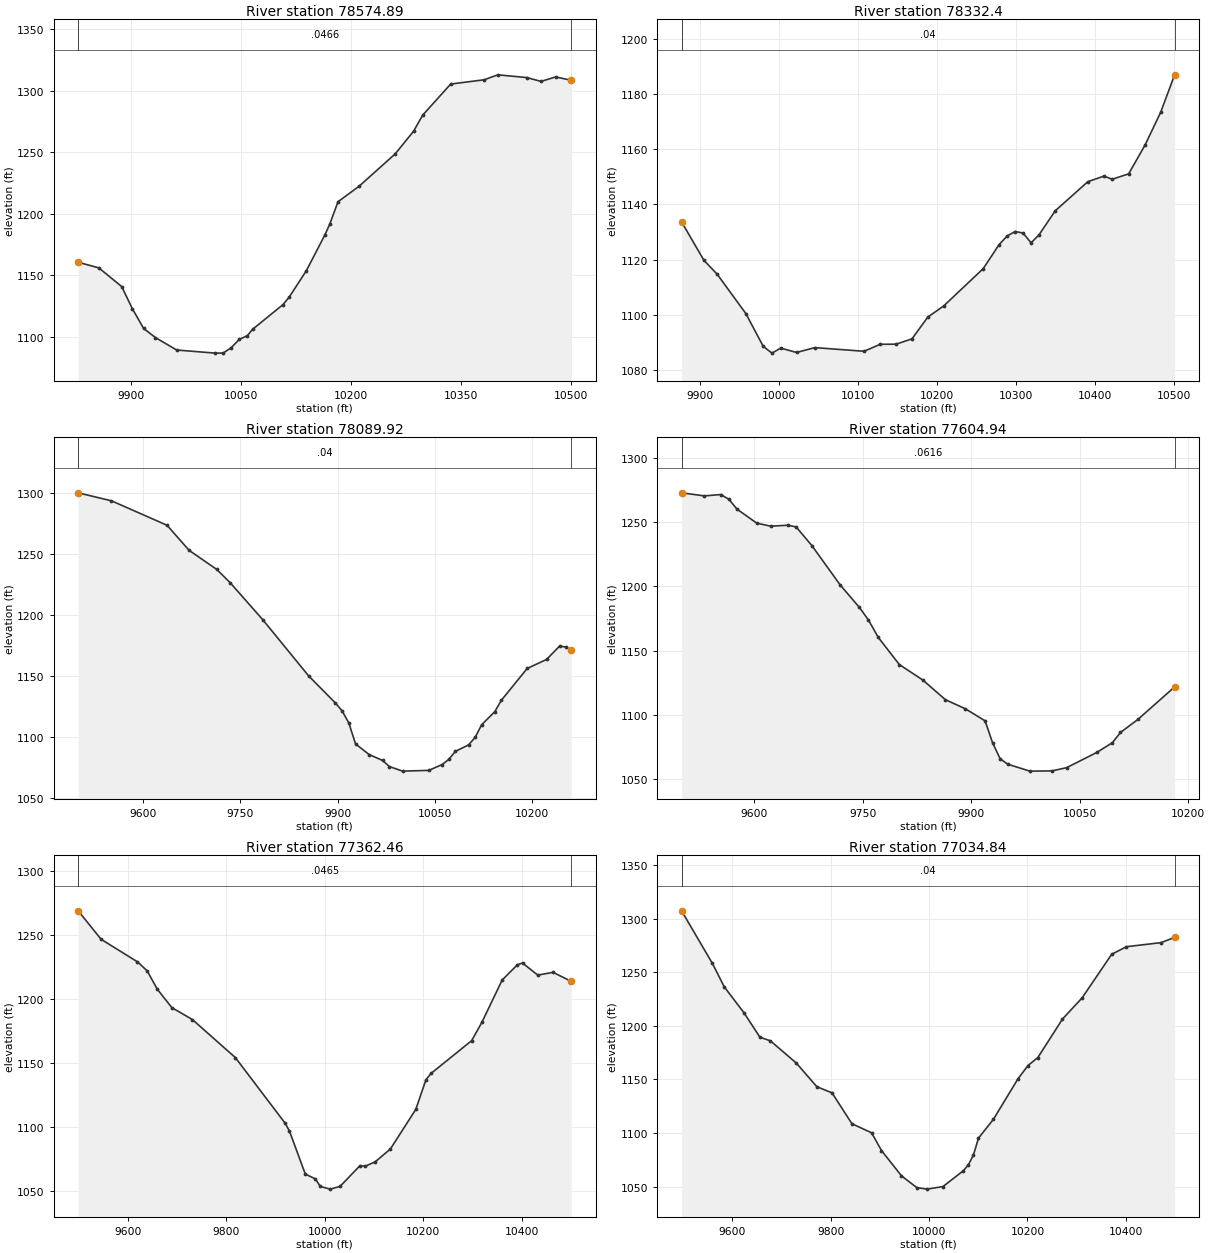
Type RM Length L Ch R = 1 ,78574.89,242.487300,242.487300,242.487300
XS GIS Cut Line= 6
587038.493577752796847.481652549587109.448906174796924.524473084
587229.175234968796973.773869591587321.942684738797028.473347288
587436.560281963797111.261153325587581.012734548797231.864021738
#Sta/Elev= 30
9828.3061160.4849856.4411155.9089887.6581140.7419902.0711122.8779917.6161106.654
9933.7671099.2689962.7121089.156 10015.5 1086.6410026.121086.70710037.081091.067
10048.041097.78510059.011100.76510066.131105.94210107.691126.06510115.961131.986
10139.54 1153.5710164.771182.60810171.321191.17110182.791209.65310211.531222.258
10260.741248.50810285.761266.86110298.271279.99310336.461305.27510382.261308.755
10400.781312.77810440.181310.549 10459.81307.449 10479.81311.07610500.941308.319
#Mann= 3 , 0 , 0
9828.306  0.0466       09828.306  0.0466       010500.94  0.0466       0
#XS Ineff= 2 , 0
       0                               0
Bank Sta=9828.306,10500.94
Exp/Cntr=0.3,0.1

Type RM Length L Ch R = 1 , 78332.4,242.487200,242.487200,242.487200
XS GIS Cut Line= 6
587012.719694306796877.031187678586997.384606623796943.392879604
586948.832772684797057.106810961586931.409641537797174.787173649
586945.592474485797320.183217021586990.384875472797480.377524884
#Sta/Elev= 30
9876.5261133.6439904.7941119.7379921.5791114.7019957.878 1100.479979.9521088.585
9990.9891086.14910002.031087.96910022.031086.39210045.281088.14110107.64 1086.82
10128.071089.349 10148.2 1089.3910168.281091.316 10188.31099.202 10208.31103.192
 10258.41116.709 10278.61125.41910288.711128.53110298.831130.16310308.941129.606
10319.061126.06310329.171128.97510349.681137.66410390.881148.18210411.481150.216
10421.781149.06510442.681151.03610463.691161.61810483.271173.37610500.851186.863
#Mann= 3 , 0 , 0
9876.526    0.04       09876.526    0.04       010500.85    0.04       0
#XS Ineff= 2 , 0
       0                               0
Bank Sta=9876.526,10500.85
Exp/Cntr=0.3,0.1

Type RM Length L Ch R = 1 ,78089.92,484.974400,484.974400,484.974400
XS GIS Cut Line= 6
586668.938023234796465.304652202 586752.49340591 796576.72591708
  586790.6629778796683.615282559586787.993789128796761.383408636
 586720.05154089797050.024323187586720.107641195797182.923592479
#Sta/Elev= 30
9499.1321299.9839550.597 1293.439636.5281273.4069670.5561252.8669713.3221237.236
9733.978  1226.49784.2641196.1759855.1241150.1549896.4331127.9929906.9031121.492
9917.3731111.5769927.8431094.3089948.7831085.6269969.7231080.7449980.193 1075.77
10000.521072.02710041.141072.63710061.64 1077.4410071.891081.60110082.141088.213
10102.51 1093.5110112.671099.63910122.831110.10810142.961120.62510152.991129.907
 10193.11156.10110223.131163.51410243.141174.38610253.211173.73410261.221170.886
#Mann= 3 , 0 , 0
9499.132    0.04       09499.132    0.04       010261.22    0.04       0
#XS Ineff= 2 , 0
       0                               0
Bank Sta=9499.132,10261.22
Exp/Cntr=0.3,0.1

Type RM Length L Ch R = 1 ,77604.94,242.487200,242.487200,242.487200
XS GIS Cut Line= 6
586046.005124986796676.969466008586133.385488719796831.256871673
586222.937247134796933.460870499 586308.46923425 796983.02375468
586478.555913794797025.733715737586551.358866118797082.708001772
#Sta/Elev= 30
9499.1591272.7459530.7211270.3669553.2411271.4119564.501 1267.779575.7611260.113
9603.1141249.1849622.2551246.8459645.7941247.5359657.522 1246.319679.3731231.734
 9718.671201.0689744.9471183.811 9757.531174.0339771.1831160.4289800.4141139.281
9832.7871127.3099864.0971111.9989891.5691104.9789918.9581095.574 9929.36 1078.46
9939.7621066.1389950.1641061.8949980.8791056.50410011.43 1056.6810031.821059.193
10073.521071.04310095.011078.566 10106.21086.52110130.241096.63510181.141121.945
#Mann= 3 , 0 , 0
9499.159  0.0616       09499.159  0.0616       010181.14  0.0616       0
#XS Ineff= 2 , 0
       0                               0
Bank Sta=9499.159,10181.14
Exp/Cntr=0.3,0.1

Type RM Length L Ch R = 1 ,77362.46,327.611400,327.611400,327.611400
XS GIS Cut Line= 6
586049.137122539 796763.55014852586140.603321513796930.541822169
586260.894797284797095.647754515586286.149959607797140.001305864
586308.681696398797284.628920133586410.890590388797680.850463272
#Sta/Elev= 30
9499.1411268.9839545.8281246.6679619.6181229.0559639.2781222.0149659.9461207.582
9689.6131193.148 9731.261183.8639818.5651154.0839919.7511102.6839928.4291096.572
9960.6221062.9089981.0181059.1819991.0651053.25610011.151051.13910031.231053.277
10071.811069.54310081.981069.01910102.481072.47710133.471082.535 10185.11113.535
10205.761136.73510216.091141.708 10298.71167.38710319.361181.64810360.67 1214.84
10391.651226.78410401.981228.15210432.961218.65110463.941220.84710500.971213.768
#Mann= 3 , 0 , 0
9499.141  0.0465       09499.141  0.0465       010500.97  0.0465       0
#XS Ineff= 2 , 0
       0                               0
Bank Sta=9499.141,10500.97
Exp/Cntr=0.3,0.1

Type RM Length L Ch R = 1 ,77034.84,399.850300,399.850300,399.850300
XS GIS Cut Line= 6
585893.797178024796686.542077004585974.001205024 796899.25654869
586000.613715275797028.906993678585995.162453022797109.092071574
585942.243179118797322.417017134585944.977956849797662.760063112
#Sta/Elev= 30
  9497.21307.4359559.8591258.2819583.8731236.4899624.1711212.1159656.327 1189.44
9677.664 1186.069730.508 1165.219771.9781143.2219802.8531137.5069843.2821108.675
9883.3421100.163 9903.361083.6429943.8791060.0769975.0611049.022 9996.371047.593
 10028.41049.99710069.93 1064.8410080.111070.458 10090.31079.53110100.49 1095.23
10130.811112.77510181.031150.81310201.071162.993 10221.11170.44710271.111206.364
10311.121226.21510371.131266.87210401.151273.93910471.241277.71910499.031282.615
#Mann= 3 , 0 , 0
  9497.2    0.04       0  9497.2    0.04       010499.03    0.04       0
#XS Ineff= 2 , 0
       0                               0
Bank Sta=9497.2,10499.03
Exp/Cntr=0.3,0.1

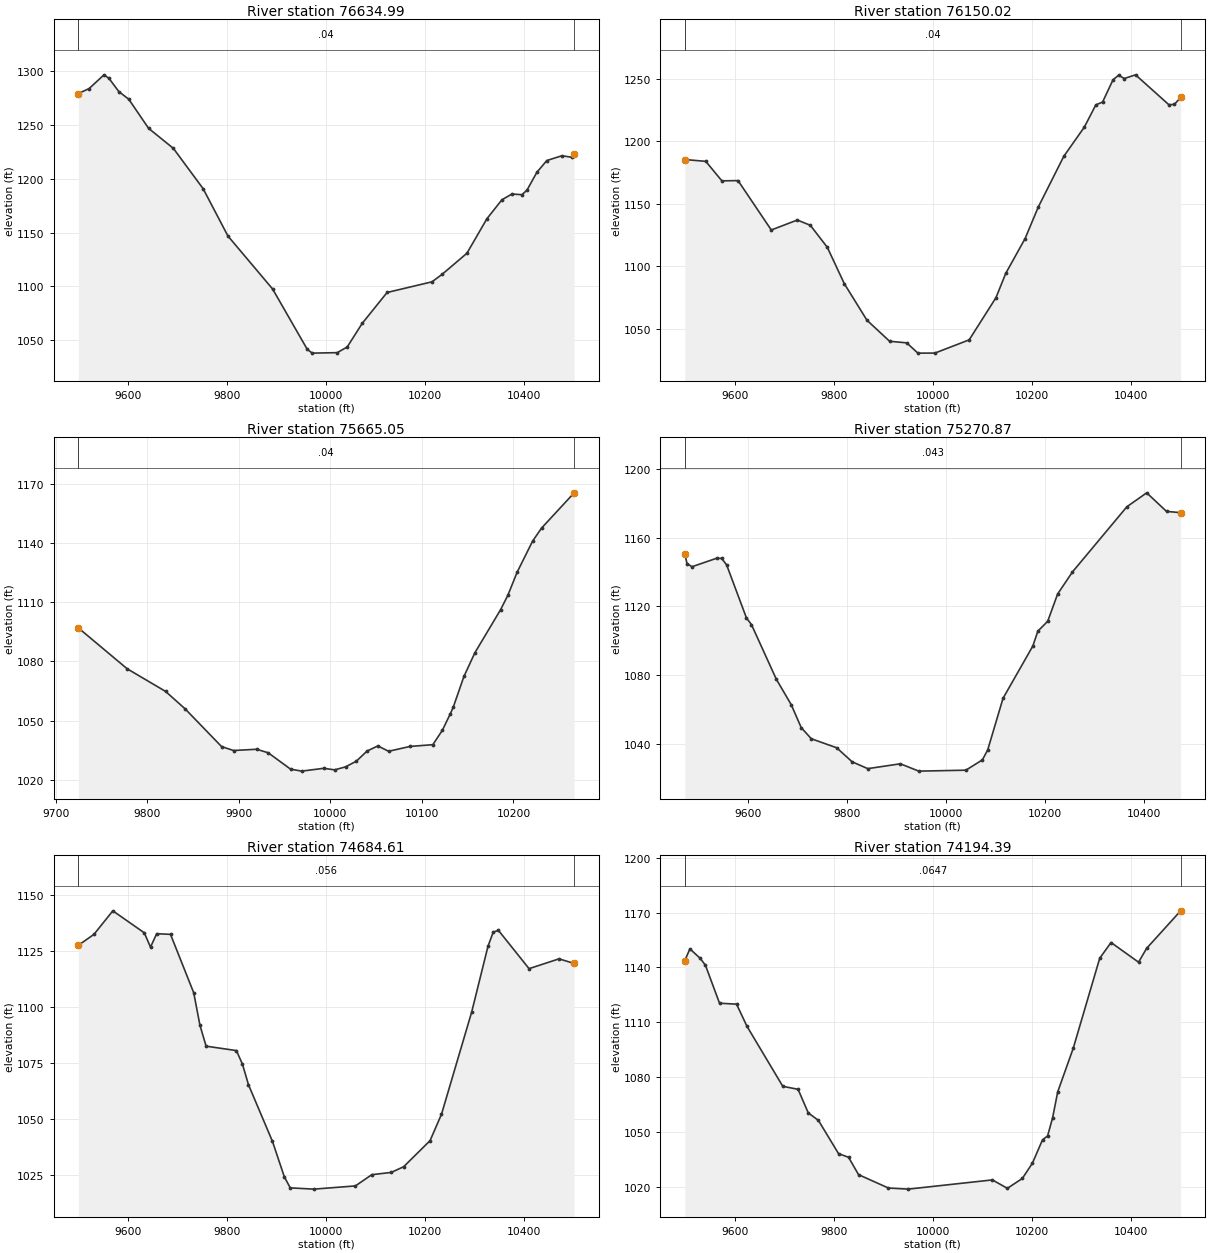
Type RM Length L Ch R = 1 ,76634.99,484.974400,484.974400,484.974400
XS GIS Cut Line= 6
 585622.79233838796723.208052086585612.274704259  796923.0382305
585593.261095345797197.099386804585585.905251146797246.575660045
585565.524598704797419.949303101 585524.32156635797719.679538821
#Sta/Elev= 30
 9499.021279.0359520.8421283.7089550.8841296.4459560.898 1293.189580.9261280.848
9600.9531273.7959641.0091246.7629691.0781228.1659751.2141190.7389801.3341146.785
 9891.551097.6469961.7191041.5349971.7431038.06210022.28  1038.510042.421043.805
10072.631065.66610122.971094.37710213.63 1104.2510233.821111.08310284.291130.797
10324.661162.82910354.951180.40510375.131185.75910395.321185.17510405.421189.173
10425.611205.92310445.79 1216.8810476.081221.30610496.261219.92610500.991223.397
#Mann= 3 , 0 , 0
 9499.02    0.04       0 9499.02    0.04       010500.99    0.04       0
#XS Ineff= 2 , 0
       0                               0
Bank Sta=9499.02,10500.99
Exp/Cntr=0.3,0.1

Type RM Length L Ch R = 1 ,76150.02,484.974400,484.974400,484.974400
XS GIS Cut Line= 6
585377.997111841796595.870084315585339.118586315796689.097858421
585282.453045881796801.979182343585124.779760329 797084.63667232
  584968.2416695797348.165590495584901.807984955797476.382536211
#Sta/Elev= 30
9499.044 1185.519541.4411184.0579573.9451168.4539606.6581168.6499673.794 1129.12
 9726.36  1137.19752.6971132.8989787.0191115.2699821.3411086.1879867.104 1056.94
9912.8671040.0899947.5521038.807 9970.071030.58910004.421030.63210073.711041.206
10127.911075.019 10147.51094.34310186.661122.24910213.281147.45610264.981188.147
10306.331211.40810329.591229.232 10343.31231.53410364.321249.27210375.711252.991
 10387.11250.33810409.881253.29910477.171229.393 10488.31229.60310500.981235.192
#Mann= 3 , 0 , 0
9499.044    0.04       09499.044    0.04       010500.98    0.04       0
#XS Ineff= 2 , 0
       0                               0
Bank Sta=9499.044,10500.98
Exp/Cntr=0.3,0.1

Type RM Length L Ch R = 1 ,75665.05,394.173300,394.173300,394.173300
XS GIS Cut Line= 6
585064.569044776796494.608583768585032.928933209796531.802926915
 584991.69109105 796573.83679046584910.620849067796640.800157484
584735.180724542 796752.74798856584636.427175849796821.995575099
#Sta/Elev= 30
9724.6621096.9949777.9721076.2979819.9991064.8199841.2761056.0149881.1711036.882
9894.2281034.8949919.4491035.527 9932.061033.7549956.5721025.4499968.7291024.451
9992.8271025.88310004.721025.09210016.621026.61110028.381029.48510040.141034.624
 10051.91037.21810063.651034.50210087.171036.96410111.991037.84310122.441045.178
10131.011053.419 10134.21056.71210145.96  1072.410157.951084.42110186.041106.238
10193.941113.48510204.141125.239   102211140.94610230.85 1147.5810266.391165.386
#Mann= 3 , 0 , 0
9724.662    0.04       09724.662    0.04       010266.39    0.04       0
#XS Ineff= 2 , 0
       0                               0
Bank Sta=9724.662,10266.39
Exp/Cntr=0.3,0.1

Type RM Length L Ch R = 1 ,75270.87,586.262600,586.262600,586.262600
XS GIS Cut Line= 6
584714.044925852795890.461605853584713.506419316796047.891321856
584685.132858479796210.749619249584650.100749058796303.361810213
584544.465010086796493.710362745584539.468065803796853.516083726
#Sta/Elev= 30
9472.2261150.5179476.7661144.9479486.7691143.1229536.7861148.0829546.7891147.967
9556.7931144.1519596.8311113.2689606.842 1109.479657.0621077.6549687.2761062.769
 9707.441049.4319727.7891042.9429779.0791037.6979810.3041029.5249841.8741025.537
9907.8341028.3619944.9041024.08910040.151024.63910073.561030.66810084.231036.468
10115.211066.51710175.461096.97910185.461105.57110205.461111.36310225.461127.234
10255.46 1140.0910365.461178.06210405.461186.15610445.461175.34110473.98 1174.61
#Mann= 3 , 0 , 0
9472.226   0.043       09472.226   0.043       010473.98   0.043       0
#XS Ineff= 2 , 0
       0                               0
Bank Sta=9472.226,10473.98
Exp/Cntr=0.3,0.1

Type RM Length L Ch R = 1 ,74684.61,490.218000,490.218000,490.218000
XS GIS Cut Line= 6
583770.145823458796270.932106735583984.309321714796435.003306944
584342.425842786  796684.6920488584384.916115273796737.360462152
584410.147719642796788.673891803584442.659541125 796955.23755825
#Sta/Elev= 30
9499.0141127.426  9530.61132.3189568.7261142.8119632.2691133.0119644.8551126.622
9657.3381132.6169685.2761132.3159732.2341106.2329744.7171091.816  9757.21082.448
9818.4371080.483 9830.631074.4359842.8241065.261 9891.33 1039.969915.2731024.182
9927.2451019.2559975.1311018.69210058.881020.12510092.011025.138 10131.31026.143
10156.351028.67510209.711040.30710232.851052.084 10293.81097.63310326.841127.023
10337.48 1133.3610347.991134.07810409.771117.02110470.381121.39410500.931119.337
#Mann= 3 , 0 , 0
9499.014   0.056       09499.014   0.056       010500.93   0.056       0
#XS Ineff= 2 , 0
       0                               0
Bank Sta=9499.014,10500.93
Exp/Cntr=0.3,0.1

Type RM Length L Ch R = 1 ,74194.39,490.217900,490.217900,490.217900
XS GIS Cut Line= 6
 583485.24304641796903.401147302583799.360447376796986.346308008
584091.033025729796994.705432021584221.329278019797016.193185321
584359.923024925797075.180420042584430.920452814  797145.9176524
#Sta/Elev= 30
9499.047 1143.739509.3031150.2049530.3241144.9929540.8341141.1829569.2021120.437
9603.6931119.9129624.5181107.8619697.0631074.9099727.942 1073.269748.5271060.338
9768.9741056.2599809.6681038.0359829.9611036.0239850.1191026.5079910.4331019.192
9950.471 1018.58 10120.61023.63310150.831019.01310181.051024.42610201.411032.779
10221.871045.60510232.091047.69610242.321057.76810252.631071.922   102841095.817
10337.431145.05910360.331153.68210415.961142.90510432.11 1150.4610500.921171.048
#Mann= 3 , 0 , 0
9499.047  0.0647       09499.047  0.0647       010500.92  0.0647       0
#XS Ineff= 2 , 0
       0                               0
Bank Sta=9499.047,10500.92
Exp/Cntr=0.3,0.1

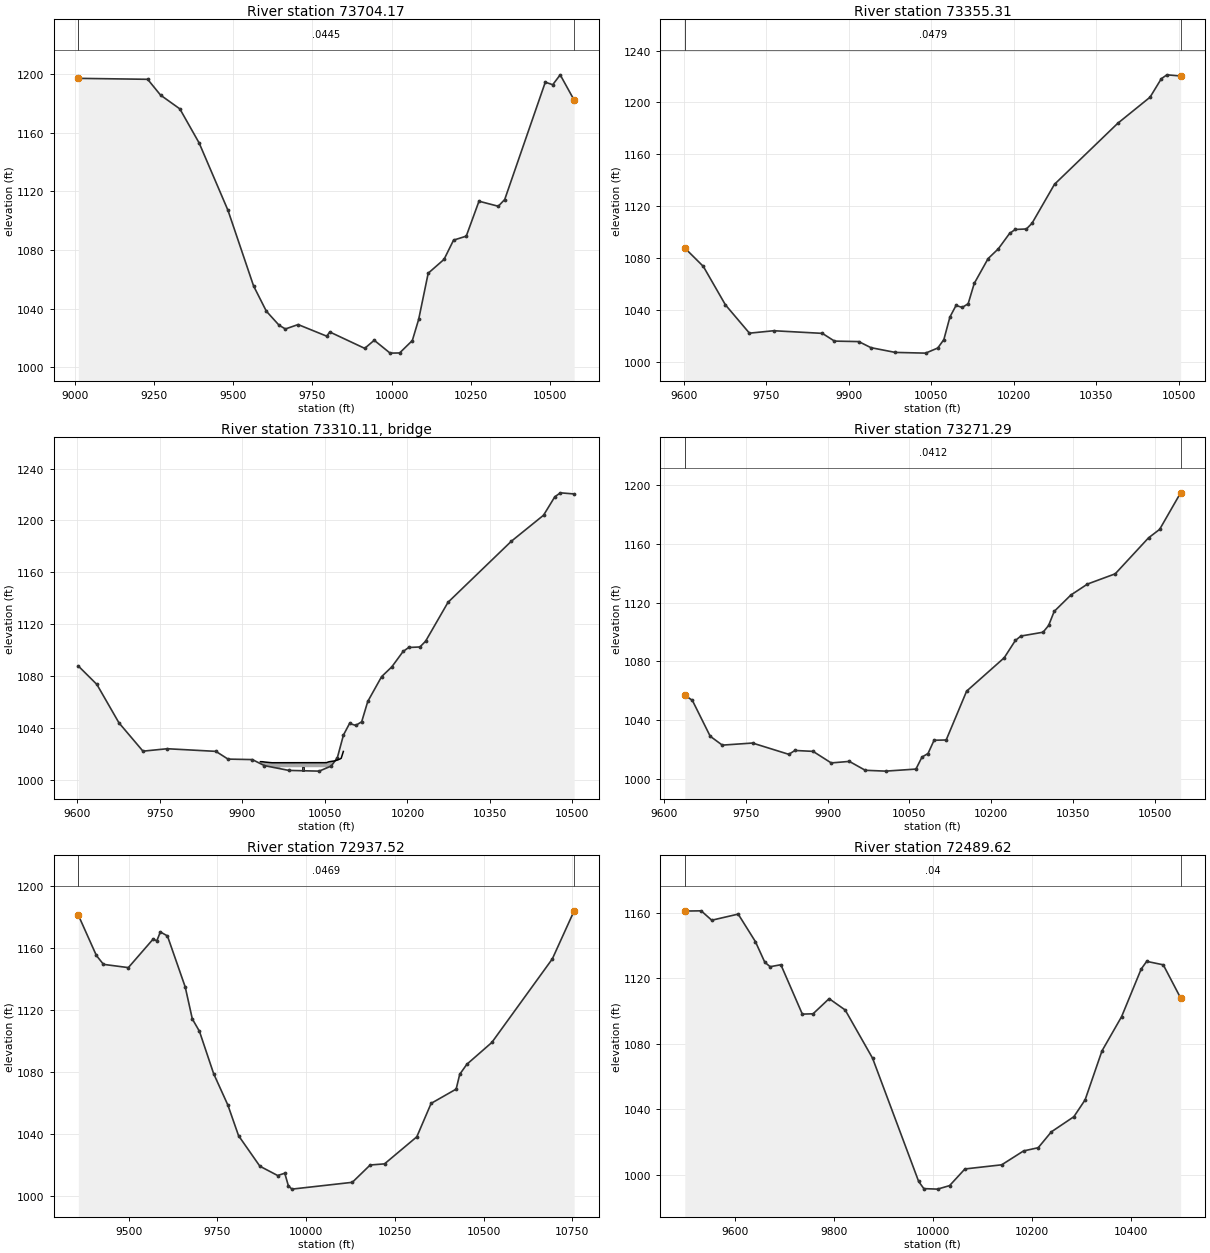
Type RM Length L Ch R = 1 ,73704.17,348.867100,348.867100,348.867100
XS GIS Cut Line= 6
582930.329294278797365.459207578583317.345091993797437.838220364
583601.790632192797471.980207773584196.165142295797467.592805338
584344.274581628797504.874912223584459.453209665797575.948403119
#Sta/Elev= 30
9011.3051196.9889230.0771196.3389270.7981185.5649331.6881176.1659392.5441152.916
9483.5651106.9719564.2491055.467 9604.521038.2349644.6721028.6569664.7481026.092
9704.8641029.0929794.9241021.1949804.924 1024.029914.9951012.862 9945.061018.381
9995.163 1009.6110025.221009.734 10065.31018.19310085.341032.68410115.351064.097
10165.351073.54610195.371086.65910235.43 1089.3810275.621113.20910336.471109.771
 10356.81114.36410484.911194.387 10508.31192.63910531.921199.39210575.961182.152
#Mann= 3 , 0 , 0
9011.305  0.0445       09011.305  0.0445       010575.96  0.0445       0
#XS Ineff= 2 , 0
       0                               0
Bank Sta=9011.305,10575.96
Exp/Cntr=0.3,0.1

Type RM Length L Ch R = 1 ,73355.31,84.015300,84.015300,84.015300
XS GIS Cut Line= 4
583411.388522565797647.546433359583489.983506709797653.903380588
583930.261284441797860.847825035584259.427951127797791.403380573
#Sta/Elev= 30
9601.5211087.8899635.2421073.7129675.3731044.1399719.0641022.3059763.2621024.176
9851.6591022.1519873.7581016.1919917.9561015.8159940.0551011.1419984.254 1007.48
 10039.51006.927 10061.61010.86910072.651017.337 10083.71034.75210094.751043.614
 10106.1 1042.1410116.851044.952 10127.91060.60310153.111079.728 10171.71087.264
10192.141099.09210202.361102.165 10222.81102.56910233.021106.963 10273.91136.992
10388.961183.96910447.651204.05910468.091218.25610478.31 1221.2910503.27 1220.42
#Mann= 3 , 0 , 0
9601.521  0.0479       09601.521  0.0479       010503.27  0.0479       0
#XS Ineff= 2 , 0
       0                               0
Bank Sta=9601.521,10503.27
Exp/Cntr=0.3,0.1

Type RM Length L Ch R = 3 ,73310.11,,,
BEGIN DESCRIPTION:
END DESCRIPTION:
Bridge Culvert--1,0,-1,-1, 0
Deck Dist Width WeirC Skew NumUp NumDn MinLoCord MaxHiCord MaxSubmerge Is_Ogee
27.257650,29.500000,2.6,0, 16, 16, , , 0.95, 0, 0,0,,
 9932.65 9936.23 9940.66 9950.95 9954.07 9968.95 9968.9510051.4510051.4510052.86
10053.5510057.4610068.5210076.9010079.5910083.51
 1014.21 1014.18 1013.93 1013.49 1013.39 1013.40 1013.40 1013.44 1013.44 1013.44
 1013.59 1014.14 1014.87 1016.18 1016.82 1022.09
   14.21   14.18   13.93   13.49   13.39   13.40 1009.90 1009.94   13.44   13.44
   13.59   14.14   14.87   16.18   16.82   22.09
 9932.65 9936.23 9940.66 9950.95 9954.07 9959.27 9959.2710041.7710041.7710052.86
10053.5510057.4610068.5210076.9010079.5910083.51
 1014.21 1014.18 1013.93 1013.49 1013.39 1013.39 1013.39 1013.44 1013.44 1013.44
 1013.59 1014.14 1014.87 1016.18 1016.82 1022.09
   14.21   14.18   13.93   13.49   13.39   13.39 1009.89 1009.94   13.44   13.44
   13.59   14.14   14.87   16.18   16.82   22.09
Pier Skew, UpSta & Num, DnSta & Num=  ,10010.20, 2 ,10000.52, 2 , 0 , 0 , 0 ,,
    4.00    4.00
   13.42 1013.42
    4.00    4.00
   13.41 1013.41
BR Coef=-1 , 0 , 0 ,, 0 ,,,0.8,0,1,0,
WSPro=,,,, 1 ,,,, 0 ,,,, 0 ,,,,-1 ,-1 ,-1 , 0 , 0 , 0 , 0 , 0
BC Design=,, 0 ,, 0 ,,,,,,

Type RM Length L Ch R = 1 ,73271.29,333.771600,333.771600,333.771600
XS GIS Cut Line= 4
 583421.20956704797719.099757478 583440.88677007 797721.07266967
583906.164547861797943.294891879584272.831214517797876.628225207
#Sta/Elev= 30
9638.5691057.0889652.4281053.5119685.067 1029.149707.2311023.0779762.6411024.498
9829.1331016.8129840.2151019.4499873.4611018.8369906.7071010.9769939.9541012.013
9969.0961005.96110006.451005.39410061.861006.78610072.941014.93910084.021017.383
 10095.11026.39510117.271026.57710154.721059.814 10223.61082.51610243.931094.255
10254.091097.28110294.751099.88410304.911104.50710315.081114.04410345.571125.161
10376.061132.64410426.881139.61110487.871164.08110508.191169.83410546.641194.698
#Mann= 3 , 0 , 0
9638.569  0.0412       09638.569  0.0412       010546.64  0.0412       0
#XS Ineff= 2 , 0
       0                               0
Bank Sta=9638.569,10546.64
Exp/Cntr=0.3,0.1

Type RM Length L Ch R = 1 ,72937.52,447.895400,447.895400,447.895400
XS GIS Cut Line= 6
583014.190441091 798220.60002692 583753.07176397798178.452849748
583825.916133098798170.897724038584059.257443351798137.773047814
584338.062665208798112.337292573584406.443192067798109.659688504
#Sta/Elev= 30
 9357.881181.0979408.7251155.1479428.7481149.4099498.855 1147.329568.9631165.755
9578.9781164.4879588.9931170.2849609.0241167.7219659.1221134.8649679.1641114.247
9699.2071106.3219739.2931078.9919779.3781058.7999809.4421039.0989869.5711019.431
9919.6771013.445 9939.721014.9149949.7331006.9229959.745 1004.6810130.091009.065
10180.411020.21710220.861020.94610311.871038.37810352.211059.89510422.751069.092
 10432.81078.61910452.911085.07110523.291099.11310693.841152.94810755.331183.882
#Mann= 3 , 0 , 0
 9357.88  0.0469       0 9357.88  0.0469       010755.33  0.0469       0
#XS Ineff= 2 , 0
       0                               0
Bank Sta=9357.88,10755.33
Exp/Cntr=0.3,0.1

Type RM Length L Ch R = 1 ,72489.62,447.895500,447.895500,447.895500
XS GIS Cut Line= 6
583364.028179174798745.504832672583489.961353196 798698.13776853
583735.026015798798597.836587614583954.796838375798531.412244005
584025.107280948798498.515283874 584286.39860174798361.340990345
#Sta/Elev= 30
9499.0561161.1169532.1461161.2579553.5141155.5189606.9341159.2599641.7741142.434
 9660.721129.8589671.5511127.1389693.2111128.3499736.5331098.2119758.1931098.393
9790.6841107.6439823.1751100.7169878.5051071.2719971.608996.03799982.068991.6751
10009.83991.366310034.12993.516910065.091003.68110139.421006.21210183.581014.685
10213.181016.65210239.751026.345 10285.21035.56510307.921045.85610342.011075.742
10381.681096.66810421.181125.69210432.351130.40610465.861128.30110500.931108.052
#Mann= 3 , 0 , 0
9499.056    0.04       09499.056    0.04       010500.93    0.04       0
#XS Ineff= 2 , 0
       0                               0
Bank Sta=9499.056,10500.93
Exp/Cntr=0.3,0.1

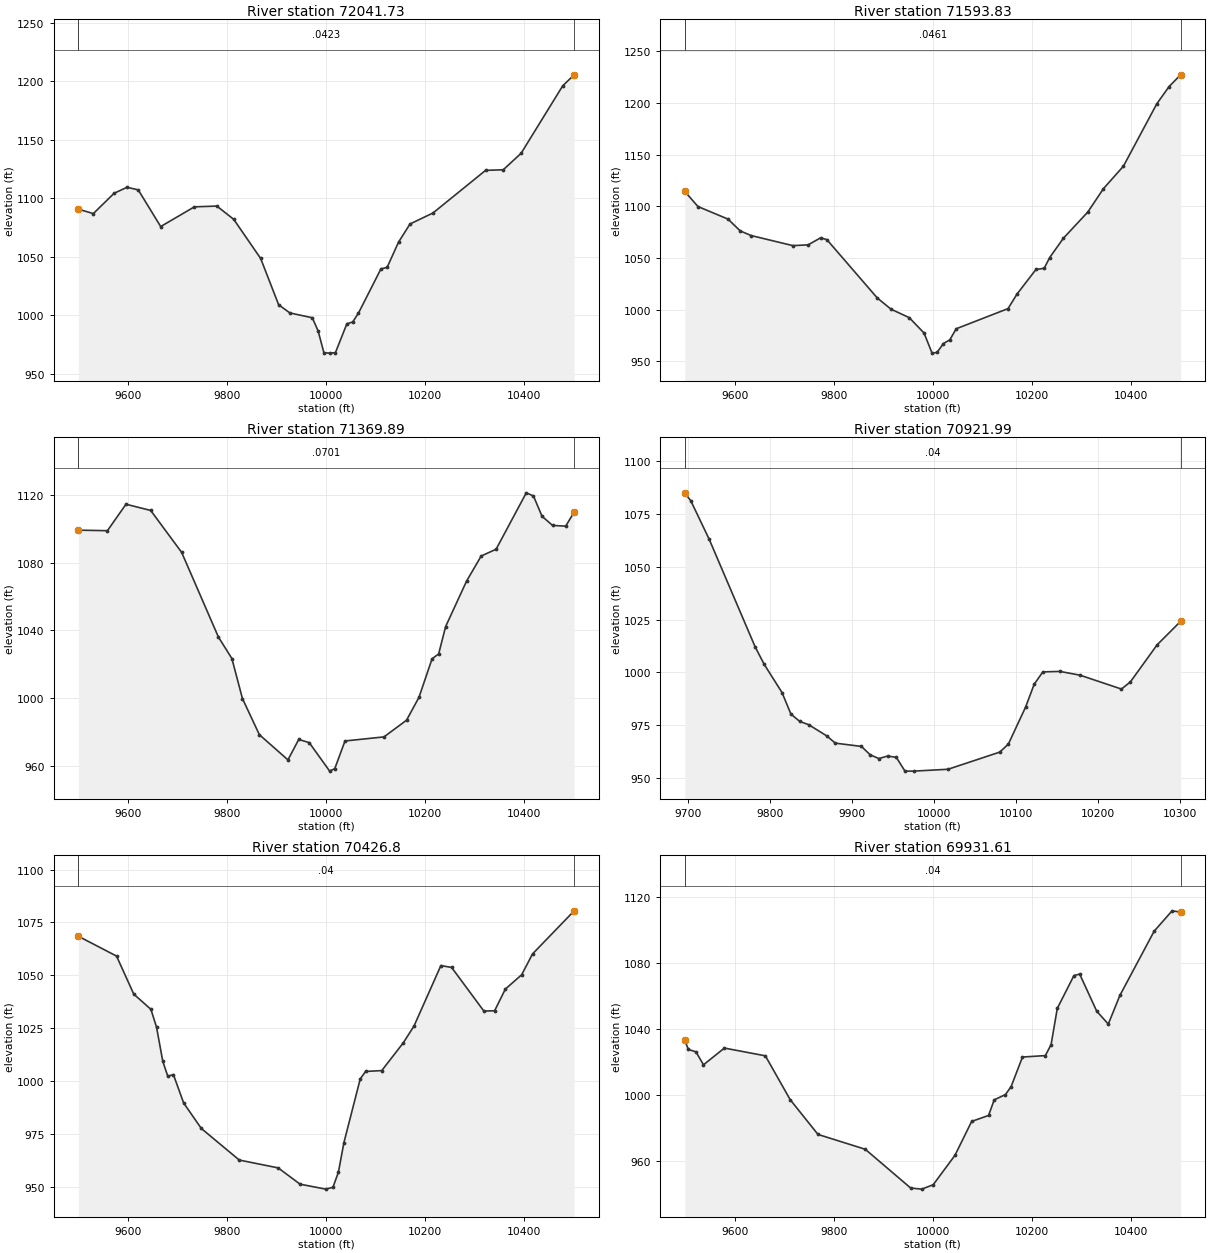
Type RM Length L Ch R = 1 ,72041.73,447.895400,447.895400,447.895400
XS GIS Cut Line= 6
583658.327354531799149.165402215 584074.53029547 798925.90811271
584099.884501056798910.481083888584313.578760117798784.971316686
584410.197646225798722.553596709584524.104513078798646.230235508
#Sta/Elev= 30
 9499.021090.6349529.2871086.8269571.297 1104.189597.3751109.308 9620.071107.102
9665.4621075.7469733.549  1092.6 9778.941093.2449812.9841081.9399867.4671048.489
9903.7671008.9499926.4631001.9359971.871997.8008 9983.57986.5504 9995.27967.9555
10006.93967.587510018.53967.985910041.72992.695810053.32994.153910064.92 1001.64
10110.551039.609 10122.91040.775 10146.11062.43510169.291077.95610215.681087.337
10321.951123.76310357.671124.27610393.711138.33110477.971196.08410500.971205.411
#Mann= 3 , 0 , 0
 9499.02  0.0423       0 9499.02  0.0423       010500.97  0.0423       0
#XS Ineff= 2 , 0
       0                               0
Bank Sta=9499.02,10500.97
Exp/Cntr=0.3,0.1

Type RM Length L Ch R = 1 ,71593.83,223.947800,223.947800,223.947800
XS GIS Cut Line= 6
583933.173126273799601.959459822584100.400080629799483.025271117
584213.192257904799391.452688668 584272.77224507799332.007952601
584427.249341678799153.016726208584670.849740441798929.406353654
#Sta/Elev= 30
9499.0291114.4159525.5711099.8089586.3711087.6389611.0021076.2329632.9111071.756
9717.2931061.9939748.1451062.7149773.5171069.5579786.2031067.7519887.9651011.369
9915.8681000.4799952.569992.34159982.475 977.4759998.707958.017510008.68958.6545
10021.63967.271210034.57970.880910047.52981.588110152.231001.08110170.271015.079
10208.631038.93410225.321040.06710236.291050.40310263.941069.05110313.421094.498
10344.981117.08110385.371138.823 10452.71199.05510477.681215.86410500.971227.182
#Mann= 3 , 0 , 0
9499.029  0.0461       09499.029  0.0461       010500.97  0.0461       0
#XS Ineff= 2 , 0
       0                               0
Bank Sta=9499.029,10500.97
Exp/Cntr=0.3,0.1

Type RM Length L Ch R = 1 ,71369.89,447.895400,447.895400,447.895400
XS GIS Cut Line= 6
584037.934191034799709.485214867584343.264630099799489.276215139
584527.873379049799422.552090311584599.169760047799382.171989991
584707.116301414 799284.21439377584835.760226662799131.023608499
#Sta/Elev= 30
9499.0481099.3579557.8471099.0339595.3251114.7049645.2961111.009 9707.76 1086.23
9782.1211036.0589809.2911023.3559830.635999.66099864.825978.26949922.589963.3381
9944.354975.42079965.539973.580310006.92956.681510017.23958.161710037.86974.5404
10116.57 976.94110162.17986.815810187.341000.37910213.811023.222 10227.11026.066
10241.251042.30910283.681069.28810313.051084.03110343.191088.06610404.161121.452
10418.681119.576   10436 1107.5610457.231102.16710483.761101.714 10500.91110.042
#Mann= 3 , 0 , 0
9499.048  0.0701       09499.048  0.0701       0 10500.9  0.0701       0
#XS Ineff= 2 , 0
       0                               0
Bank Sta=9499.048,10500.9
Exp/Cntr=0.3,0.1

Type RM Length L Ch R = 1 ,70921.99,495.187700,495.187700,495.187700
XS GIS Cut Line= 6
584661.909727596799981.600294348584703.164141236 799900.20503272
584737.882292594799818.593303413584765.901645035799740.662546799
584826.699740299799553.899604544584881.652201958799418.679320298
#Sta/Elev= 30
9695.723 1085.119703.123 1081.299725.5451063.057  9781.61012.0889792.6331003.807
9814.367990.46049825.234980.25339836.102976.74149846.969975.20119868.703969.9736
9879.484966.46629911.364964.90969921.991 960.9239932.618 959.1629943.244960.3487
9953.871959.74439964.437953.20629974.957953.200310017.02 954.08310080.12962.2133
10090.64966.016710111.67983.552610122.18 994.396 10132.71000.23410153.731000.452
10178.25998.664410228.64992.105910239.53995.467510272.211013.07310300.891024.209
#Mann= 3 , 0 , 0
9695.723    0.04       09695.723    0.04       010300.89    0.04       0
#XS Ineff= 2 , 0
       0                               0
Bank Sta=9695.723,10300.89
Exp/Cntr=0.3,0.1

Type RM Length L Ch R = 1 , 70426.8,495.187800,495.187800,495.187800
XS GIS Cut Line= 6
585017.445680127800290.279346116585089.734082864800172.212889151
585162.146007097800033.287082846585278.483731445799787.313186288
585394.473813748799513.236047133585451.315982467799388.468255705
#Sta/Elev= 30
9499.0191068.4589576.2211059.0739611.0361041.0949645.6751033.8999657.0341025.487
 9669.661009.3519679.753 1002.279691.1131003.0489711.819989.62659747.559977.5699
9824.214962.63679902.904958.92389947.157951.2186    9999948.885210013.55949.7552
 10024.6956.902510035.66970.842510068.781001.06110079.631004.52910112.211004.935
10155.651018.05210177.361026.00510231.661054.58810253.371053.69310318.521033.076
10340.241033.22510361.961043.474 10394.91050.23710416.881060.10210500.981080.471
#Mann= 3 , 0 , 0
9499.019    0.04       09499.019    0.04       010500.98    0.04       0
#XS Ineff= 2 , 0
       0                               0
Bank Sta=9499.019,10500.98
Exp/Cntr=0.3,0.1

Type RM Length L Ch R = 1 ,69931.61,495.187700,495.187700,495.187700
XS GIS Cut Line= 6
585400.219103325800485.422128134585509.556664908800355.176428383
585610.428567165800211.032263657585655.094321309800134.500052406
585763.665844769799925.398551671585932.953128505799640.305536214
#Sta/Elev= 30
9499.0531032.8879506.3431027.424 9521.591026.0019536.8371018.1249579.0941028.279
9661.8391023.5769712.003996.97339768.206975.87849863.688966.88199955.535943.3476
9977.892 942.691   10001945.353510044.98963.199210078.71983.769510112.89987.3957
10124.28996.849710147.061000.08710158.461004.91910181.411022.83910227.661023.713
10239.221030.39410251.771052.36110285.461072.30510297.021073.16510331.491050.625
10354.831042.83910378.181060.186 10447.51099.20510483.751111.55110500.98 1110.77
#Mann= 3 , 0 , 0
9499.053    0.04       09499.053    0.04       010500.98    0.04       0
#XS Ineff= 2 , 0
       0                               0
Bank Sta=9499.053,10500.98
Exp/Cntr=0.3,0.1