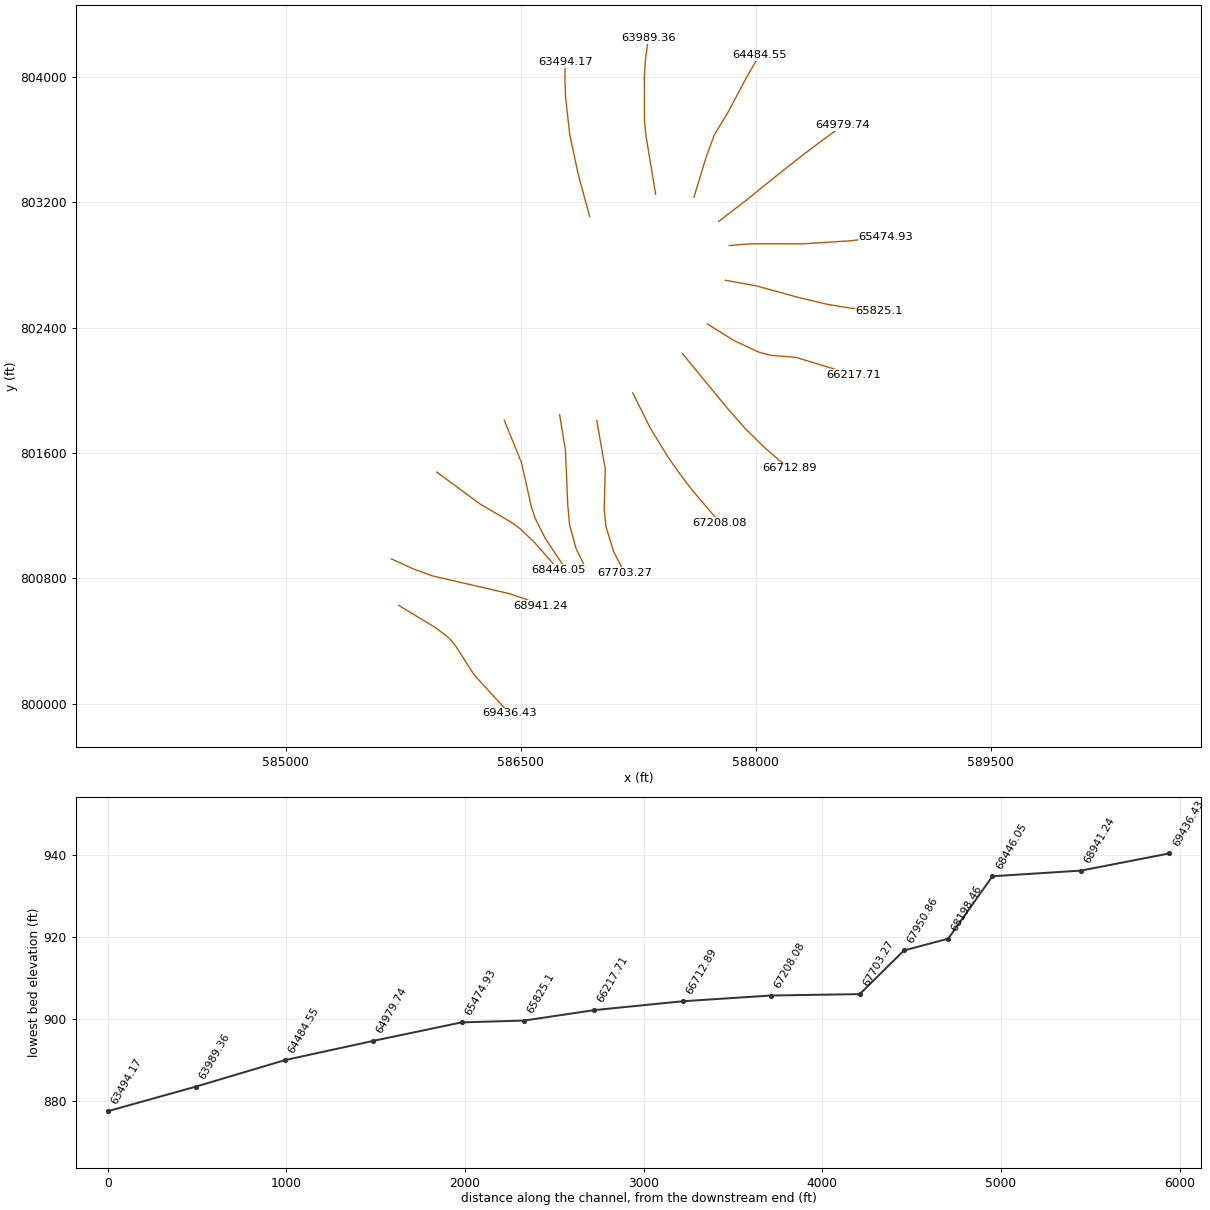
HEC-RAS study 10395_ras.prj: 10395

--- 10395_ras.g01 (geometry) --- (continued)

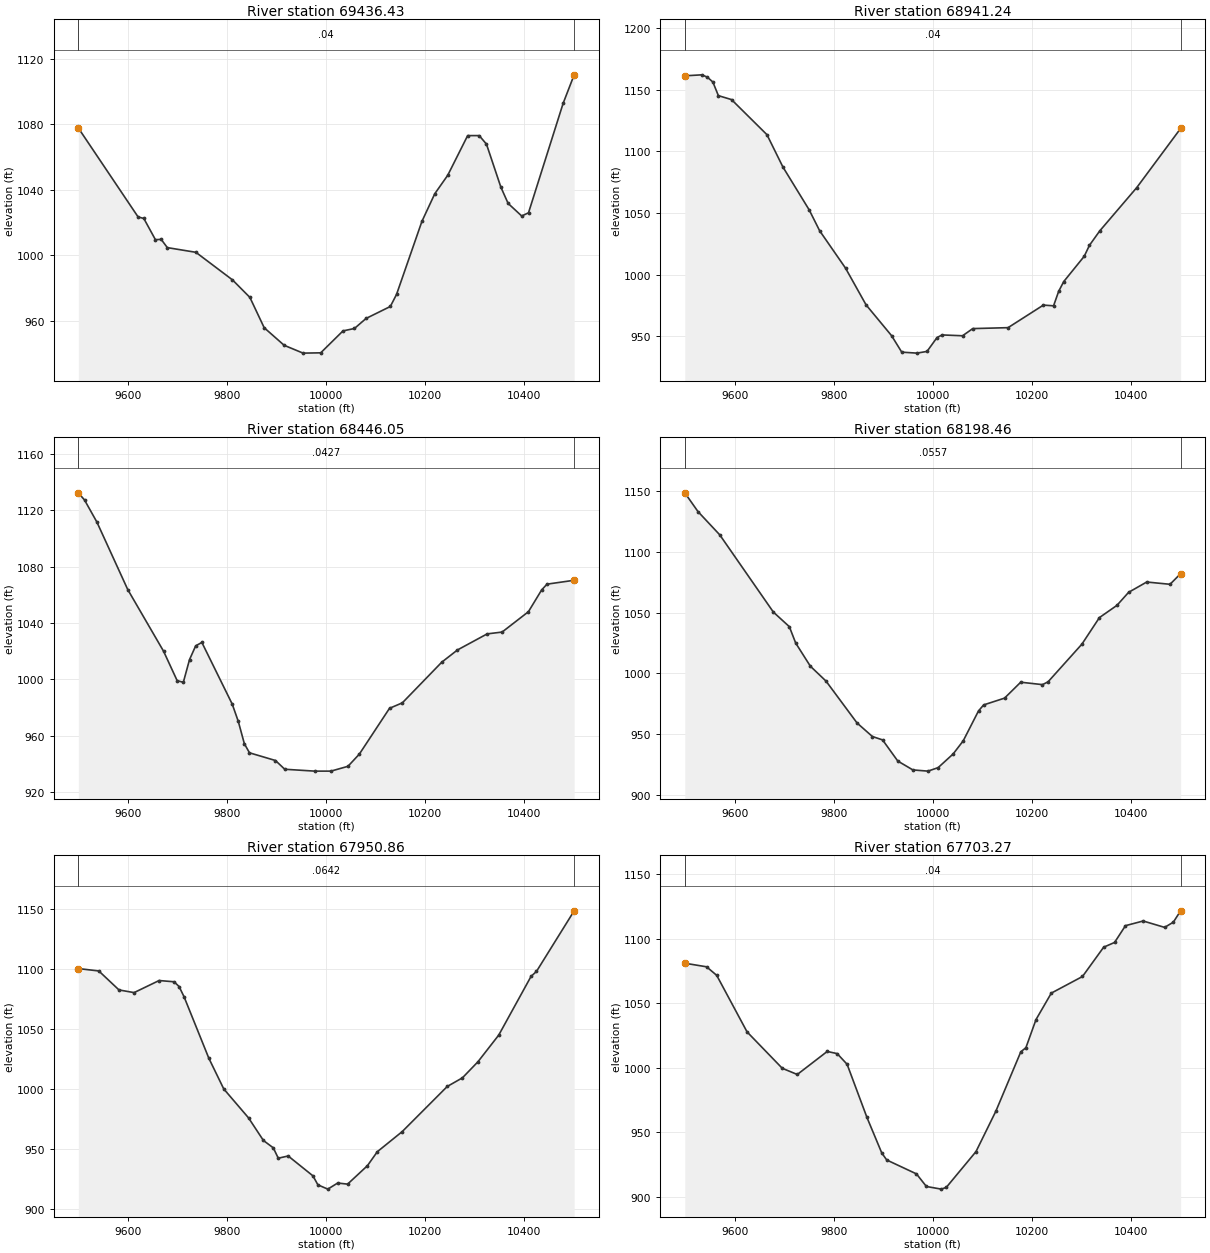
Type RM Length L Ch R = 1 ,69436.43,495.187700,495.187700,495.187700
XS GIS Cut Line= 6
585721.740294612800628.048205655585956.764725248800485.905573564
586043.693509934800419.303829021586083.175581132800372.048083705
586201.356950595800186.318580223 586427.80800601799939.132469912
#Sta/Elev= 30
9499.1141077.746 9619.791023.5219631.4761022.534 9654.85 1009.629666.5361009.793
9678.9131004.7729736.6561001.9099810.578  985.089845.737974.39999874.645955.8993
9914.975945.1815 9953.22940.40059988.869940.583510033.89953.960210056.94955.4259
10080.55961.564910129.51968.859710142.08976.224910193.291020.734 10219.3 1037.62
10245.571048.93910285.75  1073.1 10309.11073.11510323.771067.90510352.941041.595
10367.531031.73810394.97 1024.06 10408.71026.017 10478.71092.81510500.951110.185
#Mann= 3 , 0 , 0
9499.114    0.04       09499.114    0.04       010500.95    0.04       0
#XS Ineff= 2 , 0
       0                               0
Bank Sta=9499.114,10500.95
Exp/Cntr=0.3,0.1

Type RM Length L Ch R = 1 ,68941.24,495.187800,495.187800,495.187800
XS GIS Cut Line= 6
585673.799674488800925.240156882585812.054460725800861.889859493
585935.848781164800816.538256051586424.105881134800703.803645612
586528.128228588800669.511926105586625.320320126 800624.95609343
#Sta/Elev= 30
9499.0351161.3119533.6191162.1259544.7041160.2089555.7881156.2699566.8731145.229
9593.4111142.0299665.0441113.5359697.3091087.284 9750.38 1052.499771.5311035.542
9823.7931005.2299865.309975.39789916.814950.4111 9937.41937.00559968.111936.2095
9988.487937.6031 10008.7948.8562   10019950.975910060.29950.303110080.92956.1215
10152.26956.883810223.63975.2033 10244.2974.610110254.49986.348310264.77994.2935
10306.221014.85210316.651023.68710337.561035.453 10412.41070.63910500.951118.599
#Mann= 3 , 0 , 0
9499.035    0.04       09499.035    0.04       010500.95    0.04       0
#XS Ineff= 2 , 0
       0                               0
Bank Sta=9499.035,10500.95
Exp/Cntr=0.3,0.1

Type RM Length L Ch R = 1 ,68446.05,247.593900,247.593900,247.593900
XS GIS Cut Line= 6
585964.966329927801478.037558266586243.464751716801273.006437892
586434.503994623 801161.29716301586495.374202916801118.204071414
586590.904775298801026.202606351586741.309797865800855.712960891
#Sta/Elev= 30
9499.0291132.542 9511.551127.4549536.5071111.7939598.901 1063.81 9671.281020.005
9698.731999.1051 9711.21997.94789723.689 1014.039736.1671023.8469748.6461026.257
9810.042982.41729822.282970.14159834.522 954.3079844.883947.84749897.393942.3757
9916.142936.16479976.773934.835610009.48  934.8410043.89938.255910066.86946.9191
10127.82979.455910153.82983.357210233.46 1012.2410265.121020.90810325.131032.328
10355.371033.62410408.551048.08610435.221063.54210446.061067.65810500.951070.424
#Mann= 3 , 0 , 0
9499.029  0.0427       09499.029  0.0427       010500.95  0.0427       0
#XS Ineff= 2 , 0
       0                               0
Bank Sta=9499.029,10500.95
Exp/Cntr=0.3,0.1

Type RM Length L Ch R = 1 ,68198.46,247.593800,247.593800,247.593800
XS GIS Cut Line= 6
586395.186641607801808.993906819586505.288790474 801538.07779031
586566.179995347801263.998226045586591.097033584801185.846381114
586656.671934278801055.535828842586767.306958982800888.923124262
#Sta/Elev= 30
9499.0471148.5969525.6661133.1769569.6761114.0279678.0761050.4379710.2681038.487
9723.1161025.0019752.7241005.9699784.417993.6878 9847.07 959.2479878.083948.1054
9898.682945.30469929.412 927.9189959.918920.60799990.423919.6248 10010.9922.4965
10041.25933.754210061.58944.5307 10092.5969.149710102.89974.102310145.11979.6798
10177.78992.779710221.77 990.79210233.01 993.07810301.461024.11410336.841045.955
10372.221056.004 10395.81066.72910432.381075.21310479.481073.343 10500.91082.083
#Mann= 3 , 0 , 0
9499.047  0.0557       09499.047  0.0557       0 10500.9  0.0557       0
#XS Ineff= 2 , 0
       0                               0
Bank Sta=9499.047,10500.9
Exp/Cntr=0.3,0.1

Type RM Length L Ch R = 1 ,67950.86,247.593900,247.593900,247.593900
XS GIS Cut Line= 6
 586748.12619456801845.563916315586785.438669126801616.410286258
586800.009679951801268.173811156586811.586306998801142.896342024
 586852.82136798800990.653122142586913.365218111800867.789368065
#Sta/Elev= 30
9499.0381100.3059540.3921098.3289581.172 1082.539611.7191080.308 9662.27 1090.36
9692.5181089.3219702.5811085.3779712.6431076.8749762.8261025.6039792.8891000.132
9842.995976.02829873.026957.23449893.041951.07949903.049942.48429923.065944.3353
9973.099927.79339983.099920.3266 10003.1916.7478 10023.1921.829710043.11920.9078
10083.15936.2295 10103.2947.887110153.33964.5683 10244.5 1002.1910275.14 1009.37
10306.451022.71610348.551044.97210413.851093.834 10424.81097.93910500.921148.371
#Mann= 3 , 0 , 0
9499.038  0.0642       09499.038  0.0642       010500.92  0.0642       0
#XS Ineff= 2 , 0
       0                               0
Bank Sta=9499.038,10500.92
Exp/Cntr=0.3,0.1

Type RM Length L Ch R = 1 ,67703.27,495.187700,495.187700,495.187700
XS GIS Cut Line= 6
 586984.97676289801807.948470545 587039.20622492801499.177350805
587032.577843568801241.744013079587043.284520953801133.357340886
587092.583679856800971.446407822587162.254262281800836.869259796
#Sta/Elev= 30
9499.0371081.1179543.0461078.336 9563.541071.7059624.8621027.9039695.969 999.724
9726.328994.91579786.8281012.7669806.9441011.0919827.0041002.8149867.063961.6817
9897.063934.09819907.063928.68889967.164917.90279987.255908.152210017.38906.1097
10027.42 907.45510087.45935.193610127.55966.468510178.041012.51210188.241015.637
10208.691037.46210239.661057.96510302.621070.82710345.431093.53710367.421097.201
10389.51 1110.21 10425.21113.818 10468.61108.87310486.171112.90810500.911121.698
#Mann= 3 , 0 , 0
9499.037    0.04       09499.037    0.04       010500.91    0.04       0
#XS Ineff= 2 , 0
       0                               0
Bank Sta=9499.037,10500.91
Exp/Cntr=0.3,0.1

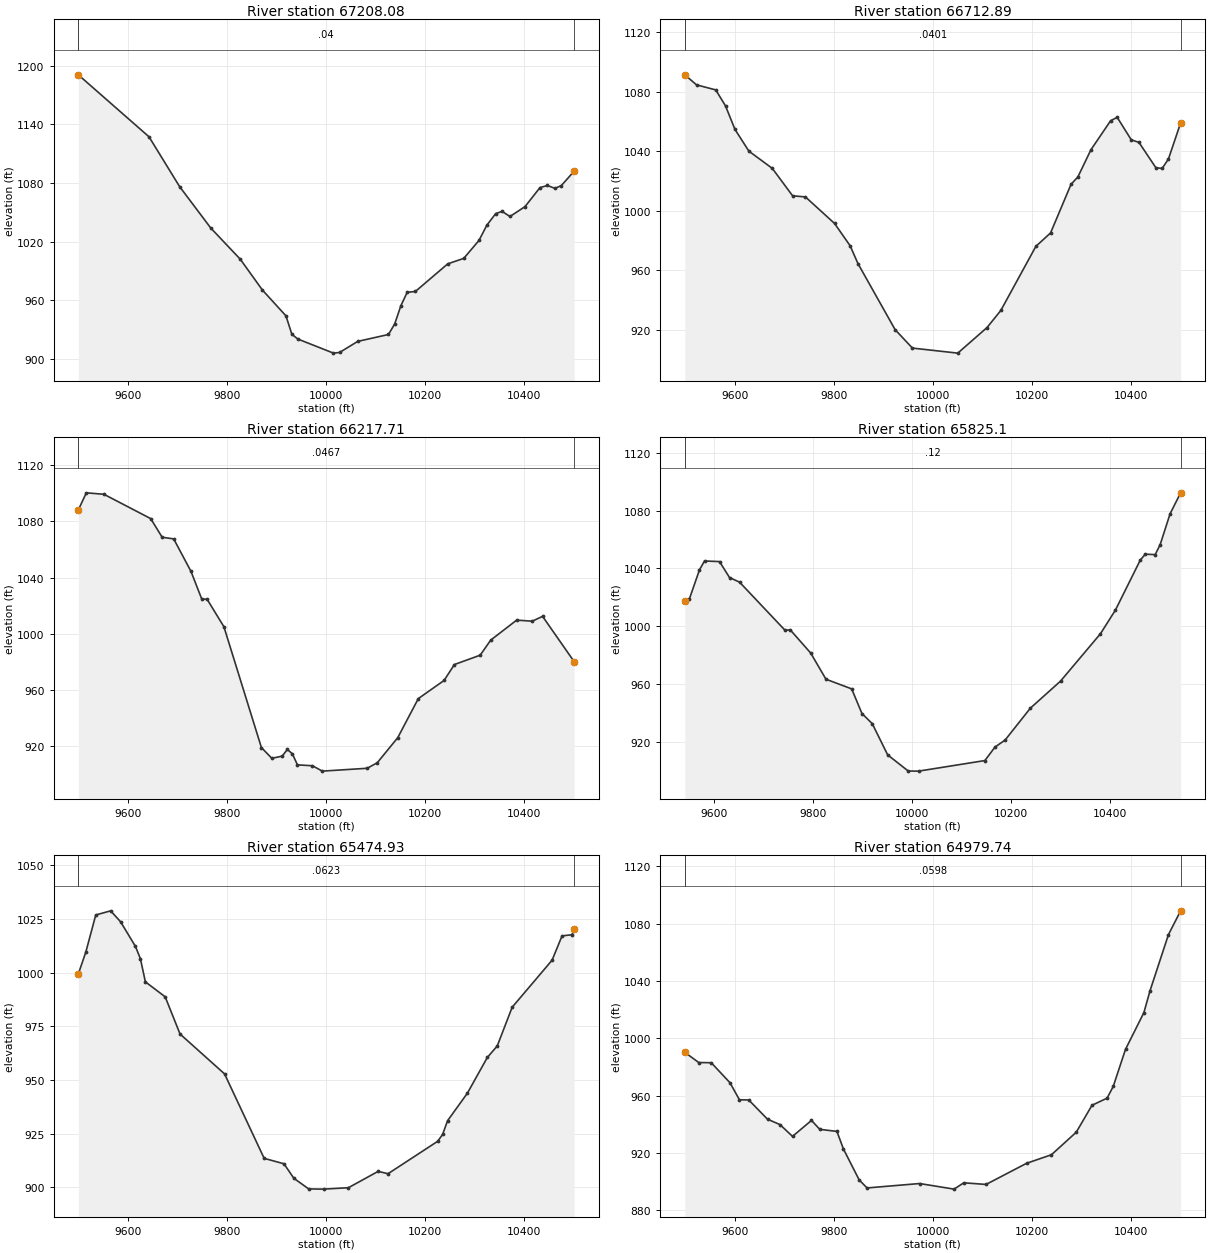
Type RM Length L Ch R = 1 ,67208.08,495.187800,495.187800,495.187800
XS GIS Cut Line= 6
587214.506028216 801983.77322046587327.094486238  801758.2269004
587442.297509111 801570.67422887587513.680740124801469.042074573
587596.806721924801360.184682702587770.609992143801155.603707448
#Sta/Elev= 30
 9499.031190.7919641.8611127.3249703.628 1076.369766.4791033.9899826.2951001.946
9871.029970.37539918.602943.92939930.495925.13649942.389920.241710014.63905.7722
10026.89906.437110063.69917.808710125.77924.856510138.35935.705210150.94954.4928
 10163.6968.092210180.08968.910110245.44997.180410277.911002.82510308.691021.219
 10324.51036.75710342.461048.68310355.371050.937 10371.31045.699 10401.61055.795
10431.891075.28810447.041077.47210462.181074.48710475.151077.41410500.971092.138
#Mann= 3 , 0 , 0
 9499.03    0.04       0 9499.03    0.04       010500.97    0.04       0
#XS Ineff= 2 , 0
       0                               0
Bank Sta=9499.03,10500.97
Exp/Cntr=0.3,0.1

Type RM Length L Ch R = 1 ,66712.89,495.187700,495.187700,495.187700
XS GIS Cut Line= 6
587532.756246499802233.302918816587819.158956866801884.969198441
587927.003149692801762.471357528588054.565134736801636.208801372
588141.901837276801560.219502817588214.282215812801502.627447563
#Sta/Elev= 30
9499.0061091.2389522.7011084.5089561.5391081.1079581.2661070.3829600.3781054.592
9628.5031039.996 9675.741028.4579716.8931010.0099742.7851009.2629801.705991.4185
9833.196 976.4269848.941964.48169924.031920.13329958.994907.755410050.63904.3748
10109.77921.553710137.57933.002110208.46 976.06710238.15985.086610279.521017.723
10293.281022.64710319.791040.96710359.561060.44510372.811062.69110401.191047.622
10416.851045.84810450.771028.94210463.551028.34510476.331034.69710500.971058.959
#Mann= 3 , 0 , 0
9499.006  0.0401       09499.006  0.0401       010500.97  0.0401       0
#XS Ineff= 2 , 0
       0                               0
Bank Sta=9499.006,10500.97
Exp/Cntr=0.3,0.1

Type RM Length L Ch R = 1 ,66217.71,392.608500,392.608500,392.608500
XS GIS Cut Line= 6
587691.440360681802423.127480877587861.370511173802317.580712439
588017.644650969802244.481282816588097.387988248802223.447474268
588255.284241376802210.621530915588625.892561649802098.375577688
#Sta/Elev= 30
9499.1261088.112 9515.291100.2779550.7971099.2519645.2831081.9399668.5411068.642
9691.7991067.5019726.7411044.3549748.256 1024.899759.4981024.4119793.2241005.003
9869.015919.00179890.047911.33979910.985912.86769921.419917.62319931.618914.5201
9941.818906.66029972.108906.03769992.154902.208710082.73904.241910103.16908.1783
10144.52926.027110186.03 953.817 10238.1966.746110259.05978.0839   10311984.7111
10332.39995.460710384.77 1009.68 10416.21008.92810437.151012.35610500.94980.1155
#Mann= 3 , 0 , 0
9499.126  0.0467       09499.126  0.0467       010500.94  0.0467       0
#XS Ineff= 2 , 0
       0                               0
Bank Sta=9499.126,10500.94
Exp/Cntr=0.3,0.1

Type RM Length L Ch R = 1 , 65825.1,350.173100,350.173100,350.173100
XS GIS Cut Line= 6
587805.630310367802702.540127127588002.452323137802667.139940332
 588279.12840748802591.006719269588457.045485223802548.997135425
588611.944133492802523.771430389588786.197627425802506.725861201
#Sta/Elev= 30
9540.1961017.7549549.6711019.0789569.8961039.0099580.008 1045.129610.3451044.708
9630.5691033.6599650.8971030.4599742.891997.10559753.214997.48879794.507981.4461
9825.477963.28259877.392956.59579898.186 939.541 9918.98932.53679950.171910.9069
9991.759899.731310012.55 899.66710146.56906.979910167.03916.3134 10187.5921.1843
10238.47943.238310299.41961.956110380.17994.776710410.361011.12110460.661045.764
10470.691049.81910490.761049.533 10500.81056.44710520.871077.80310542.141092.292
#Mann= 3 , 0 , 0
9540.196    0.12       09540.196    0.12       010542.14    0.12       0
#XS Ineff= 2 , 0
       0                               0
Bank Sta=9540.196,10542.14
Exp/Cntr=0.3,0.1

Type RM Length L Ch R = 1 ,65474.93,495.187700,495.187700,495.187700
XS GIS Cut Line= 6
587829.927233113802923.903778668587930.356724721802932.635687847
587999.573817581802935.495640459588298.979333792802934.950492948
588594.432225085802953.845052712588829.282839453802980.256702994
#Sta/Elev= 30
9499.033 999.3329514.1631009.5019534.2391026.7729564.352  1028.79584.4271023.607
9614.4981012.1259624.5061006.3969634.515995.65729674.544988.68889704.545971.3906
9794.549952.82599874.559913.53489914.564911.01169934.568904.26529964.574899.3047
9994.652899.218410044.81899.877110104.88907.473410124.91906.3949 10225.1921.4578
10235.13924.635510245.15931.0283 10285.3943.876610325.48960.473410345.57965.8215
10375.74983.855110456.361005.72610476.521017.03910496.671017.57810500.991020.436
#Mann= 3 , 0 , 0
9499.033  0.0623       09499.033  0.0623       010500.99  0.0623       0
#XS Ineff= 2 , 0
       0                               0
Bank Sta=9499.033,10500.99
Exp/Cntr=0.3,0.1

Type RM Length L Ch R = 1 ,64979.74,495.187800,495.187800,495.187800
XS GIS Cut Line= 6
587762.653800467 803077.60731319587942.684110429803216.456118877
588156.416561794803388.924692632588283.001766901803488.665271793
588399.003170141803576.681005016588554.846739196803690.909245102
#Sta/Elev= 30
9499.006990.16529527.226983.03789552.484982.9092 9590.37968.92849609.356957.0645
9628.256956.92059666.142943.50619691.399939.73089716.656931.52069755.036 942.655
9771.812936.41539806.436934.98639819.582 922.7079851.429901.10879867.353895.5324
9973.487898.609710043.13 894.70710062.85899.124710107.76897.976810189.77912.7406
10239.98918.702310290.19934.468310321.84 953.206 10352.4958.1977 10364.8966.3545
 10389.6992.243210426.791017.90710439.191033.19110476.391072.28410500.991088.895
#Mann= 3 , 0 , 0
9499.006  0.0598       09499.006  0.0598       010500.99  0.0598       0
#XS Ineff= 2 , 0
       0                               0
Bank Sta=9499.006,10500.99
Exp/Cntr=0.3,0.1

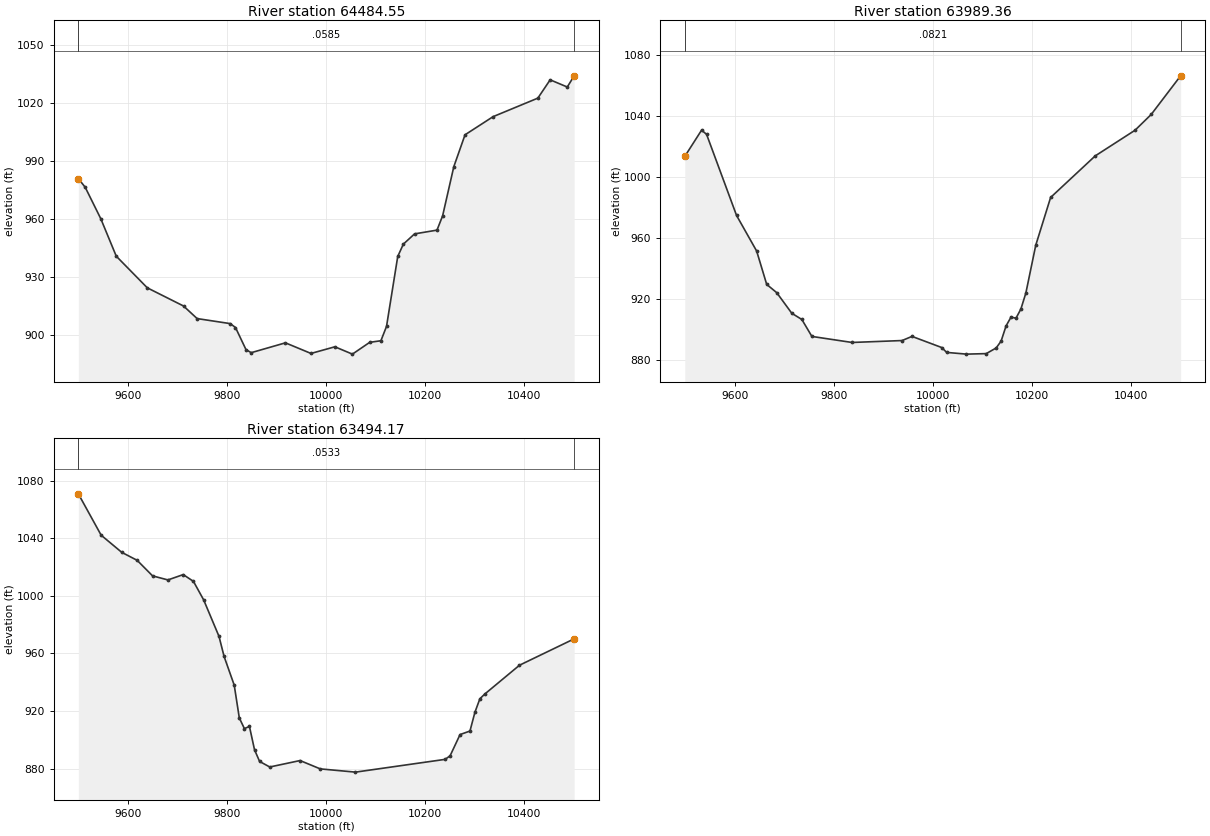
Type RM Length L Ch R = 1 ,64484.55,495.187700,495.187700,495.187700
XS GIS Cut Line= 6
587605.113877781803231.673471525587685.082244255 803494.44413332
587735.953838469803631.591700322587819.246785935803768.642470676
587939.234175493 803993.79527491588021.548132404 804137.05071558
#Sta/Elev= 30
9499.059 980.9289512.989976.41639544.347960.19169575.706940.73879638.423924.3446
9711.592914.93659739.098908.42019806.055  905.819816.634903.79289837.793892.3768
9848.373890.75479917.532 895.8519969.205890.358110017.47893.805510052.89890.0058
10087.83896.114610110.49 896.94410121.82 904.37310144.48940.594310155.82946.9833
10178.48952.2907 10223.8954.237910235.14961.6116 10257.8987.114310280.461003.616
10337.14 1013.0110427.611022.60810452.471032.08810487.071028.36410500.971034.161
#Mann= 3 , 0 , 0
9499.059  0.0585       09499.059  0.0585       010500.97  0.0585       0
#XS Ineff= 2 , 0
       0                               0
Bank Sta=9499.059,10500.97
Exp/Cntr=0.3,0.1

Type RM Length L Ch R = 1 ,63989.36,495.187700,495.187700,495.187700
XS GIS Cut Line= 6
587360.592805668803251.462382313587300.046796305803619.277589196
587289.346235903803712.320002621587288.962139371804010.574320722
587296.606984608804118.357103354587314.329392407804246.188924933
#Sta/Elev= 30
9499.0361013.3239532.9121030.5289543.0121027.8229603.634974.56899644.228951.2249
9664.525929.35119684.822923.90929715.267910.38949735.564906.31939755.861895.1967
9837.048891.23979938.104892.50239958.174895.222910018.21887.916810028.21884.7165
10068.22883.588810108.22883.923810128.23887.645610138.23892.133310148.23 902.104
10158.24907.887810168.24907.157410178.24913.224610188.24923.703510208.25955.0827
10238.25986.384210328.421013.66310408.791030.481 10441.51040.83910500.961066.195
#Mann= 3 , 0 , 0
9499.036  0.0821       09499.036  0.0821       010500.96  0.0821       0
#XS Ineff= 2 , 0
       0                               0
Bank Sta=9499.036,10500.96
Exp/Cntr=0.3,0.1

Type RM Length L Ch R = 1 ,63494.17,495.187800,495.187800,495.187800
XS GIS Cut Line= 6
586939.445917903803110.611218061586866.336652288803380.319613076
586812.507636794803633.969299085586786.340431529803867.911337648
 586781.89135788803974.382408131 586783.11245689 804095.46111778
#Sta/Elev= 30
9499.0241070.8939545.1611042.1519586.7371030.2549617.9181024.6899649.0661013.891
9680.0481011.0859711.0291014.7899731.6831010.0599752.337997.17219783.285  971.86
 9793.54 957.9419814.049937.98149824.304915.21189834.558907.81819844.813909.2773
9855.068893.07849865.323884.99139885.832881.1363 9947.08 885.6119987.913879.8188
10059.04 877.56910240.25886.438210250.29888.932410270.36903.661110290.39906.1128
 10300.4919.139310310.41928.510310320.42931.835610390.47951.834210500.94970.1528
#Mann= 3 , 0 , 0
9499.024  0.0533       09499.024  0.0533       010500.94  0.0533       0
#XS Ineff= 2 , 0
       0                               0
Bank Sta=9499.024,10500.94
Exp/Cntr=0.3,0.1