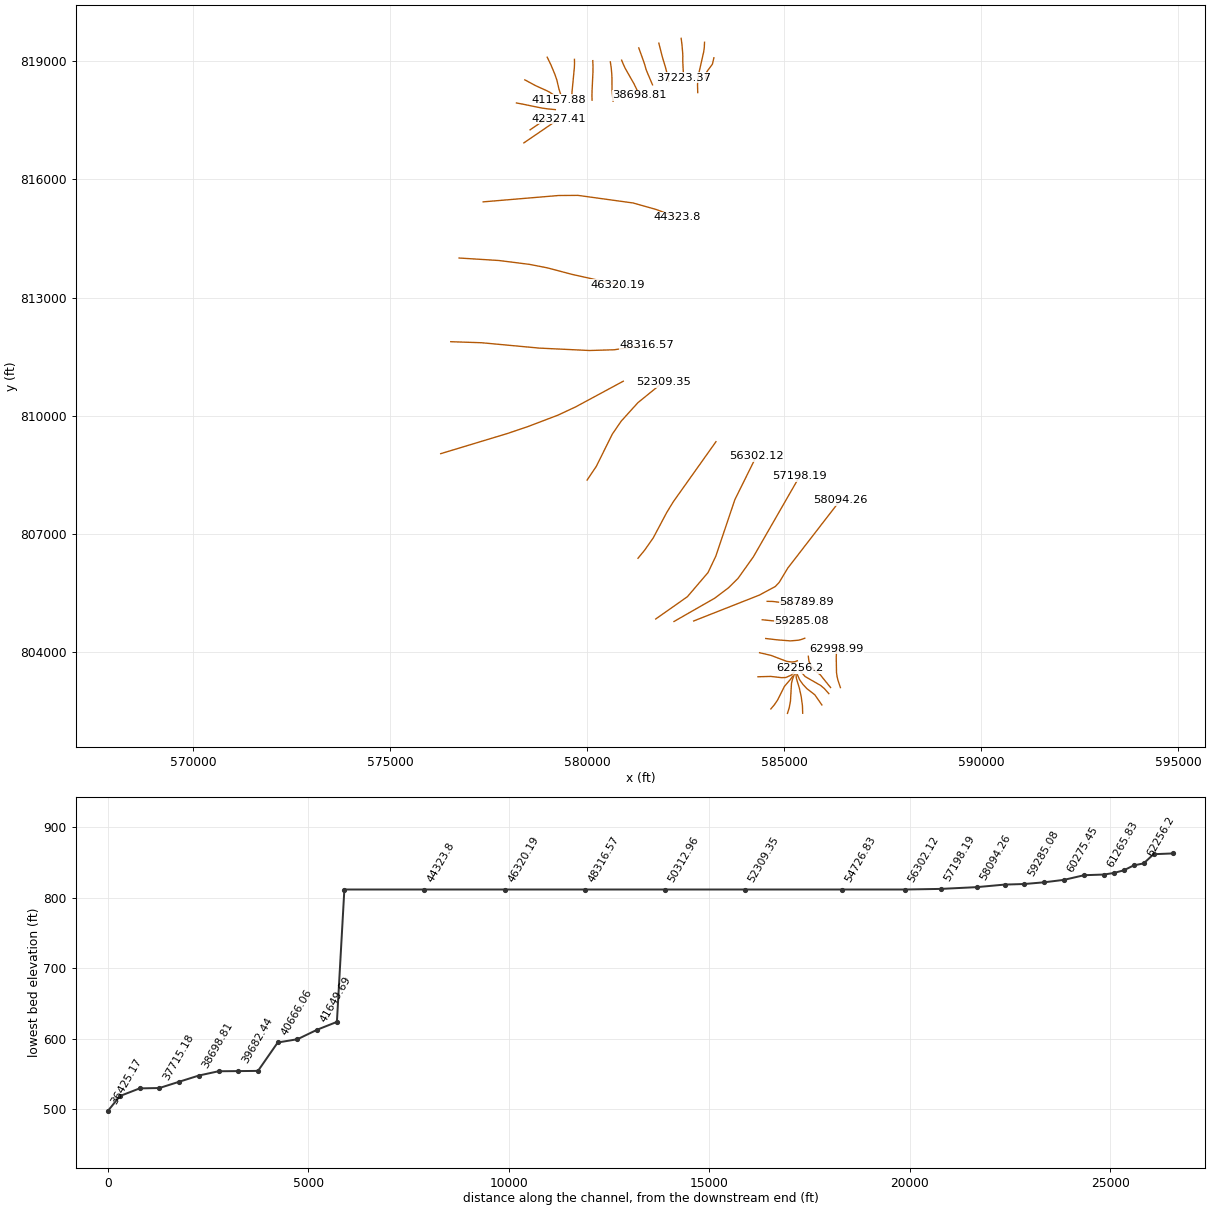
HEC-RAS study 10395_ras.prj: 10395

--- 10395_ras.g01 (geometry) --- (continued)

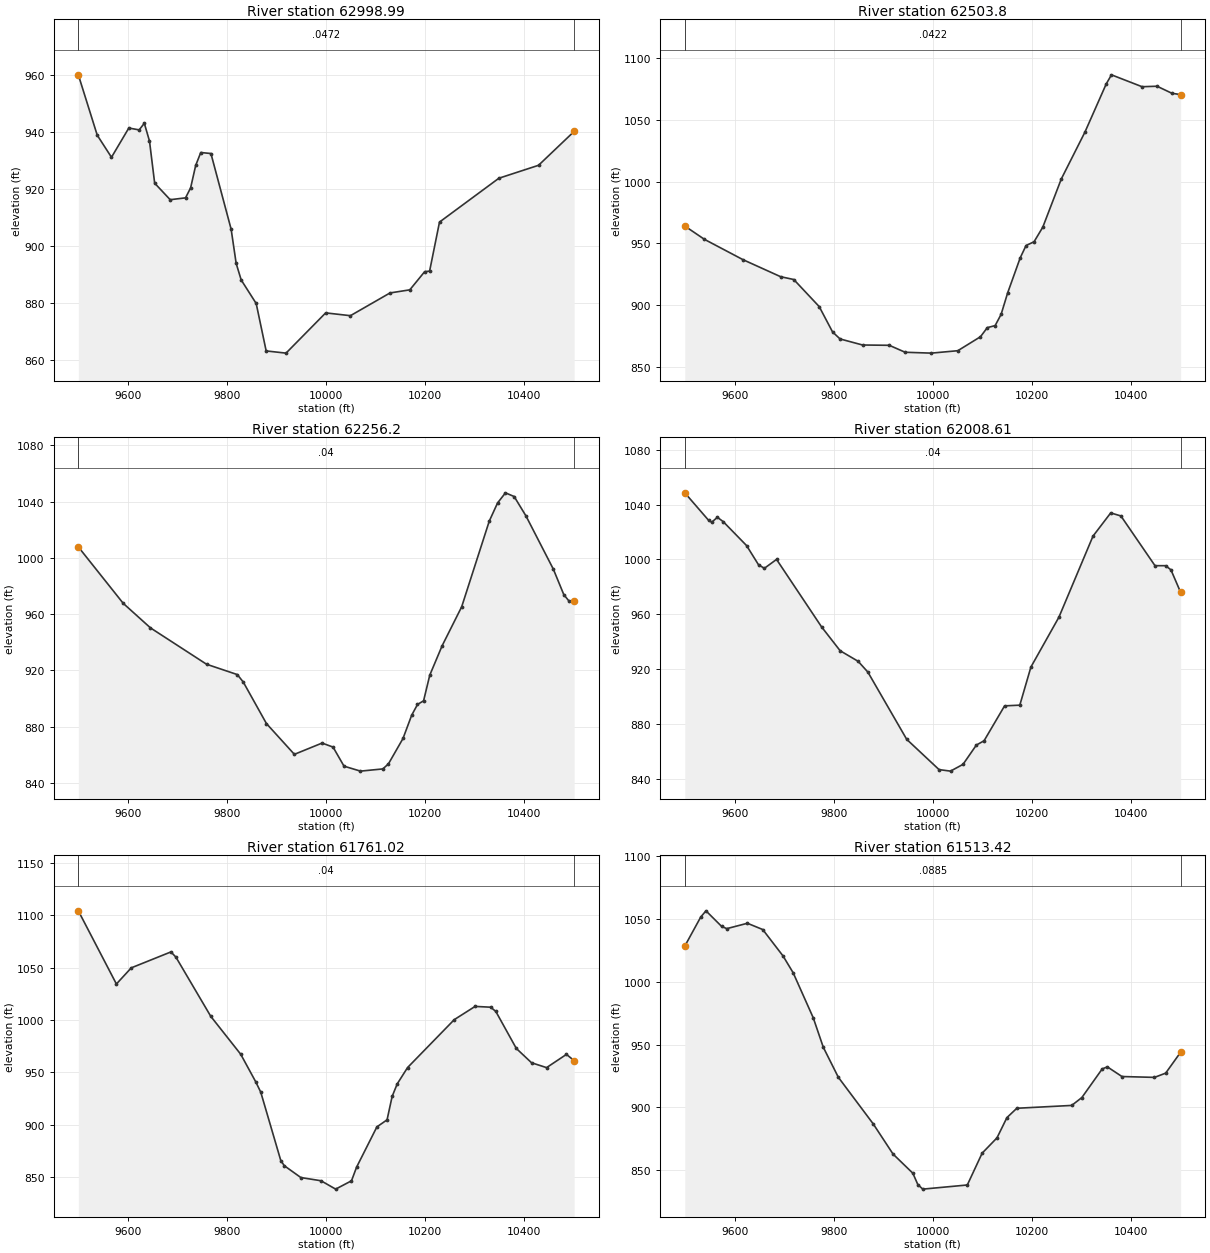
Type RM Length L Ch R = 1 ,62998.99,495.187700,495.187700,495.187700
XS GIS Cut Line= 6
586427.878890993803109.099309482 586364.70725483803298.855447829
586343.490879669803391.503181752 586329.17698077803490.163080957
586322.652324476803875.468743272586331.569465704804096.870471294
#Sta/Elev= 30
9499.075959.91269537.272938.7727 9566.06931.03469601.089941.27869621.984940.6317
9632.432 942.9459642.879936.70679653.327921.96589684.669916.18039715.707916.8273
9725.966920.32119736.225928.18869746.484932.70419767.002932.35659807.875905.8286
9818.014893.86299828.153888.07949858.484879.83029878.633 863.2189918.786862.4488
9998.876876.542110048.88875.561810128.88 883.52410168.88884.613310198.88890.9726
10208.88891.169910228.88908.3418 10348.9923.700910428.97928.225410500.98940.1047
#Mann= 3 , 0 , 0
9499.075  0.0472       09499.075  0.0472       010500.98  0.0472       0
#XS Ineff= 2 , 0
       0                               0
Bank Sta=9499.075,10500.98
Exp/Cntr=0.3,0.1

Type RM Length L Ch R = 1 , 62503.8,247.593900,247.593900,247.593900
XS GIS Cut Line= 6
586178.131809191803110.132507076585919.396818983 803431.83779666
585786.069659715803534.201563447585702.079252371803630.642136929
585629.895836251803773.731611482585614.061351283 803902.61510174
#Sta/Elev= 30
 9499.05964.11869538.693953.36629616.625936.90569692.716 923.1269719.234920.8563
9770.614898.95619797.591878.45539812.745 872.7789858.207  867.88 9912.16867.6406
9944.261862.01239997.225 861.30710050.68863.267910096.41874.552310110.33881.9583
10126.05883.563310138.17892.696410151.34910.0252 10176.8938.457910188.55948.3521
10204.72951.409510222.37963.204710259.791002.23910307.331039.95210350.511079.058
 10361.11086.43610422.891076.824 10453.21077.20610483.22 1071.5110500.841070.443
#Mann= 3 , 0 , 0
 9499.05  0.0422       0 9499.05  0.0422       010500.84  0.0422       0
#XS Ineff= 2 , 0
       0                               0
Bank Sta=9499.05,10500.84
Exp/Cntr=0.3,0.1

Type RM Length L Ch R = 1 , 62256.2,247.593900,247.593900,247.593900
XS GIS Cut Line= 6
586134.591890017802954.999556456586022.223761248803082.504416315
585926.671306139803163.016334197585533.297665817803388.820968397
585433.744670888803501.894175582585397.155173381803595.236393134
#Sta/Elev= 30
9499.0721007.7599589.805 967.6249644.863950.16929758.142 924.3239820.314916.9701
9832.368911.65239879.144882.14369935.602860.24759991.557868.258210013.77865.4103
10035.93851.824710069.19848.306910114.38849.8741 10125.7853.480710155.11871.5297
10172.62888.059410184.38895.707710196.69898.331110209.19916.561310234.19937.4877
10273.65965.169810329.441026.14110346.161039.01110362.131046.23110379.781043.582
10403.621029.75810458.84991.974310480.07973.791310490.59969.234710500.94969.5628
#Mann= 3 , 0 , 0
9499.072    0.04       09499.072    0.04       010500.94    0.04       0
#XS Ineff= 2 , 0
       0                               0
Bank Sta=9499.072,10500.94
Exp/Cntr=0.3,0.1

Type RM Length L Ch R = 1 ,62008.61,247.593800,247.593800,247.593800
XS GIS Cut Line= 6
585958.315537654802667.422658119585777.385894779802928.407141503
585575.897953925803083.031460196585472.304324169803196.138693545
585393.044350964803308.445730086585338.677966957 803433.76211683
#Sta/Elev= 30
9499.0931048.5259547.1521028.4799553.5021027.0749564.9591030.6669576.6911027.506
9623.9741010.0069648.052996.01469659.887993.44449684.462999.94129775.387950.7292
9812.984933.29669849.352925.58389868.933917.74749947.449 868.65710012.76846.5752
10035.95845.455110061.24850.405510088.19864.470810103.76867.613210145.21893.0723
10175.96893.594310198.41921.415410254.97957.772310323.861016.93310359.661033.878
10380.241031.644 10449.1995.367110470.73995.357710481.39992.289610500.89 975.924
#Mann= 3 , 0 , 0
9499.093    0.04       09499.093    0.04       010500.89    0.04       0
#XS Ineff= 2 , 0
       0                               0
Bank Sta=9499.093,10500.89
Exp/Cntr=0.3,0.1

Type RM Length L Ch R = 1 ,61761.02,247.593900,247.593900,247.593900
XS GIS Cut Line= 6
585471.439287907 802458.06546662585464.918101952802647.680124531
585431.912092777802892.481912897585387.388726007803092.532295639
585312.105381793803340.521173673585301.478288584803440.556789543
#Sta/Elev= 30
9499.0481104.1079575.9831034.2749606.0241049.6879686.1891064.8969696.2431059.911
9766.7081003.3879827.226967.19719857.567940.87369867.681931.02449908.135865.8038
9915.273860.82859948.689849.55889989.458846.487410019.02838.503910051.03846.4568
 10061.3859.453710102.36 897.907 10122.9904.629210133.16926.986610143.47938.9771
10164.32954.512510258.671000.24310300.781012.88810332.341012.12810342.691008.061
10384.08972.767810414.84959.107110445.24954.470210485.39967.101910500.96961.1093
#Mann= 3 , 0 , 0
9499.048    0.04       09499.048    0.04       010500.96    0.04       0
#XS Ineff= 2 , 0
       0                               0
Bank Sta=9499.048,10500.96
Exp/Cntr=0.3,0.1

Type RM Length L Ch R = 1 ,61513.42,247.593900,247.593900,247.593900
XS GIS Cut Line= 6
 585084.89023865802454.575171309585128.458033019802592.695708213
585161.339001573802765.900581628585187.239315026803217.949190798
585208.886727311803305.504132121585255.836163812 803434.30230686
#Sta/Elev= 30
9499.0561028.4959531.2661051.6829541.8531056.6259573.6141044.1399584.0131042.435
9625.5671046.7089656.557 1041.719697.5391020.658 9718.031007.2379758.634971.3185
9778.894947.86419809.283923.93959879.773886.78449919.865862.70769959.911 847.422
9969.913838.42199979.915834.756310069.92838.056210099.92863.437610129.94875.6565
10149.95891.767410169.97 899.22210280.85901.481610301.34907.748110342.51930.5953
10352.92 932.22310382.42924.523310448.14923.841110470.77927.231410500.96943.8881
#Mann= 3 , 0 , 0
9499.056  0.0885       09499.056  0.0885       010500.96  0.0885       0
#XS Ineff= 2 , 0
       0                               0
Bank Sta=9499.056,10500.96
Exp/Cntr=0.3,0.1

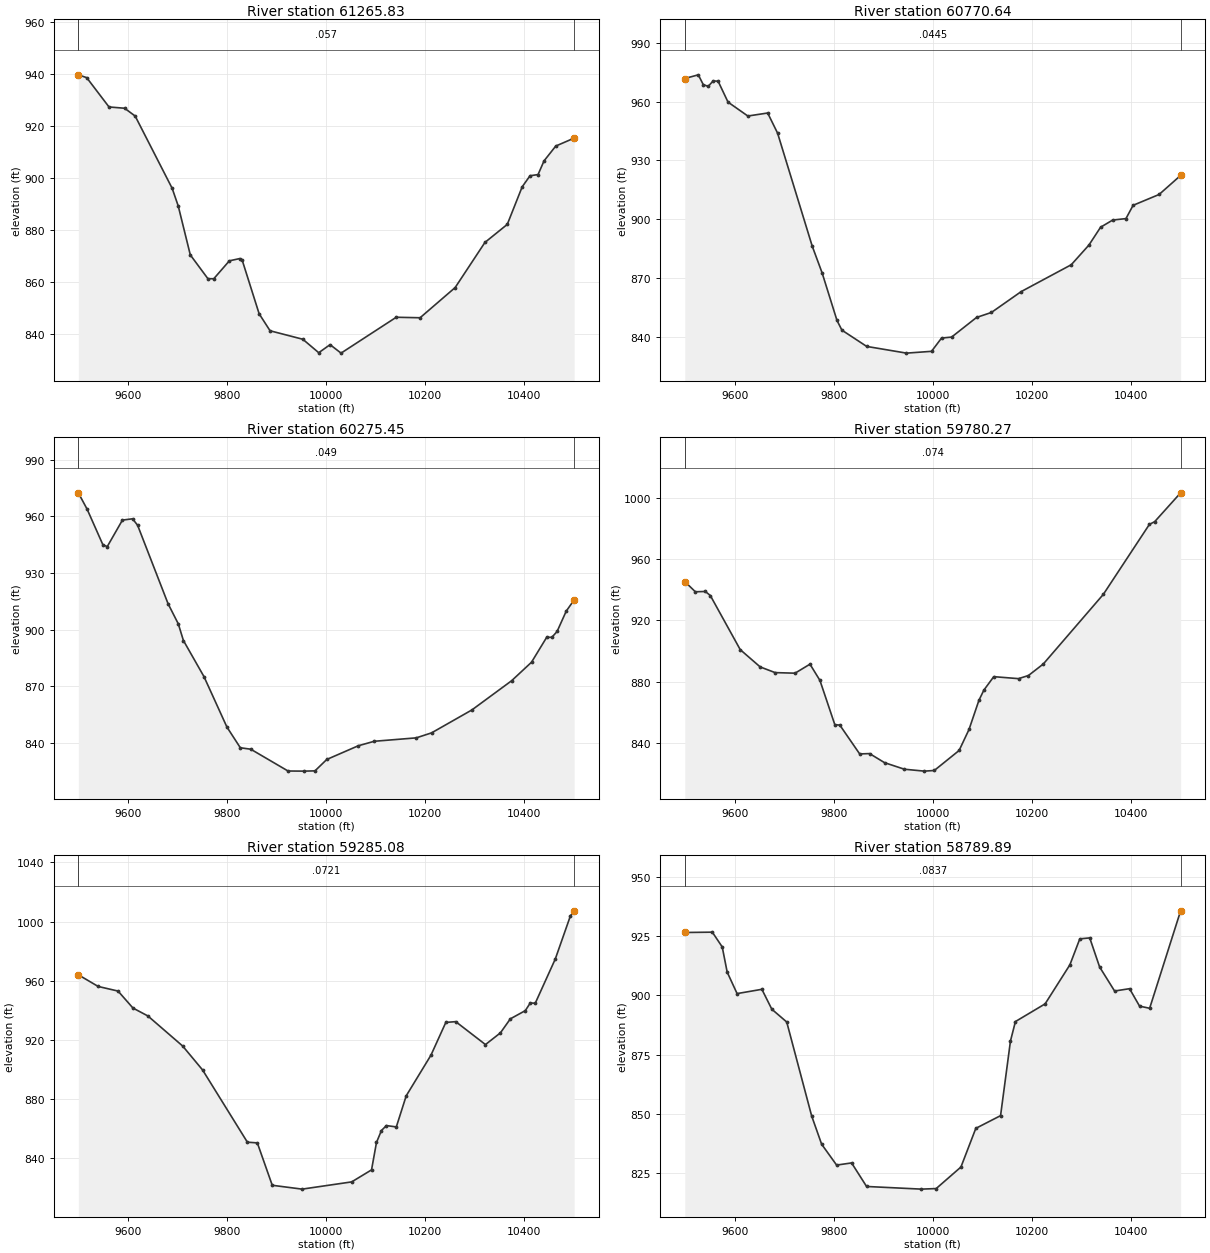
Type RM Length L Ch R = 1 ,61265.83,495.187700,495.187700,495.187700
XS GIS Cut Line= 6
584663.715765188802567.793024831584752.608240686 802672.66748502
584833.441661569802791.402837368585008.391806619803139.582348949
585157.821587229803314.045361631585216.977589306803395.611792052
#Sta/Elev= 30
9499.071939.76529516.009938.6738 9561.04927.38279592.539 926.8899613.925923.8746
9688.674896.02289700.976889.18679725.306870.37519760.853861.21339772.703861.1785
9804.188868.08049824.865868.94749830.099868.38049864.375847.68929886.485841.1298
9952.662837.8651 9984.79832.680210007.73835.7825 10029.9832.518310141.38846.3398
 10189.6846.149810260.45857.790310320.62875.181610365.75 882.13110395.84896.5976
10411.72900.876410427.94901.3267   10440 906.59710463.71912.315510500.88915.3828
#Mann= 3 , 0 , 0
9499.071   0.057       09499.071   0.057       010500.88   0.057       0
#XS Ineff= 2 , 0
       0                               0
Bank Sta=9499.071,10500.88
Exp/Cntr=0.3,0.1

Type RM Length L Ch R = 1 ,60770.64,495.187700,495.187700,495.187700
XS GIS Cut Line= 6
584337.752222541803383.385646354584658.833743262803392.190863747
584932.929793888803360.680672577585041.883743983803364.488628462
585185.084744325803427.335625097585273.850501683803530.927701993
#Sta/Elev= 30
9499.055971.88369526.336973.76039536.348968.76979546.361967.86079556.373970.6576
9566.385970.4929 9586.41 959.8169626.459952.71389666.507954.25399686.518943.9779
9756.518886.24579776.518872.57169806.518848.31329816.518843.31369866.565835.0061
9946.982831.57889997.584832.497610017.87839.284810038.16839.772110088.57849.8108
10118.62852.356810178.75863.016710279.95876.736810315.66886.798210339.16895.8962
10363.69899.573610390.42900.302310404.91907.097110457.41912.629710500.91922.3579
#Mann= 3 , 0 , 0
9499.055  0.0445       09499.055  0.0445       010500.91  0.0445       0
#XS Ineff= 2 , 0
       0                               0
Bank Sta=9499.055,10500.91
Exp/Cntr=0.3,0.1

Type RM Length L Ch R = 1 ,60275.45,495.187800,495.187800,495.187800
XS GIS Cut Line= 6
584377.390641308803993.677207577584667.686899175803925.602257333
 585068.02645545803773.419896421  585204.3710295803757.745102719
585279.902966064803766.974644459585336.741711236803788.362592416
#Sta/Elev= 30
9499.028972.38959516.912963.6617 9548.77944.83039557.535943.95469588.128957.9508
9608.586958.64219618.816 955.2149680.352913.68269701.023903.02849711.359 894.207
9752.854875.1193 9799.31848.38059826.374837.4252 9847.54836.65379922.763825.1172
9955.454825.05349977.248825.1931   10001831.219610064.63838.471210097.01840.8565
10181.74842.661110212.81845.304910294.32 857.44710374.51872.889810414.78882.7033
10445.42895.891910455.94 895.91410466.45 898.97510484.97 909.76510500.97 915.714
#Mann= 3 , 0 , 0
9499.028   0.049       09499.028   0.049       010500.97   0.049       0
#XS Ineff= 2 , 0
       0                               0
Bank Sta=9499.028,10500.97
Exp/Cntr=0.3,0.1

Type RM Length L Ch R = 1 ,59780.27,495.187700,495.187700,495.187700
XS GIS Cut Line= 6
584533.842288017804354.176059807584809.528613347804321.642940972
585159.181218649804293.531818315585359.838423022804310.844523228
585426.993416964804326.288924685585523.882958962804360.578886813
#Sta/Elev= 30
9499.005945.16459520.326938.52349540.481938.72119550.558936.08899611.021900.7849
9651.329889.50849681.519885.80319721.758885.42579751.937891.30669772.056880.7246
9802.181851.8157 9812.22851.58949852.374832.76749872.451832.98899902.567827.0776
9942.751822.79089982.985821.5521 10003.1821.965910053.28835.0121 10073.3848.7076
10093.31867.704310103.32874.387910123.33 883.16210173.37881.866910193.38883.9053
10223.41891.416310344.71936.830310437.79 982.46110448.51984.2549 10500.91003.054
#Mann= 3 , 0 , 0
9499.005   0.074       09499.005   0.074       0 10500.9   0.074       0
#XS Ineff= 2 , 0
       0                               0
Bank Sta=9499.005,10500.9
Exp/Cntr=0.3,0.1

Type RM Length L Ch R = 1 ,59285.08,495.187700,495.187700,495.187700
XS GIS Cut Line= 6
584445.063773957804829.453441748584889.765648051 804784.80136162
 585084.32185622804772.607185241585169.727533238 804772.60998738
 585273.39134554804778.308296291585442.583922563804801.365905162
#Sta/Elev= 30
9499.006964.03879539.102956.15169579.261953.0374 9609.38941.56369639.528 936.213
9709.909915.85659750.127899.67629840.618850.86919860.727850.3887 9890.89821.7271
9951.204819.128310051.43824.0219 10091.5832.139410101.51850.689510111.53858.7575
10121.54862.100110141.58861.185310161.58882.223310211.58909.6953 10241.6 931.843
10261.63932.362410321.72916.866510351.87924.753310372.01934.2569 10402.2939.8064
10412.27944.969710422.33944.818910462.81974.709110493.251003.74510500.951007.287
#Mann= 3 , 0 , 0
9499.006  0.0721       09499.006  0.0721       010500.95  0.0721       0
#XS Ineff= 2 , 0
       0                               0
Bank Sta=9499.006,10500.95
Exp/Cntr=0.3,0.1

Type RM Length L Ch R = 1 ,58789.89,695.628500,695.628500,695.628500
XS GIS Cut Line= 6
584569.390158827805296.780397742584706.426924899805294.537898379
585013.174109591805258.333044233585248.932451774805247.845793048
585413.399440092805254.203788979585566.390400274805279.921614286
#Sta/Elev= 30
9499.033926.55669554.647926.69639574.659920.47389584.667909.85189604.683 900.781
9654.787902.59179674.873894.19619705.003888.79729755.356849.18549775.539837.2426
9805.812828.43999836.086829.3513 9866.36819.41839976.954818.298410007.01818.5345
10057.04827.625810087.07843.9315 10137.1849.296610157.12 880.79510167.12888.9844
10227.14896.452410277.17912.910410297.22923.869910317.27924.277510337.31911.9878
10367.52901.869410397.77902.853710417.96895.493210438.36894.589110500.95935.6969
#Mann= 3 , 0 , 0
9499.033  0.0837       09499.033  0.0837       010500.95  0.0837       0
#XS Ineff= 2 , 0
       0                               0
Bank Sta=9499.033,10500.95
Exp/Cntr=0.3,0.1

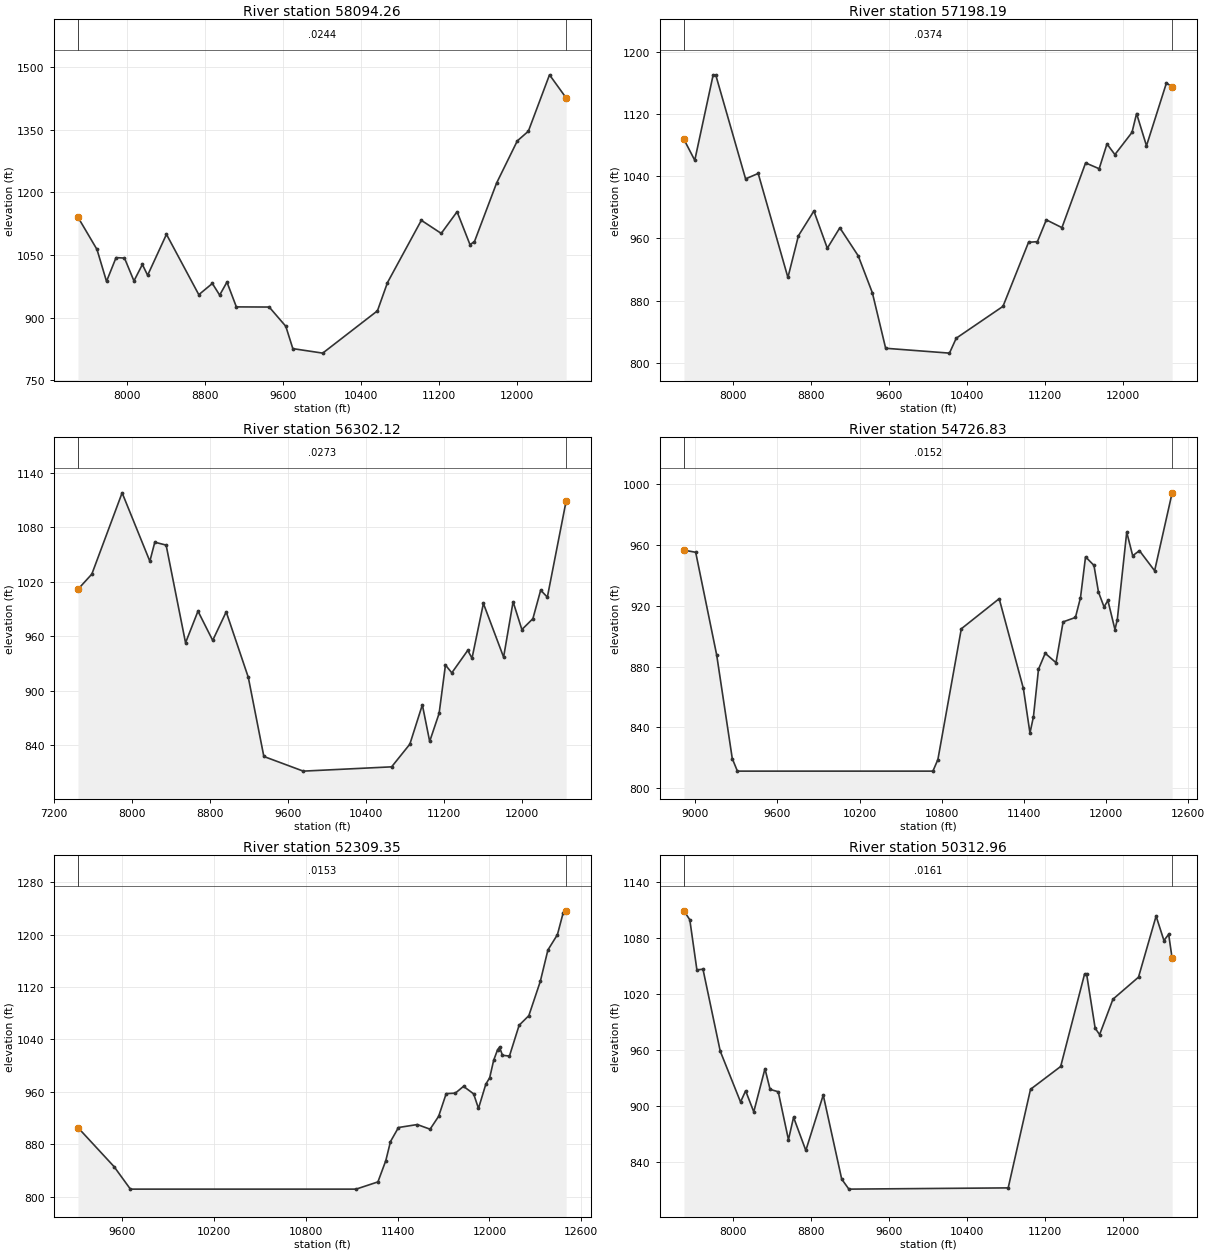
Type RM Length L Ch R = 1 ,58094.26,896.069100,896.069100,896.069100
XS GIS Cut Line= 6
582705.031192808804798.681848588584373.416288104805456.071599837
584776.015377485805672.969567898584873.963823529805776.107067253
585093.995952797806141.536006008 586427.28575741807865.597276214
#Sta/Elev= 30
7499.1311140.6487694.2661063.191 7791.85986.66447889.4341043.6927975.948 1042.63
8072.915987.76988159.1081027.2118212.9781001.3688405.9941099.5688737.341 954.814
8876.193981.73328950.959953.78099025.726985.04359122.075925.53559458.605925.1818
9628.684878.99729700.604825.485110006.81814.6799 10567.5 916.107 10670.3983.7786
11017.261133.15711221.161101.74811383.531153.73711515.741074.82111561.821082.261
11787.871222.29512000.331323.55712113.631346.726 12330.4 1481.9912500.951426.625
#Mann= 3 , 0 , 0
7499.131  0.0244       07499.131  0.0244       012500.95  0.0244       0
#XS Ineff= 2 , 0
       0                               0
Bank Sta=7499.131,12500.95
Exp/Cntr=0.3,0.1

Type RM Length L Ch R = 1 ,57198.19,896.069300,896.069300,896.069300
XS GIS Cut Line= 6
582206.775878201804785.991858164 583239.98733343805377.012545775
 583589.20938432805640.652926213583830.661994778805879.636090923
584220.174120712806426.443053585585396.236919709808473.011812901
#Sta/Elev= 30
7499.0571087.6337609.9661060.6787798.392 1170.697824.523 1170.828130.6571036.731
8259.8221043.7378564.408909.66618672.071963.45528830.427995.3095 8967.96947.3605
9096.312973.7048 9285.05937.50129429.644889.90569565.783818.4455 10219.5812.1897
10288.91831.4354 10767.9872.482711029.55954.959711120.57955.864911211.79983.9261
11371.86973.915611614.371057.32611753.281049.80711833.341081.78211914.481068.054
12089.641096.62312136.631120.93112238.111079.36512442.841160.46712500.981154.961
#Mann= 3 , 0 , 0
7499.057  0.0374       07499.057  0.0374       012500.98  0.0374       0
#XS Ineff= 2 , 0
       0                               0
Bank Sta=7499.057,12500.98
Exp/Cntr=0.3,0.1

Type RM Length L Ch R = 1 ,56302.12,1575.295500,1575.295500,1575.295500
XS GIS Cut Line= 6
581743.239440571804849.389583512582546.789604359805415.256106512
583069.974306303806027.591707609583266.798434287806441.858246047
583750.463732141807876.955327837584298.028514445808982.388923414
#Sta/Elev= 30
7449.5951011.7867591.8371028.5577902.1531118.1748186.2881042.7418236.9351063.719
8353.0151060.5418551.994 952.8178679.321987.72688830.135 955.4668968.508986.9459
9195.077914.67999354.239827.49229758.061811.330710663.43 816.05910850.05841.0636
10978.25884.443811053.31844.084511150.08875.075711214.83928.307111280.09 919.693
11443.29944.493811487.03935.832811603.66996.2299 11810.6936.990111907.94998.0811
11997.94967.419212110.66979.406212190.471010.81312258.88 1003.1512451.531109.297
#Mann= 3 , 0 , 0
7449.595  0.0273       07449.595  0.0273       012451.53  0.0273       0
#XS Ineff= 2 , 0
       0                               0
Bank Sta=7449.595,12451.53
Exp/Cntr=0.3,0.1

Type RM Length L Ch R = 1 ,54726.83,2417.479000,2417.479000,2417.479000
XS GIS Cut Line= 6
581292.554991595806389.993915539581463.832276486806598.123766358
581680.547121443806908.139854898582016.317381821807540.924593149
 582184.08427178807817.085336832583270.820320506809347.219523115
#Sta/Elev= 30
8917.585956.52449003.287955.1231 9156.79887.57319270.498819.58589307.877811.3307
10735.44811.330710771.76818.917810942.85904.857411219.43924.627211396.09865.6431
11444.14836.333211469.65847.139711506.43878.281411555.47888.773311634.28882.5782
11686.14909.388611776.15912.307111813.04925.282611849.92952.1296 11911.4946.5138
11944.46928.966611985.17919.215312013.21 923.45312064.77904.346112081.96910.9422
 12150.7968.329612194.19 952.86812243.56956.172612354.45942.9987 12482.3994.1845
#Mann= 3 , 0 , 0
8917.585  0.0152       08917.585  0.0152       0 12482.3  0.0152       0
#XS Ineff= 2 , 0
       0                               0
Bank Sta=8917.585,12482.3
Exp/Cntr=0.3,0.1

Type RM Length L Ch R = 1 ,52309.35,1996.387300,1996.387300,1996.387300
XS GIS Cut Line= 6
580001.678888931808373.981083304580233.318260452808717.927716811
580640.246806469809537.752717406580865.852927334809867.773097442
581290.960909468810337.334324922581930.942846326810856.743804364
#Sta/Elev= 30
9311.194 905.3479547.393845.63969653.891811.330711128.34811.330711271.13 822.371
11322.72854.960311353.05883.931911405.22905.420511528.04909.971911611.88902.8693
11667.77922.551211717.13957.187511776.36957.882711830.41 968.31111896.38956.8375
11928.09934.6042 11976.1971.666412001.36 981.44912027.181008.02212053.091024.369
 12065.91028.10312084.721015.73512130.37 1014.5612193.741061.64512257.111076.291
12332.031128.63812381.731176.58212443.851199.97512481.141233.07112500.931236.392
#Mann= 3 , 0 , 0
9311.194  0.0153       09311.194  0.0153       012500.93  0.0153       0
#XS Ineff= 2 , 0
       0                               0
Bank Sta=9311.194,12500.93
Exp/Cntr=0.3,0.1

Type RM Length L Ch R = 1 ,50312.96,1996.387400,1996.387400,1996.387400
XS GIS Cut Line= 6
576287.079507659809043.264081025577979.220667798809554.689059408
578502.045609428809731.475787543579258.553483052 810019.41595875
579711.555136189810230.613026309580919.315117083810881.657368152
#Sta/Elev= 30
7499.0361109.1817559.1491099.584  7631.8 1045.987694.0721046.7027870.598 959.101
8078.972904.59428131.065916.55628214.415894.04258329.163940.18378381.491918.1037
8465.217915.53368569.875864.16898622.203 888.2258747.792 852.7418926.254912.0071
9115.414822.04929188.977811.330710821.22812.658311049.85918.166111358.97942.5951
11603.391041.355 11624.21041.83211712.11983.593211757.73976.670211894.58 1014.61
12156.251038.18412336.561103.55612416.951077.36612465.231084.08112500.951058.257
#Mann= 3 , 0 , 0
7499.036  0.0161       07499.036  0.0161       012500.95  0.0161       0
#XS Ineff= 2 , 0
       0                               0
Bank Sta=7499.036,12500.95
Exp/Cntr=0.3,0.1

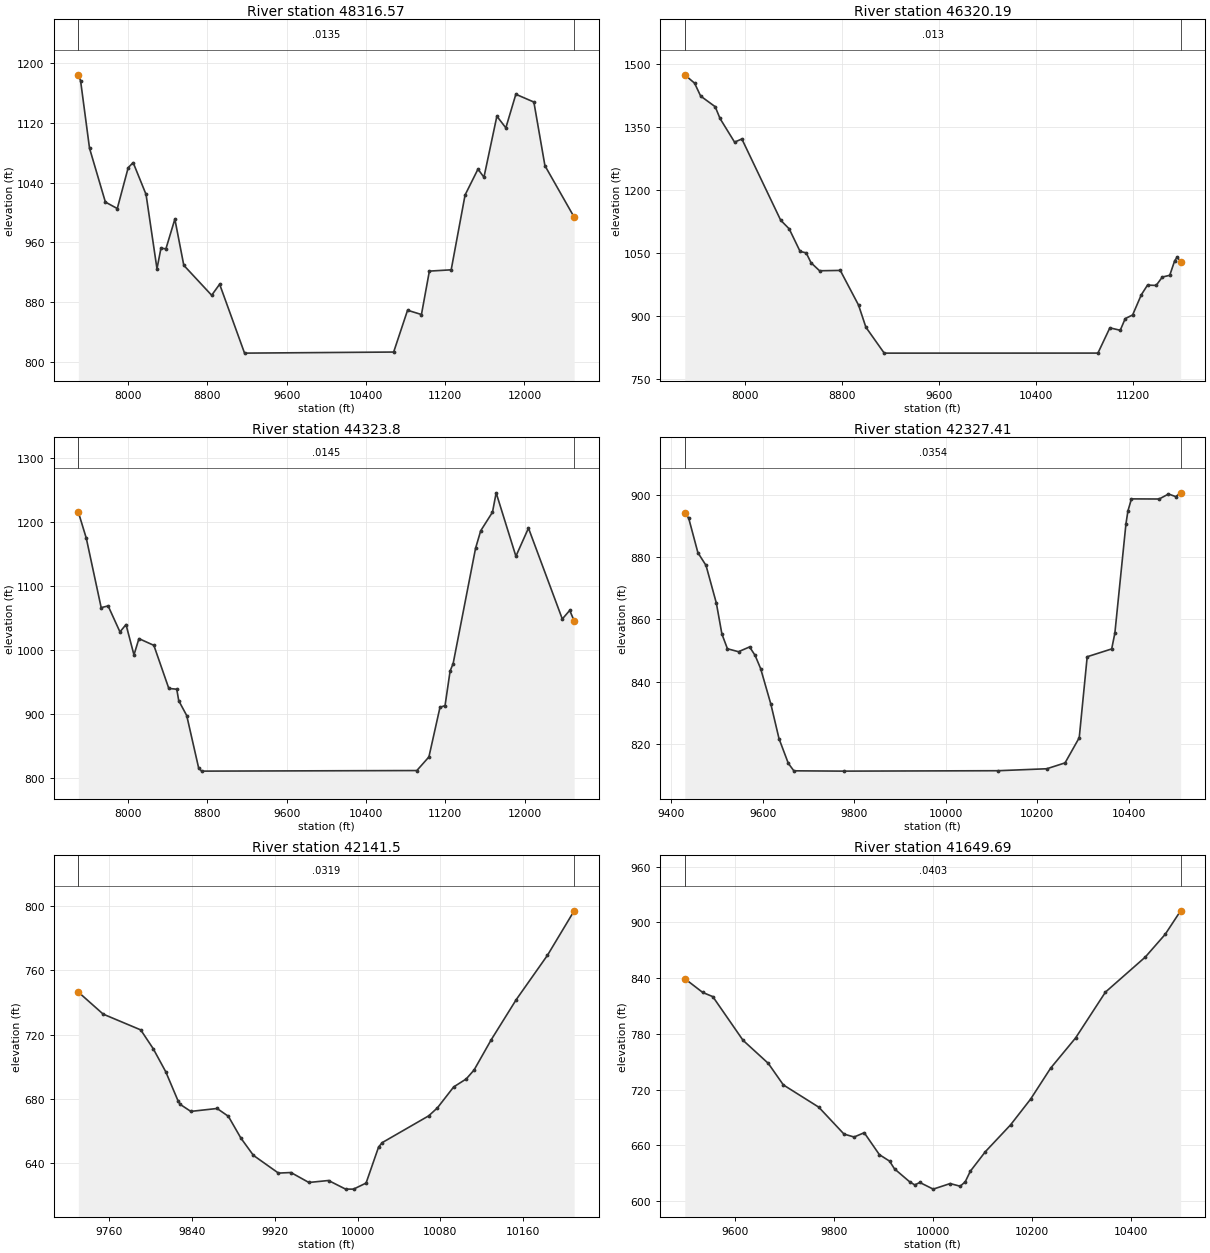
Type RM Length L Ch R = 1 ,48316.57,1996.387300,1996.387300,1996.387300
XS GIS Cut Line= 6
576542.164178525811884.145033904577328.405478296811857.690075574
578788.379719699811721.976111946580061.870307978811660.698290819
580693.048182261811679.734159096581524.422061188811809.187029831
#Sta/Elev= 30
7499.0351184.3817521.8761176.2927611.893 1086.017771.924 1013.847891.9651005.146
8002.036 1059.928052.098 1066.74 8182.261024.0368292.403924.40378332.495951.9671
8382.609951.15118472.815 990.9658563.063929.04788844.098888.88318924.503903.7119
9175.848811.330710680.09812.783810820.32868.822510960.43863.079511040.46921.2617
11260.47923.008311400.531023.298 11530.71057.99311590.871047.10111721.381128.913
11811.86 1113.2811912.69 1158.3312094.611147.89512206.191062.56312500.98993.6477
#Mann= 3 , 0 , 0
7499.035  0.0135       07499.035  0.0135       012500.98  0.0135       0
#XS Ineff= 2 , 0
       0                               0
Bank Sta=7499.035,12500.98
Exp/Cntr=0.3,0.1

Type RM Length L Ch R = 1 ,46320.19,1996.387300,1996.387300,1996.387300
XS GIS Cut Line= 6
576754.256267715814007.491273803577764.849469949 813944.27274078
578543.381346329 813845.64298016578995.283181914 813757.46444597
579616.835333833813592.880665257580783.191511087813334.070330581
#Sta/Elev= 30
7499.0451473.486 7579.871453.6387629.9211422.9687750.0421397.6487790.0821369.585
7910.2811313.315 7970.381320.8978291.1151127.5578361.3561107.0488451.6671053.228
8501.8391049.901 8542.031026.2918612.3941007.2878783.3551008.1048934.449925.5564
8994.995872.95869146.426811.330710911.81811.419111010.37871.482411096.13865.7038
11137.09893.405611198.52902.1867 11270.2950.1489 11321.4973.163811392.83972.4443
11443.83992.346411505.03996.511111545.831031.01111566.231039.77211594.981028.786
#Mann= 3 , 0 , 0
7499.045   0.013       07499.045   0.013       011594.98   0.013       0
#XS Ineff= 2 , 0
       0                               0
Bank Sta=7499.045,11594.98
Exp/Cntr=0.3,0.1

Type RM Length L Ch R = 1 , 44323.8,1996.387300,1996.387300,1996.387300
XS GIS Cut Line= 6
577364.882241988815432.085121339579278.360481059 815593.28945795
579770.490254824815596.483504573581167.809451276815403.925836474
581745.152990219815241.504958167582286.697407901815042.482627415
#Sta/Elev= 30
7499.0721215.7377579.3051174.965 7729.521066.5537799.6381069.2647918.9731028.661
 7980.081040.152 8060.32992.73838110.4691018.1858261.0171007.6758411.656 940.506
8491.996939.16358512.082921.24158592.475898.06258713.092816.09298743.247811.3307
10914.06812.247611035.66833.480811147.49910.990311198.43913.553611249.53 967.609
11280.19979.265811506.351159.20811558.131186.52711677.061215.581 11714.1 1245.78
11913.271146.774 12040.11190.74812381.351048.826 12456.31062.29512500.951045.871
#Mann= 3 , 0 , 0
7499.072  0.0145       07499.072  0.0145       012500.95  0.0145       0
#XS Ineff= 2 , 0
       0                               0
Bank Sta=7499.072,12500.95
Exp/Cntr=0.3,0.1

Type RM Length L Ch R = 1 ,42327.41,185.910200,185.910200,185.910200
XS GIS Cut Line= 2
578397.967598539816928.854123068579293.800931853817539.965234173
#Sta/Elev= 30
9429.128894.15749437.641892.44249457.779881.37089475.524877.29729498.167865.1904
9510.272855.29879522.377 850.5689546.588849.62219570.798851.15819582.903848.4376
9595.009844.20679617.485832.7339 9635.23821.72659655.535813.8229 9667.64811.4328
9776.586811.330710114.35811.462610220.82 812.09110260.79813.9746 10291.8822.0446
10309.21848.010410362.78850.513710369.74855.589410393.95890.581410398.27894.7535
10406.06898.626410466.58898.5873   10487900.1829 10502.9899.363410513.55  900.57
#Mann= 3 , 0 , 0
9429.128  0.0354       09429.128  0.0354       010513.55  0.0354       0
#XS Ineff= 2 , 0
       0                               0
Bank Sta=9429.128,10513.55
Exp/Cntr=0.3,0.1

Type RM Length L Ch R = 1 , 42141.5,491.813100,491.813100,491.813100
XS GIS Cut Line= 2
578555.149296284 817259.40487738578951.237583011817529.534053743
#Sta/Elev= 30
 9729.93746.44849753.958732.7278 9790.27722.92089802.374711.19419814.479696.8592
9826.583678.43519828.602676.52199838.687672.22649864.098674.0408    9875669.1802
9887.104655.62879899.208644.88729923.416633.85559935.521634.2058 9952.84628.0177
9971.833629.24599988.336623.89169996.041623.879610008.15627.642910020.25650.0646
10023.83652.833810068.67669.450410077.08674.382410092.87687.449610104.98692.4053
10112.57697.956610129.19716.8204 10153.4741.797210183.57769.360610209.36796.9831
#Mann= 3 , 0 , 0
 9729.93  0.0319       0 9729.93  0.0319       010209.36  0.0319       0
#XS Ineff= 2 , 0
       0                               0
Bank Sta=9729.93,10209.36
Exp/Cntr=0.3,0.1

Type RM Length L Ch R = 1 ,41649.69,491.813100,491.813100,491.813100
XS GIS Cut Line= 6
578209.398442297817941.685922085 578415.39946067  817902.1611909
 578721.83329413817838.216729983578867.662412868 817810.24760317
578997.003098424817792.165144172579196.101030246817772.262511763
#Sta/Elev= 30
9499.003839.38789535.254824.53669555.619820.04869616.714773.00959667.626748.2529
9698.173724.99769769.649701.07519820.728 672.0659841.159668.91399861.591673.5461
9892.238649.9058 9912.67643.00319922.886 634.5519953.533620.63589963.749617.3205
9973.965619.9645   10001612.8008 10035.2618.788410055.57615.915810065.75620.7347
10075.93632.033210106.48653.176810157.39682.034510197.89709.769110238.28 743.059
10288.76775.601110349.12824.969810429.52862.628710469.72887.096710500.97912.4321
#Mann= 3 , 0 , 0
9499.003  0.0403       09499.003  0.0403       010500.97  0.0403       0
#XS Ineff= 2 , 0
       0                               0
Bank Sta=9499.003,10500.97
Exp/Cntr=0.3,0.1

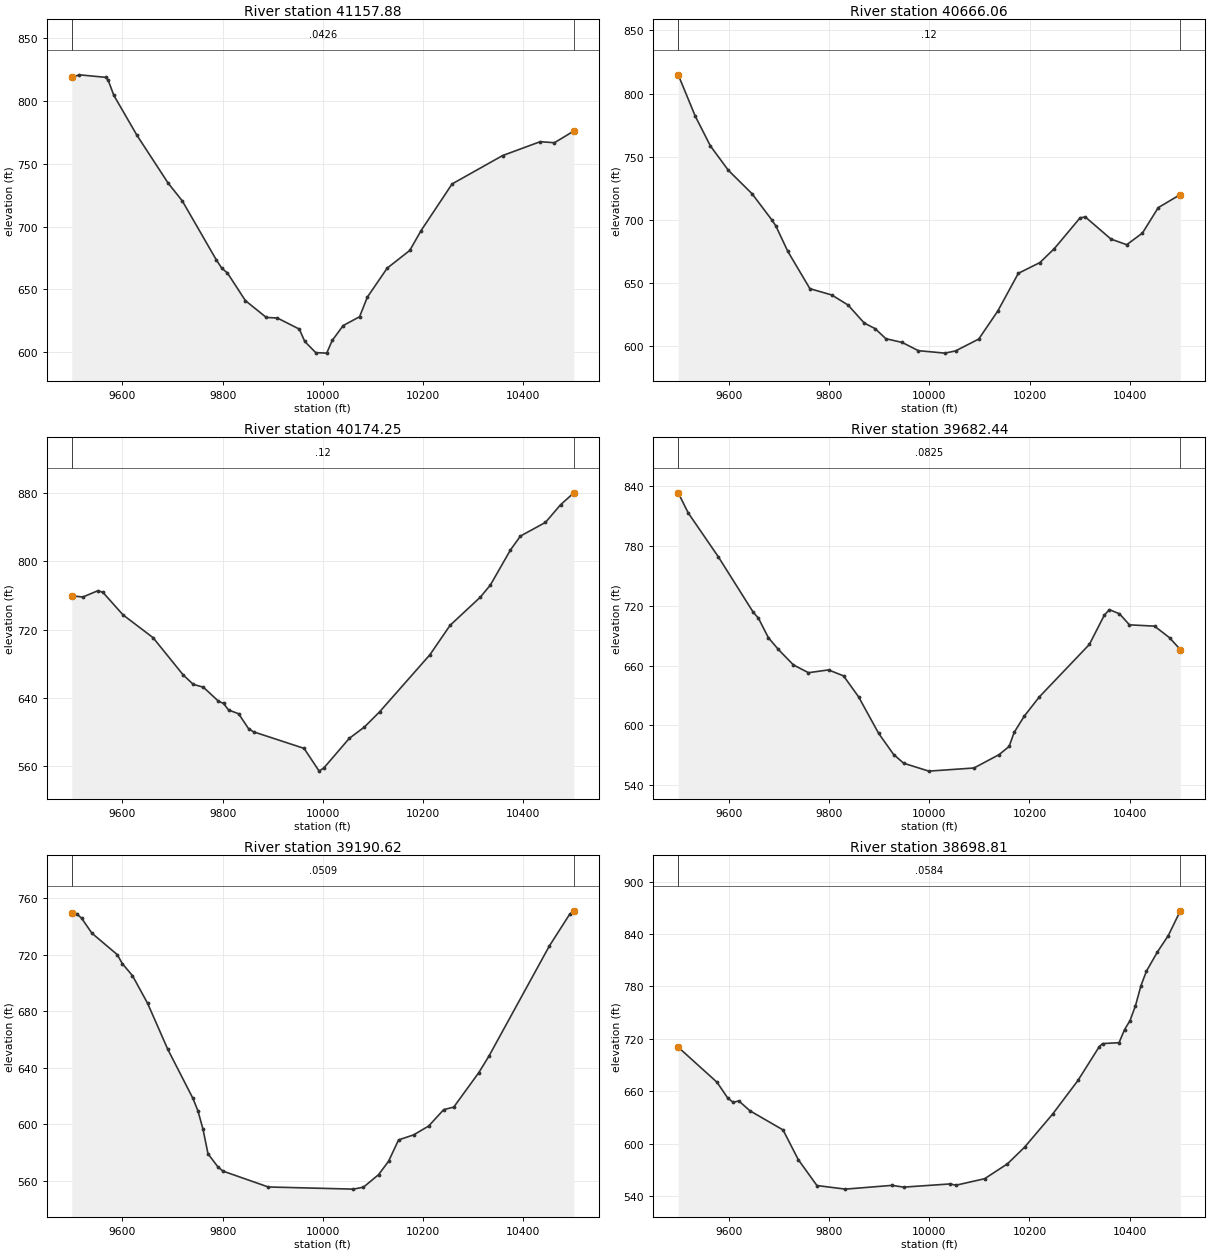
Type RM Length L Ch R = 1 ,41157.88,491.813000,491.813000,491.813000
XS GIS Cut Line= 6
578421.609325096818527.973100672578689.440546965818383.078215431
578974.521959092818253.742390242579053.734227732818212.760869569
 579157.31036383818142.858365059579282.899379635818028.317755711
#Sta/Elev= 30
9499.014 818.9699514.321820.85889567.075818.85099571.476 816.8159582.907804.5537
9628.999772.78689691.358734.63699719.574720.49799787.259673.6767 9798.54666.8243
9809.709663.08459845.535641.08719887.266 627.7239909.305627.2723 9953.07618.4426
9964.012608.57619985.895599.712410007.78599.317710018.72609.374410040.59621.2633
 10073.4628.294310088.82643.877510128.42666.965910173.46681.043910195.97696.8028
10257.96734.002710358.62756.5704 10433.7767.626510462.14766.812110500.92 776.122
#Mann= 3 , 0 , 0
9499.014  0.0426       09499.014  0.0426       010500.92  0.0426       0
#XS Ineff= 2 , 0
       0                               0
Bank Sta=9499.014,10500.92
Exp/Cntr=0.3,0.1

Type RM Length L Ch R = 1 ,40666.06,491.813100,491.813100,491.813100
XS GIS Cut Line= 6
578989.553124235819102.223696763579083.563413538818908.902111643
579185.033624965818664.920655971579233.792512477818523.212055468
579287.782714186818293.821178658579330.653269953 818163.64945809
#Sta/Elev= 30
9499.022814.91889532.977782.2397 9563.28758.6184 9599.11739.34549646.436720.7807
9685.229700.42229693.761695.38929717.678675.23269761.773645.70469805.277640.7346
9837.835632.78689870.225618.49049891.818614.10829913.411606.0926  9945.8603.1774
 9978.19596.642810031.16594.698510052.43596.446410098.67605.8384 10136.6627.9655
 10177.7657.868210220.73666.346410249.61677.451810300.98701.764210311.25702.4833
10362.62684.942210393.94680.490610425.28689.675610456.93709.842710500.93720.1909
#Mann= 3 , 0 , 0
9499.022    0.12       09499.022    0.12       010500.93    0.12       0
#XS Ineff= 2 , 0
       0                               0
Bank Sta=9499.022,10500.93
Exp/Cntr=0.3,0.1

Type RM Length L Ch R = 1 ,40174.25,491.813100,491.813100,491.813100
XS GIS Cut Line= 6
579680.688198661819047.214385167579682.500313717818935.766259123
579677.318930173818826.114256245579618.606115107818218.462028215
579616.979495525818109.314472097 579621.55605509818048.595220525
#Sta/Elev= 30
9499.056759.69999521.274758.34279551.278765.73929561.279763.75789601.284737.4305
9661.342710.71589721.414667.09119741.523656.06819761.632 652.7589791.796636.3631
 9801.85 633.7699811.904626.09189832.013621.65989852.122603.97769862.177600.4369
 9962.63581.12239992.697554.489810002.72558.635810052.84592.846110082.96606.1075
10113.16623.798210213.82690.804810254.07725.246510314.28758.123110334.34772.3255
10374.36813.337510394.37 829.67610444.39845.716310474.48866.349710500.96880.2971
#Mann= 3 , 0 , 0
9499.056    0.12       09499.056    0.12       010500.96    0.12       0
#XS Ineff= 2 , 0
       0                               0
Bank Sta=9499.056,10500.96
Exp/Cntr=0.3,0.1

Type RM Length L Ch R = 1 ,39682.44,491.813100,491.813100,491.813100
XS GIS Cut Line= 6
580146.005602093819014.782216067580151.152612672 818869.10905099
580150.518459374818738.384646716 580127.01391657818240.841344425
580124.760977142818114.335157825580127.523360301818013.560400643
#Sta/Elev= 30
9499.025833.55369518.819813.51089578.857769.46789648.898 713.5369658.898707.8718
9678.898 688.1869698.898676.30059728.899660.80959758.899653.00359798.913 655.809
 9828.93 649.8079858.948628.77869898.971592.0963 9928.99570.83479949.023562.1047
9999.105554.199210089.26557.348210139.34570.772310159.36579.002210169.37 593.051
10189.39609.252910219.42628.610410319.49681.383210349.49710.911910359.49716.2854
 10379.5712.1601 10399.5701.051110449.52 699.73910479.53688.092510500.98676.2272
#Mann= 3 , 0 , 0
9499.025  0.0825       09499.025  0.0825       010500.98  0.0825       0
#XS Ineff= 2 , 0
       0                               0
Bank Sta=9499.025,10500.98
Exp/Cntr=0.3,0.1

Type RM Length L Ch R = 1 ,39190.62,491.813100,491.813100,491.813100
XS GIS Cut Line= 6
580591.059077704818984.720803051580611.462133027818847.669035526
580626.463005101818691.823770106580632.461638288818558.926651419
580633.483426227818262.341166667580660.133492231817986.650879532
#Sta/Elev= 30
9499.042749.2901 9508.87749.0009 9518.98745.7156  9539.2 735.2389589.751720.0849
9599.861713.70999620.082705.21279650.348685.58159690.584 653.051 9740.84618.2398
9750.872 609.3529760.903596.44449770.935578.99579790.999569.59319801.016566.7298
9891.108555.514410061.16553.989910081.17555.388710111.18564.216510131.19573.6917
10151.19588.854110181.21592.394310211.22 598.66710241.26610.285710261.31612.0884
10311.44636.573510331.49648.197210452.15726.225910492.54748.591910500.96751.0713
#Mann= 3 , 0 , 0
9499.042  0.0509       09499.042  0.0509       010500.96  0.0509       0
#XS Ineff= 2 , 0
       0                               0
Bank Sta=9499.042,10500.96
Exp/Cntr=0.3,0.1

Type RM Length L Ch R = 1 ,38698.81,491.813100,491.813100,491.813100
XS GIS Cut Line= 6
580877.993081266819026.665224979580919.435884217818925.078126729
580969.521539473818817.920727903581190.844006125 818428.13731312
581263.423461293818281.017269528581328.429403432 818133.09666123
#Sta/Elev= 30
9499.037710.36619576.436670.27839598.036652.01739608.838647.23329619.877648.9297
9641.954637.66659708.184615.68319738.595581.68539775.782  552.029832.635547.8994
9925.658552.21419948.914550.185910041.79 553.85510053.26552.390910110.38559.7923
10156.08 576.89310190.09595.852710246.22 633.83610296.65672.271310339.41711.1698
10345.98714.544810378.75715.547610389.67730.502610400.59740.814310411.52757.8472
10422.44780.908310433.36797.421410455.21819.355210477.05838.241810500.98866.5124
#Mann= 3 , 0 , 0
9499.037  0.0584       09499.037  0.0584       010500.98  0.0584       0
#XS Ineff= 2 , 0
       0                               0
Bank Sta=9499.037,10500.98
Exp/Cntr=0.3,0.1

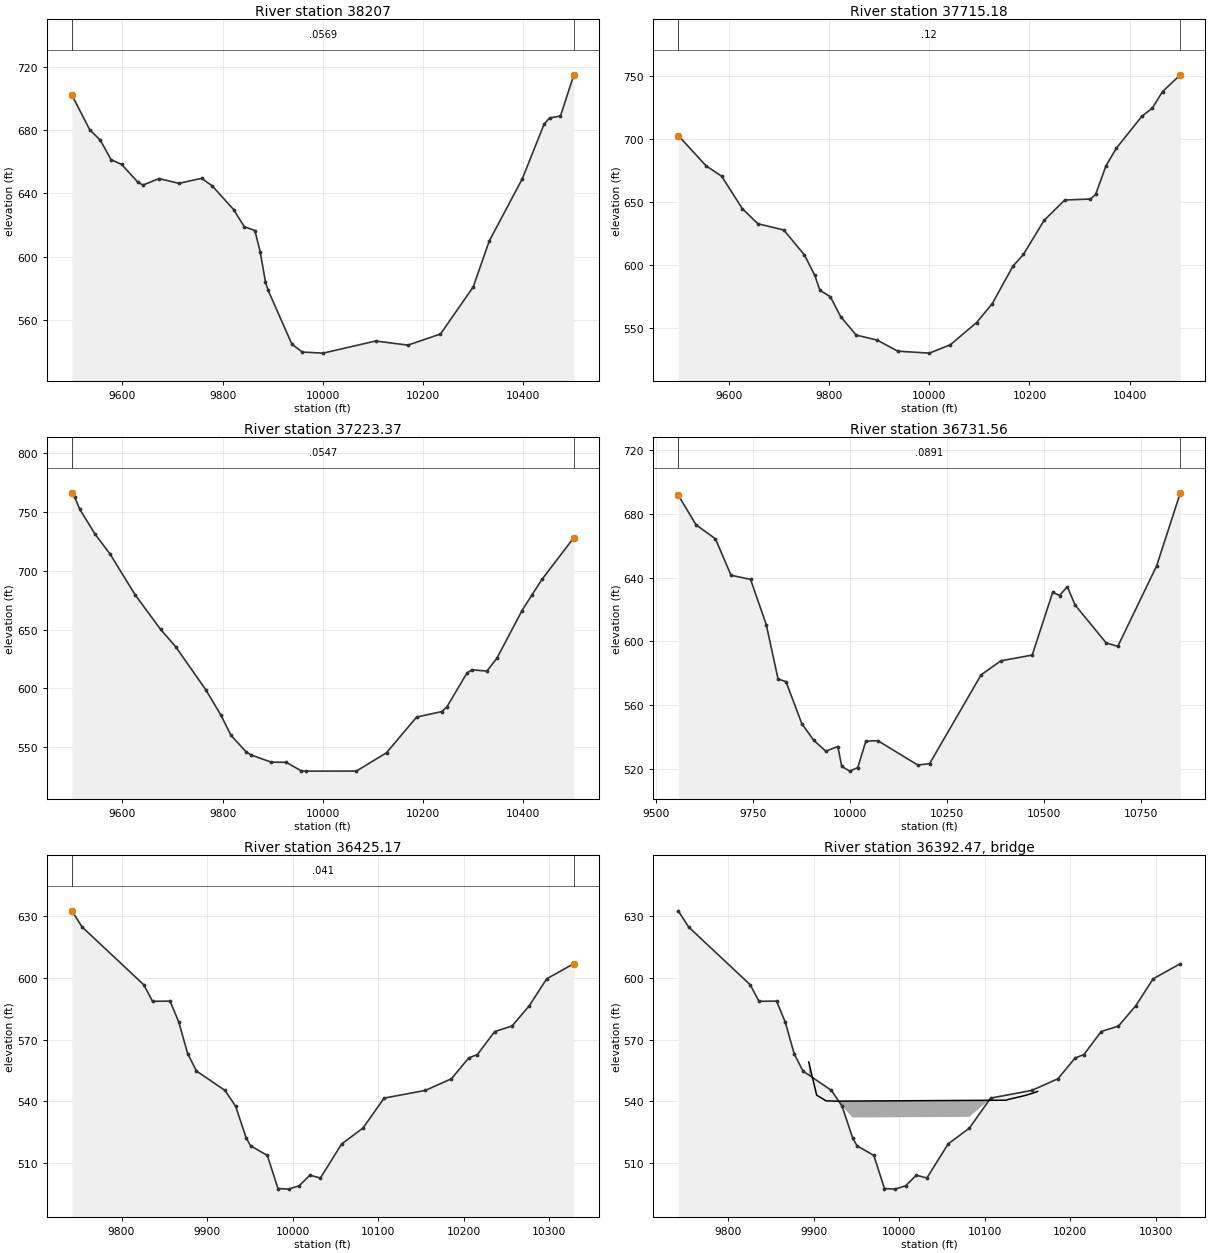
Type RM Length L Ch R = 1 ,   38207,491.813000,491.813000,491.813000
XS GIS Cut Line= 6
581312.260618247819338.648797767581440.037565756818985.380543489
581463.143857604818913.720720608581491.619653369818812.694100694
581511.759637704818754.396513163581661.630308353818400.478030225
#Sta/Elev= 30
9499.013702.21959534.795680.18179556.063673.48539577.331661.33669598.599 658.227
9630.501  647.199641.135645.18939673.037649.32479712.868646.3178 9758.11649.4762
9779.378644.69659821.914629.76499843.182618.9597 9864.45616.49789875.079 602.922
9885.586583.9924 9890.85578.77229938.121544.85149959.026539.771110000.55539.0915
 10105.4546.733710169.88544.152110234.85551.170310300.15580.872310332.16609.9205
 10398.1649.175210441.63683.695610452.52 687.56610474.29688.823310500.97714.8282
#Mann= 3 , 0 , 0
9499.013  0.0569       09499.013  0.0569       010500.97  0.0569       0
#XS Ineff= 2 , 0
       0                               0
Bank Sta=9499.013,10500.97
Exp/Cntr=0.3,0.1

Type RM Length L Ch R = 1 ,37715.18,491.813100,491.813100,491.813100
XS GIS Cut Line= 6
581821.150721858819459.004647437581913.536872867819097.824685341
581976.897688351 818891.28428378582003.527342634818795.578405472
582031.114025097818685.289853202 582076.85377473818490.494772024
#Sta/Elev= 30
9499.009702.49689554.753678.43229585.719670.27859627.007644.54859657.972632.6676
9709.582627.7109 9750.87607.95679771.514591.77179781.836579.9699 9802.48574.8965
9823.124559.1756 9854.09544.53789895.592540.60859937.257531.781610000.15530.2377
10042.06536.866310094.39 554.42610125.53569.340610167.05599.113310187.81608.3154
10229.04635.249210270.27 651.44110321.74652.222710332.01655.858210352.56678.4201
 10373.1692.308410424.46717.8362   10445724.107310465.55737.269210500.99750.5333
#Mann= 3 , 0 , 0
9499.009    0.12       09499.009    0.12       010500.99    0.12       0
#XS Ineff= 2 , 0
       0                               0
Bank Sta=9499.009,10500.99
Exp/Cntr=0.3,0.1

Type RM Length L Ch R = 1 ,37223.37,491.813100,491.813100,491.813100
XS GIS Cut Line= 6
582388.206268411819580.892771963582409.340395589819410.521875961
582426.604469111819209.728331043582430.064067821819127.618916874
582428.844784086818994.238218032582449.838542565818581.646064291
#Sta/Elev= 30
9499.034766.40269504.972 762.7349515.048752.38289545.278731.46319575.508714.3216
9625.892679.40829676.258650.29759706.395635.51249766.669598.80979796.769 577.233
9816.826560.13869846.911546.1629 9856.94543.46489897.005 537.3789927.032537.2332
9957.057529.8958 9967.06529.7286 10067.1529.779410127.15545.381210187.23575.7063
 10237.3580.362810247.31 584.13910287.36 612.91310297.37615.937510327.41 614.809
10347.44625.7514 10397.5666.212810417.53679.705910437.55692.896510500.99728.2865
#Mann= 3 , 0 , 0
9499.034  0.0547       09499.034  0.0547       010500.99  0.0547       0
#XS Ineff= 2 , 0
       0                               0
Bank Sta=9499.034,10500.99
Exp/Cntr=0.3,0.1

Type RM Length L Ch R = 1 ,36731.56,306.391800,306.391800,306.391800
XS GIS Cut Line= 6
 582980.96139864819480.902951458582974.001304221 819336.13504363
582957.901497151819228.157942658582825.949533742818649.073931342
582802.898379487818410.936441664 582808.69428704818203.955598367
#Sta/Elev= 30
9557.351691.58329603.256673.02379653.362 664.2159693.461641.48189743.803638.8492
9784.338610.62929814.767576.55839835.216574.85629876.113548.54439906.908538.1276
9937.866531.38249968.823534.29039979.142521.8183 9999.78518.879710020.42521.1165
10041.06537.607910072.01537.948210174.79522.724210205.54523.518210338.49579.1654
10389.39587.896510470.24591.521310523.07630.802110540.73628.782310560.77634.3319
10580.81622.816610660.94599.121310690.94596.967710790.97 647.24210852.16693.0349
#Mann= 3 , 0 , 0
9557.351  0.0891       09557.351  0.0891       010852.16  0.0891       0
#XS Ineff= 2 , 0
       0                               0
Bank Sta=9557.351,10852.16
Exp/Cntr=0.3,0.1

Type RM Length L Ch R = 1 ,36425.17,59.971600,59.971600,59.971600
XS GIS Cut Line= 4
583218.634837508 819086.90319635583181.134837508818926.486529663
583037.384837538818730.653196335583010.301504165818553.569863006
#Sta/Elev= 30
9741.837632.61989754.061624.72689825.949596.69489836.218 588.6519856.757588.7471
9867.027578.41199877.297563.21879887.566554.78349920.828545.35989933.233537.7606
9945.638522.31789950.745518.44779970.447513.73619982.852497.66719995.257497.3661
10007.66499.022510020.07504.126910032.47502.787810057.28519.329410082.09527.0126
 10106.9541.604110155.23545.361610185.58 551.00410205.81561.146110215.92562.7617
10236.16573.942110256.39576.632910276.62586.516610296.86599.566910328.65606.9441
#Mann= 3 , 0 , 0
9741.837   0.041       09741.837   0.041       010328.65   0.041       0
#XS Ineff= 2 , 0
       0                               0
Bank Sta=9741.837,10328.65
Exp/Cntr=0.3,0.1

Type RM Length L Ch R = 3 ,36392.47,,,
BEGIN DESCRIPTION:
END DESCRIPTION:
Bridge Culvert--1,0,-1,-1, 0
Deck Dist Width WeirC Skew NumUp NumDn MinLoCord MaxHiCord MaxSubmerge Is_Ogee
20.635450,18.700700,2.6,0, 19, 19, , , 0.95, 0, 0,0,,
 9894.39 9903.65 9910.71 9914.52 9916.41 9925.36 9925.36 9926.64 9931.9810105.80
10105.8010125.1210127.1010133.5110141.5710147.3610156.0310161.2010161.94
  559.14  543.02  541.28  540.26  540.24  540.13  540.13  540.12  540.14  540.54
  540.54  540.58  540.90  541.53  542.30  542.88  543.99  544.72  544.83
 -440.86 -456.98 -458.72 -459.74 -459.76 -459.87  532.13  532.12  532.14  532.54
 -459.46 -459.42 -459.10 -458.47 -457.70 -457.12 -456.01 -455.28 -455.17
 9894.39 9903.65 9910.71 9914.52 9916.41 9926.64 9931.98 9945.82 9945.8210125.12
10126.2610126.2610127.1010133.5110141.5710147.3610156.0310161.2010161.94
  559.14  543.02  541.28  540.26  540.24  540.12  540.14  540.18  540.18  540.58
  540.77  540.77  540.90  541.53  542.30  542.88  543.99  544.72  544.83
 -440.86 -456.98 -458.72 -459.74 -459.76 -459.88 -459.86 -459.82  532.18  532.58
  532.77 -459.23 -459.10 -458.47 -457.70 -457.12 -456.01 -455.28 -455.17
BR Coef=-1 , 0 , 0 ,, 0 ,,,0.8,0,1,0,
WSPro=,,,, 1 ,,,, 0 ,,,, 0 ,,,,-1 ,-1 ,-1 , 0 , 0 , 0 , 0 , 0
BC Design=,, 0 ,, 0 ,,,,,,