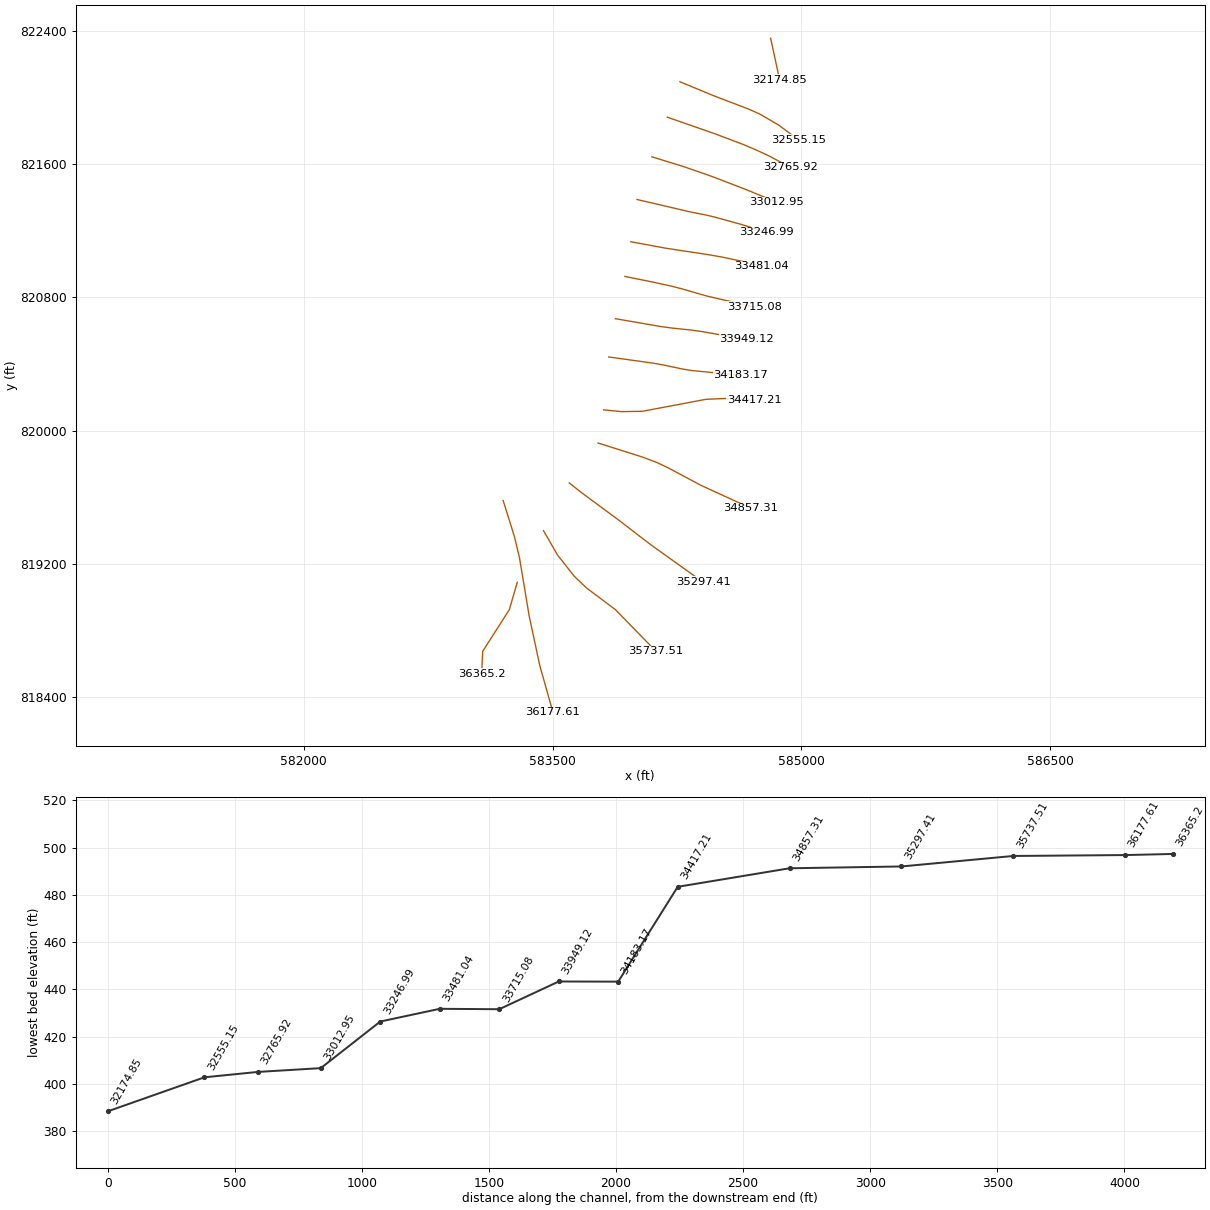
HEC-RAS study 10395_ras.prj: 10395

--- 10395_ras.g01 (geometry) --- (continued)

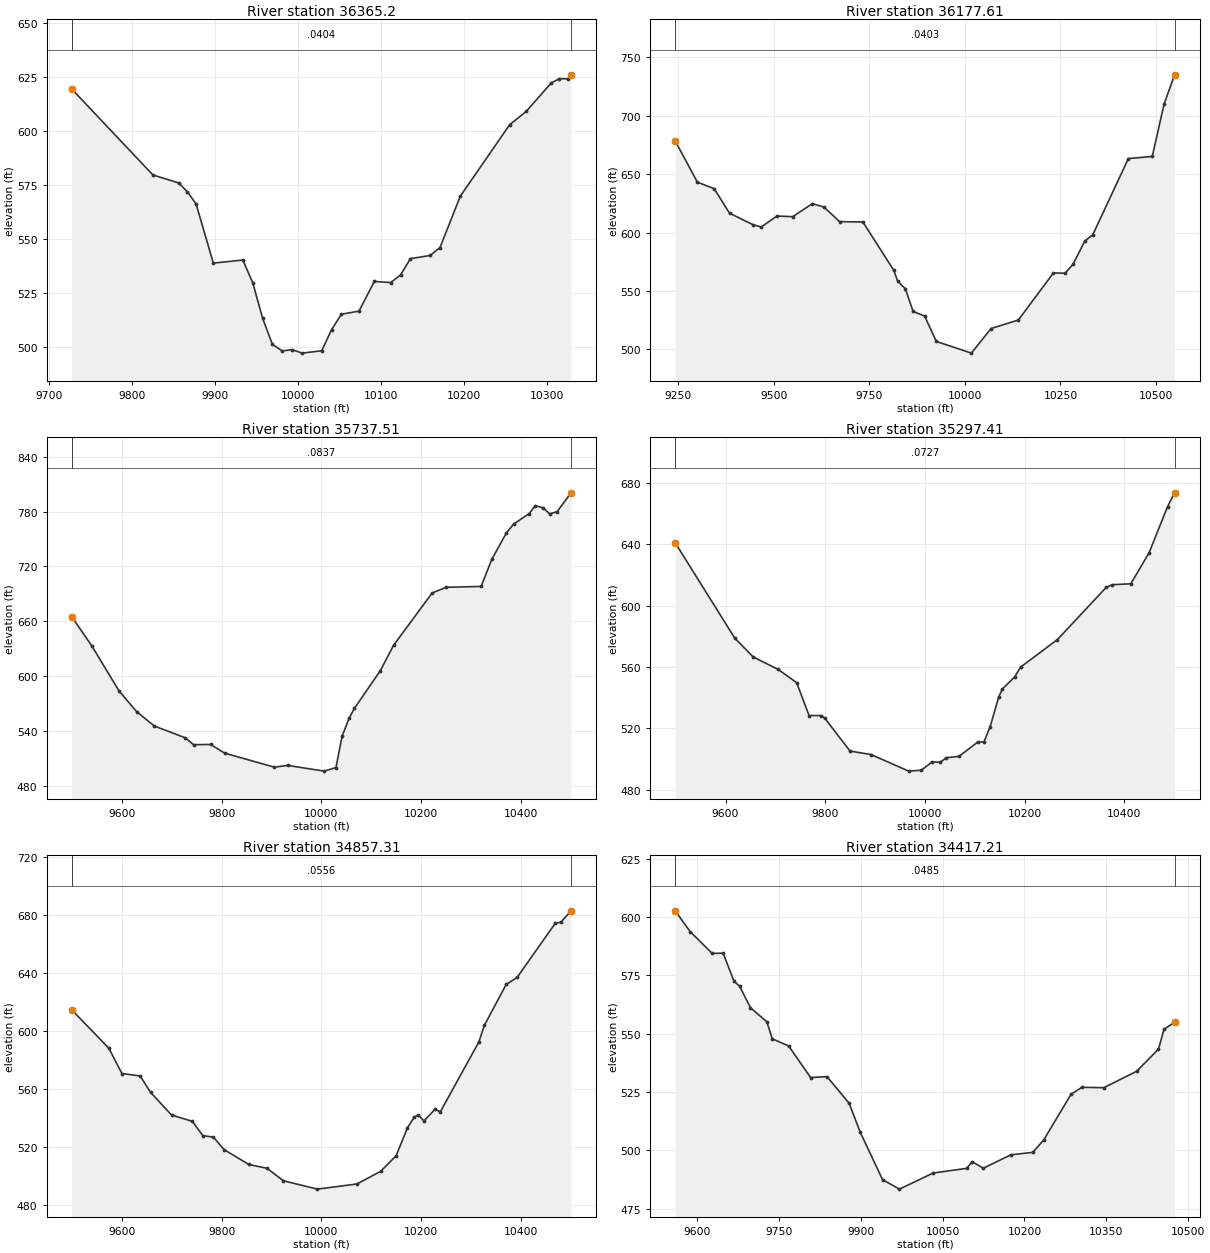
Type RM Length L Ch R = 1 , 36365.2,187.580700,187.580700,187.580700
XS GIS Cut Line= 4
583287.384837508819088.986529663583239.468170822818924.403196335
583079.051504165818674.403196335583072.801504165818541.069863006
#Sta/Elev= 30
 9726.86619.51639824.748579.73459855.994576.01259866.409571.89299876.824566.3361
9897.655538.94879933.212540.37359945.094529.90979956.975513.54629968.857501.3423
9980.739498.3504 9992.62498.9241 10004.5497.317310028.27498.409610040.15508.1781
10052.03515.3066 10073.2516.751210091.72530.472810111.44529.955510123.32533.4707
 10135.2541.017910158.96542.469610170.85546.150910195.32569.897810254.79602.9471
10274.81609.109110304.84622.253510314.85624.255510324.86624.1562 10328.8626.0222
#Mann= 3 , 0 , 0
 9726.86  0.0404       0 9726.86  0.0404       0 10328.8  0.0404       0
#XS Ineff= 2 , 0
       0                               0
Bank Sta=9726.86,10328.8
Exp/Cntr=0.3,0.1

Type RM Length L Ch R = 1 ,36177.61,440.101200,440.101200,440.101200
XS GIS Cut Line= 6
583202.201635117819580.124314915583269.924176372819364.164681044
583300.776871984819235.701638337583359.316627895818886.059914849
583422.827719274818590.208818615583502.060994094 818309.42350649
#Sta/Elev= 30
9241.339678.5155 9299.55643.14099343.418637.59379383.621616.61869446.052606.6077
9466.862604.8321 9508.01614.17489549.147613.62619600.562 624.7729631.106621.8066
9671.832609.38319732.874609.06729813.747567.66289823.856558.47489844.074551.8094
9864.292532.52259894.619528.5517 9925.04506.860610016.99496.852410068.23517.8812
10139.75525.171310231.69565.4818 10262.4565.239910283.03572.910110313.99592.8409
10334.62598.071810427.83663.317410490.47665.218310521.24709.768210548.89735.0116
#Mann= 3 , 0 , 0
9241.339  0.0403       09241.339  0.0403       010548.89  0.0403       0
#XS Ineff= 2 , 0
       0                               0
Bank Sta=9241.339,10548.89
Exp/Cntr=0.3,0.1

Type RM Length L Ch R = 1 ,35737.51,440.101200,440.101200,440.101200
XS GIS Cut Line= 6
 583445.66512859819398.422138062583530.935658023819251.361042578
583630.563591998819125.590399743583705.836746205819053.909386766
583878.624457238818924.870033665584124.174658978818673.878225766
#Sta/Elev= 30
9499.096665.31339539.468633.35129594.124 584.1149629.386561.4957 9664.87545.7625
9726.627532.95659743.777525.34619777.792525.59659805.859516.15589905.869500.7779
9932.626502.700910005.62496.470110029.39500.374110041.63534.519610056.01554.5713
10066.47565.075110118.37606.246110144.94633.8898 10222.2690.992910250.51697.2597
10320.63698.181110341.96727.746410371.09756.497910385.66 766.24110416.91777.7307
10429.35786.421210444.42784.150510458.48777.383110473.05779.903410500.97800.4325
#Mann= 3 , 0 , 0
9499.096  0.0837       09499.096  0.0837       010500.97  0.0837       0
#XS Ineff= 2 , 0
       0                               0
Bank Sta=9499.096,10500.97
Exp/Cntr=0.3,0.1

Type RM Length L Ch R = 1 ,35297.41,440.101100,440.101100,440.101100
XS GIS Cut Line= 6
583600.471881362 819685.41901499583679.862629592819623.275865404
583908.200615732 819455.17148348584001.392210641819383.401663272
584091.074591379819314.991227173584406.574027154819090.537266352
#Sta/Elev= 30
9499.011640.99769618.628578.74039655.881 566.4179705.552558.37719742.806549.7125
9767.641528.28189792.477528.25559799.329526.4703 9849.93505.10389891.957502.8233
9967.681492.02279992.922492.620210014.85498.093810030.69497.760710043.27500.7632
10068.42501.639710106.16510.993110118.61511.143210130.89520.941410148.28540.5189
10155.43545.553110179.98553.443710192.25559.907410265.88577.812610364.06611.9501
10376.33613.625510413.15614.188810449.97634.555210486.79664.419710500.99673.5318
#Mann= 3 , 0 , 0
9499.011  0.0727       09499.011  0.0727       010500.99  0.0727       0
#XS Ineff= 2 , 0
       0                               0
Bank Sta=9499.011,10500.99
Exp/Cntr=0.3,0.1

Type RM Length L Ch R = 1 ,34857.31,440.101200,440.101200,440.101200
XS GIS Cut Line= 6
583773.858251773819925.250082963584035.875935557819842.878957343
584127.778430818 819808.54365198584198.416304889819775.147677857
584394.034256944819671.255294312584693.634646571819534.166986423
#Sta/Elev= 30
9499.048614.79039573.623588.34139599.915570.87799636.518 569.2239657.483557.9144
9699.413542.30649741.343 537.9099762.308528.05479783.385527.12769804.595518.5461
9854.501508.24429890.886505.5899 9924.07497.00139991.897491.257410071.62494.8158
10119.12503.546210150.15514.313410172.57533.353210186.21540.737510194.66542.4081
10205.71538.223310227.81546.131210238.86544.580410315.99592.612210326.96603.9801
10370.84632.229210392.78 637.08210469.57 674.48510480.54675.084710500.98 682.937
#Mann= 3 , 0 , 0
9499.048  0.0556       09499.048  0.0556       010500.98  0.0556       0
#XS Ineff= 2 , 0
       0                               0
Bank Sta=9499.048,10500.98
Exp/Cntr=0.3,0.1

Type RM Length L Ch R = 1 ,34417.21,234.043500,234.043500,234.043500
XS GIS Cut Line= 6
583807.567147912820124.067422193583916.227658523820113.627032148
584041.184732686820115.532096021584424.922132625820187.545261291
584552.576417624820192.858541824584714.361223356820181.987322613
#Sta/Elev= 30
9559.966602.68249587.614593.72759627.797 584.4359647.859584.53079667.922  572.42
9677.926570.42619697.926561.14769727.927555.13979737.928547.83829767.957544.7439
9808.088531.24329838.275531.59699878.854520.14399899.178 507.7049940.057487.4455
9970.899483.404110032.62490.300710094.03492.299310104.23495.159210124.55492.3447
10175.01498.114210215.17499.150310235.21504.473410285.26524.030310305.26527.0436
10345.28526.872410405.42533.899610445.57 543.40610455.61551.885910475.04554.9085
#Mann= 3 , 0 , 0
9559.966  0.0485       09559.966  0.0485       010475.04  0.0485       0
#XS Ineff= 2 , 0
       0                               0
Bank Sta=9559.966,10475.04
Exp/Cntr=0.3,0.1

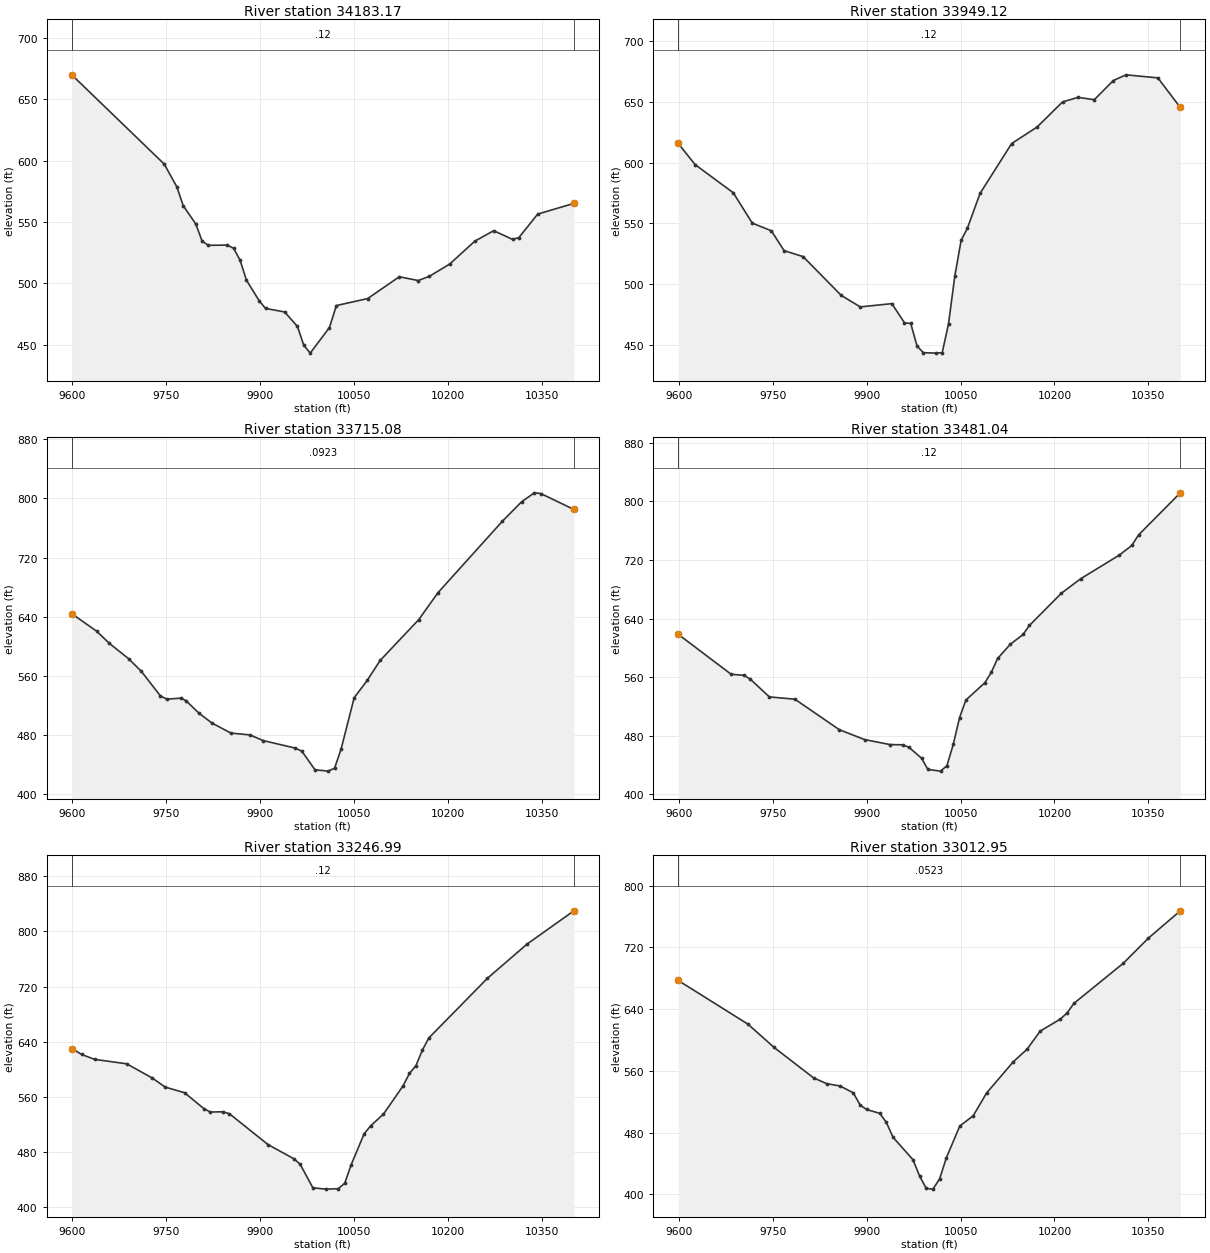
Type RM Length L Ch R = 1 ,34183.17,234.043500,234.043500,234.043500
XS GIS Cut Line= 6
583838.703794261 820441.70143581584108.927983722820404.287776306
584169.858229469820393.276305649584283.656044922820369.268208143
584338.993854218820360.227821976584632.492773995820331.927299704
#Sta/Elev= 30
9599.013669.98869746.705597.26669766.896578.66169776.991563.42949797.182548.3863
9807.277534.42149817.373531.06889847.659531.27819857.754528.5109 9867.85518.9122
9877.986502.74419898.309485.93759908.471479.67669938.991476.79829959.444464.9858
9969.671449.58899979.897443.248410010.56464.0891 10021.7482.003510071.66487.7116
10122.22 505.46810152.41502.386610170.19 505.83110202.66515.805310242.82534.4796
10272.95542.990910303.08535.916310313.12537.369410343.24556.517110400.98565.2454
#Mann= 3 , 0 , 0
9599.013    0.12       09599.013    0.12       010400.98    0.12       0
#XS Ineff= 2 , 0
       0                               0
Bank Sta=9599.013,10400.98
Exp/Cntr=0.3,0.1

Type RM Length L Ch R = 1 ,33949.12,234.043500,234.043500,234.043500
XS GIS Cut Line= 6
583878.385613033820671.562650193584158.636848115 820623.38134358
584224.650014373820614.663766602584334.443723805820603.410932313
584401.636115806820593.977948214584670.304926173820546.669475848
#Sta/Elev= 30
9599.015615.6793 9626.02598.2685  9686.9575.1535 9717.34550.1701 9747.78543.8853
9768.073527.54649798.514522.64869859.394 490.7639889.796481.3119 9940.23484.0058
9960.366468.25249970.417467.68039980.468449.13539990.518443.693110010.62443.3104
10020.68443.692710030.73467.332810040.78506.557710050.84 535.92210060.89545.9843
10081.09574.5965 10131.6615.615410172.22629.186810212.83649.797210237.62653.5461
 10263.6 651.65910294.06667.422710314.37672.090710365.14669.575710400.99645.2427
#Mann= 3 , 0 , 0
9599.015    0.12       09599.015    0.12       010400.99    0.12       0
#XS Ineff= 2 , 0
       0                               0
Bank Sta=9599.015,10400.99
Exp/Cntr=0.3,0.1

Type RM Length L Ch R = 1 ,33715.08,234.043400,234.043400,234.043400
XS GIS Cut Line= 6
 583936.11024929820925.086446141584107.376620295820890.744307948
584214.526070961820867.256463208584279.050605137820850.817142893
584429.088349134 820807.64023172584716.441459003820741.443679855
#Sta/Elev= 30
9599.011644.25319638.675620.72669659.073604.2021 9689.67 583.5739710.068566.5103
9740.665533.16519750.864528.80269773.686 530.2069781.491526.72229801.966 510.076
 9822.44496.82159853.153482.97129883.869 480.4799904.508 472.9359956.175462.6555
9966.612458.43829987.485433.423310008.38431.570210018.82435.540210029.27461.5652
10050.13530.772710070.83554.042110091.53581.068310153.23636.293210184.01672.7552
10286.63769.082710317.42795.467910337.94807.6502 10348.2806.690410400.99785.1926
#Mann= 3 , 0 , 0
9599.011  0.0923       09599.011  0.0923       010400.99  0.0923       0
#XS Ineff= 2 , 0
       0                               0
Bank Sta=9599.011,10400.99
Exp/Cntr=0.3,0.1

Type RM Length L Ch R = 1 ,33481.04,234.043500,234.043500,234.043500
XS GIS Cut Line= 6
583971.803705418821133.509560423584182.024692149 821094.69739359
584432.654792266821056.788457533584519.999517931821041.763489108
584635.937927696 821017.30615229584759.613836145820985.927691461
#Sta/Elev= 30
9599.013618.60019683.615563.94199703.953 562.6599714.122557.3035 9744.63533.0649
9785.306530.00449856.255 488.3589896.713474.84559937.171468.02249957.401467.6754
9967.515464.27849987.744449.31099997.859434.014910018.08431.745610028.19439.1803
 10038.3468.202410048.42504.909310058.53528.855510088.94552.629710099.09566.6375
10109.24585.685710129.53605.005510149.82618.371610160.01630.756710211.11674.7435
10241.77694.420410303.37726.656510323.43739.894110334.32754.315710400.98811.8069
#Mann= 3 , 0 , 0
9599.013    0.12       09599.013    0.12       010400.98    0.12       0
#XS Ineff= 2 , 0
       0                               0
Bank Sta=9599.013,10400.98
Exp/Cntr=0.3,0.1

Type RM Length L Ch R = 1 ,33246.99,234.043500,234.043500,234.043500
XS GIS Cut Line= 6
584009.621851271821387.094910632584329.282705838821312.697371341
584424.104282387821294.032077818584478.678379269821281.055342815
584640.346675216821236.702199187584786.583222562821190.493928268
#Sta/Elev= 30
9599.019630.23119614.808621.58989635.343614.52289686.679608.05969727.748587.3934
9748.282574.27939779.084 566.1399809.886543.18239820.153538.14329840.688 538.477
9850.955535.57439912.559490.90369953.468470.51419963.673462.58549984.083428.3225
10004.46426.352410024.79426.956810035.07435.057510045.35461.802310065.91506.3821
10076.19 517.93810096.89535.1247   10128575.854910138.37594.028710148.74605.3738
10159.11628.106210169.48645.670710262.98732.0795 10325.9781.370110400.97829.8507
#Mann= 3 , 0 , 0
9599.019    0.12       09599.019    0.12       010400.97    0.12       0
#XS Ineff= 2 , 0
       0                               0
Bank Sta=9599.019,10400.97
Exp/Cntr=0.3,0.1

Type RM Length L Ch R = 1 ,33012.95,247.024100,247.024100,247.024100
XS GIS Cut Line= 6
584098.551963595821643.319346732584285.285541836821585.947661343
584440.490011195821532.620131005584480.422920504821517.996155101
584671.677701427821444.650081329584852.146890582821370.387103047
#Sta/Elev= 30
9599.015676.98049710.374620.39799752.219590.19029815.209550.76159836.356543.2235
9857.504540.28519878.652531.38919889.602515.51759899.799509.81889920.947504.8083
9931.521493.00349942.095473.82089973.925444.76329984.574423.56159995.223407.5394
 10005.9406.621810016.61420.081210027.32447.241310048.74488.388310070.16501.6651
10091.58531.187710134.42571.846810155.84587.584810177.26611.423210209.43 626.967
10220.24635.028410231.06647.332810310.03699.389710350.01731.860110400.99767.2541
#Mann= 3 , 0 , 0
9599.015  0.0523       09599.015  0.0523       010400.99  0.0523       0
#XS Ineff= 2 , 0
       0                               0
Bank Sta=9599.015,10400.99
Exp/Cntr=0.3,0.1

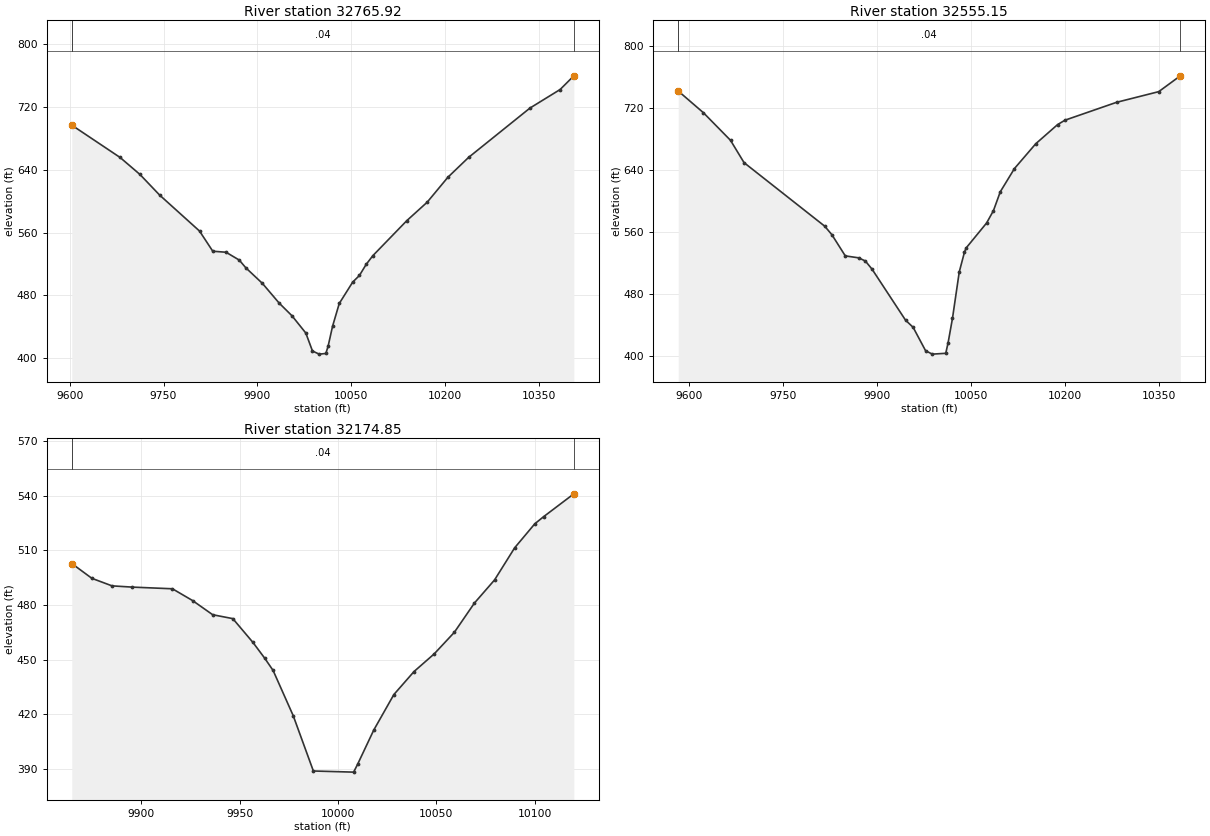
Type RM Length L Ch R = 1 ,32765.92,210.779300,210.779300,210.779300
XS GIS Cut Line= 6
  584192.1693003821880.923826124 584479.83391642 821781.27105261
584652.366451481821716.135545636584728.241817097821683.965264289
584799.495763765821650.872869671584934.278461767  821580.3377847
#Sta/Elev= 30
9603.446697.08119680.523655.93389712.272634.26539743.742607.93449807.519562.0102
9828.685536.27519849.851534.98959871.017524.9652  9881.6515.02369907.882495.3256
9934.682470.15339955.201453.9314 9977.28431.93969987.929409.00449998.579405.0221
10009.26405.828710012.89 415.066   10020440.513310030.73469.6537 10052.2496.9123
10062.94505.365610073.67519.4317 10084.4530.638710138.62575.2787 10171.2598.8337
10204.23  630.61 10237.3655.932410335.32 718.87310383.49742.534210405.43760.0017
#Mann= 3 , 0 , 0
9603.446    0.04       09603.446    0.04       010405.43    0.04       0
#XS Ineff= 2 , 0
       0                               0
Bank Sta=9603.446,10405.43
Exp/Cntr=0.3,0.1

Type RM Length L Ch R = 1 ,32555.15,380.294300,380.294300,380.294300
XS GIS Cut Line= 6
584267.827389342822093.833681464584470.033908145822010.397625427
584679.196274846821930.866255132 584747.91031433821900.600215949
584862.108230786821834.155541087584984.712862545 821744.11430937
#Sta/Elev= 30
9582.755741.83559622.968713.86519666.239678.31219687.875649.52449816.744 567.614
9828.195556.6117 9849.58529.34319870.966526.83639881.658522.72259892.351 512.203
9945.815446.50049957.957437.26039977.893407.03889988.596402.736910010.05403.7972
10013.84417.583610020.77448.741310031.61508.647610039.83533.828810042.54539.4909
10075.32571.763410086.25587.707310097.18612.001710119.77641.899710153.84673.9062
10188.63698.519610200.47704.235210282.84727.263810350.22741.0163 10384.7761.4091
#Mann= 3 , 0 , 0
9582.755    0.04       09582.755    0.04       0 10384.7    0.04       0
#XS Ineff= 2 , 0
       0                               0
Bank Sta=9582.755,10384.7
Exp/Cntr=0.3,0.1

Type RM Length L Ch R = 1 ,32174.85,108.840300,108.840300,108.840300
XS GIS Cut Line= 2
584814.236090034822354.992286161584868.264684558822105.629542276
#Sta/Elev= 26
9864.737502.78039874.961494.65129885.193490.52299895.425489.84169915.889488.9234
9926.121 482.4659936.353474.68699946.585472.54799956.817 459.4849962.794450.8166
9967.049444.11969977.281419.28149987.513388.947110007.98388.328710010.02 392.688
10018.21411.411810028.44430.911910038.67443.516410048.91453.187510059.14465.0122
10069.37 481.098 10079.6493.777510089.83511.425710100.07524.599610104.47528.4307
10119.89541.0189
#Mann= 3 , 0 , 0
9864.737    0.04       09864.737    0.04       010119.89    0.04       0
#XS Ineff= 2 , 0
       0                               0
Bank Sta=9864.737,10119.89
Exp/Cntr=0.3,0.1