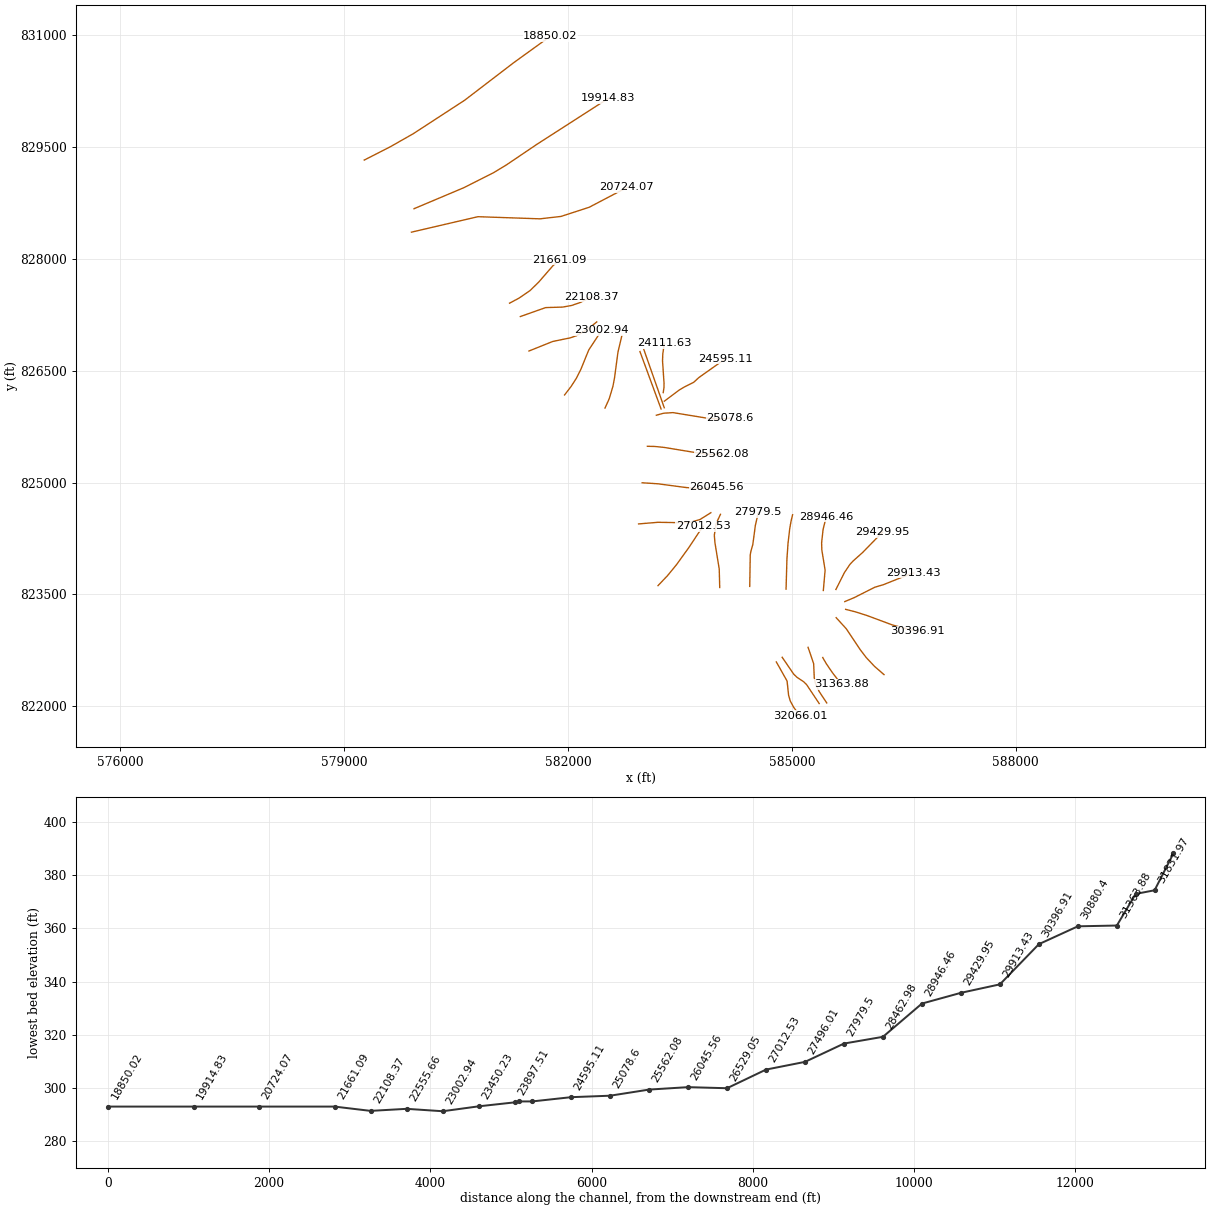
HEC-RAS study 10395_ras.prj: 10395

--- 10395_ras.g01 (geometry) --- (continued)

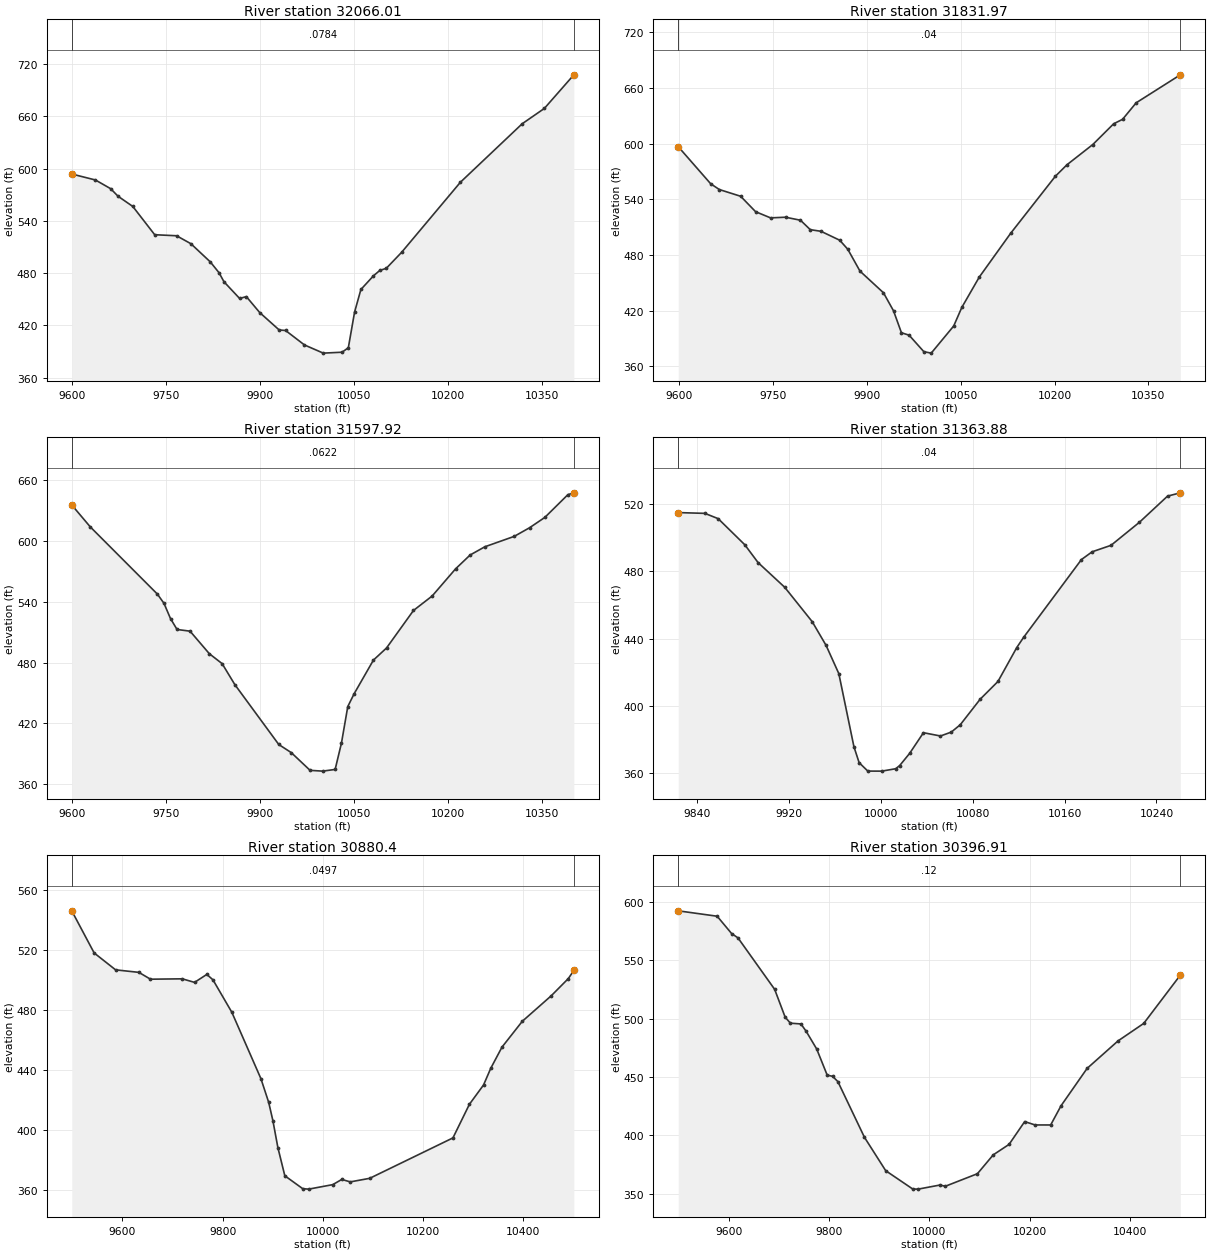
Type RM Length L Ch R = 1 ,32066.01,234.043500,234.043500,234.043500
XS GIS Cut Line= 6
584790.406580162822596.406355977584934.771772856 822340.16380431
584954.916156271822149.352503198584977.542617638822072.772940713
585024.316146868821986.259543435585106.664597801821878.318076149
#Sta/Elev= 30
9599.098593.73579636.916586.87789661.195576.8944 9673.04568.20699696.575556.5105
 9731.52524.08079766.466522.89839789.325 513.7649820.253492.95659834.285480.4608
9842.155470.10919867.112450.98059877.909453.04979899.292434.72849930.385414.7581
9940.512414.21769970.707397.600210000.74 388.22810030.75389.277410040.75394.3967
10050.75435.414610060.81461.244610080.92476.963310091.07483.150210101.34485.5208
10125.66 503.73810219.77584.333210318.45651.433510353.79668.994810400.87707.5431
#Mann= 3 , 0 , 0
9599.098  0.0784       09599.098  0.0784       010400.87  0.0784       0
#XS Ineff= 2 , 0
       0                               0
Bank Sta=9599.098,10400.87
Exp/Cntr=0.3,0.1

Type RM Length L Ch R = 1 ,31831.97,234.043500,234.043500,234.043500
XS GIS Cut Line= 6
584869.066850666822658.420135912585023.021083898822433.392247966
585067.410649206822390.393058471585157.086572012822330.735332173
585196.234070929822292.245284114585364.811313114 822038.86785371
#Sta/Elev= 30
 9599.05596.86369650.927556.84269664.717550.66179698.717543.40739722.612 526.783
9746.507520.12479770.402 520.8329794.297517.58389809.926507.41239827.055505.6562
9856.969496.0247 9869.82486.31459889.302462.75759926.798439.42559942.895419.9277
9955.521396.32199967.783393.69269991.315375.909910003.09374.357310039.01403.6078
10051.93423.606610079.82456.301510130.05503.583210201.31564.944910219.95577.3958
10261.18 599.18910294.47621.544310308.65626.305410330.45644.163810400.91674.2929
#Mann= 3 , 0 , 0
 9599.05    0.04       0 9599.05    0.04       010400.91    0.04       0
#XS Ineff= 2 , 0
       0                               0
Bank Sta=9599.05,10400.91
Exp/Cntr=0.3,0.1

Type RM Length L Ch R = 1 ,31597.92,234.043500,234.043500,234.043500
XS GIS Cut Line= 6
585216.049997481822792.194736285585290.736607912822572.802538152
585298.844632226822383.088732753585313.646691738822311.132695415
585364.671483131822200.234898274585465.716295951822047.177551843
#Sta/Elev= 30
9599.077635.29459628.545613.74799735.823547.44029746.307538.35689756.751523.3378
9767.195512.59099787.968510.91749818.776488.69459839.195478.93059859.428 458.305
9929.635399.23929949.635391.22219979.635373.76379999.638372.994410019.65374.6508
10029.73 400.58910039.84 436.61710049.95449.202610080.78482.396310101.74494.3665
10144.78531.338310174.53545.5388   10212572.342310235.24585.989110258.72594.0885
10305.67604.3516 10330.2612.870410354.57623.054910391.28645.420710400.85647.2578
#Mann= 3 , 0 , 0
9599.077  0.0622       09599.077  0.0622       010400.85  0.0622       0
#XS Ineff= 2 , 0
       0                               0
Bank Sta=9599.077,10400.85
Exp/Cntr=0.3,0.1

Type RM Length L Ch R = 1 ,31363.88,483.483400,483.483400,483.483400
XS GIS Cut Line= 6
585412.716894286822655.494413079 585421.16232907822639.188754242
585462.122244008822569.208822384585521.561347355822482.535027587
 585541.35093139822453.480402509585661.774537942822296.698887575
#Sta/Elev= 30
9823.415514.97069846.632 514.5039858.219511.34819881.393  495.83 9892.98 485.204
9916.154470.53619940.093450.07949952.219435.92839963.315419.1316 9976.47375.6418
9980.997366.13329988.595361.115710000.72361.095610012.85362.521110016.36364.4296
10024.97371.627210037.04383.960110051.87382.008510061.28384.328310069.11388.6866
10086.42403.872310101.94 414.45210118.36434.664310124.25440.672210174.68487.0141
10184.02491.640110200.44495.477110225.12509.163110249.69524.765210260.81 526.728
#Mann= 3 , 0 , 0
9823.415    0.04       09823.415    0.04       010260.81    0.04       0
#XS Ineff= 2 , 0
       0                               0
Bank Sta=9823.415,10260.81
Exp/Cntr=0.3,0.1

Type RM Length L Ch R = 1 , 30880.4,483.483400,483.483400,483.483400
XS GIS Cut Line= 6
585592.296916596823189.253244203585726.809975466823041.679543828
585915.000695195822760.133789758585996.202812896822653.733414675
586106.153405617822537.041700802586233.513994529822426.225709712
#Sta/Elev= 30
 9499.07546.35599543.735518.27199586.528507.00049632.945505.33319656.117500.7704
9719.556501.01859744.072498.64969768.589503.96729780.848 500.3269818.458478.7354
9876.548434.41869892.013 418.656 9900.38406.49679910.402388.42099924.212369.7062
 9959.96361.09159971.876360.800210019.84363.790110037.82 367.25210054.85365.6336
10093.57368.001810259.71394.955810292.55417.366910320.83430.275210335.13441.3536
10357.55455.484110398.08472.696610455.85489.7165 10489.9501.174910500.95506.6164
#Mann= 3 , 0 , 0
 9499.07  0.0497       0 9499.07  0.0497       010500.95  0.0497       0
#XS Ineff= 2 , 0
       0                               0
Bank Sta=9499.07,10500.95
Exp/Cntr=0.3,0.1

Type RM Length L Ch R = 1 ,30396.91,483.483300,483.483300,483.483300
XS GIS Cut Line= 6
585719.466258376823300.795900976 585852.27996727823266.888486726
586002.935591553823219.150909297586343.832506225823092.480406569
586505.921878712823047.606298729586676.095352577823008.001401076
#Sta/Elev= 30
 9499.04592.20639576.733 587.5849605.586572.74249618.221 569.0869691.447525.0265
9712.427501.20249722.917 496.0739743.897495.41919754.387 489.0939775.368473.9646
9796.372451.53599806.982450.65139817.592446.09929870.642398.42699913.082369.8505
9967.047354.17029977.722354.086910021.27357.588110032.08356.542610096.07367.2783
10127.67383.419610159.25392.375610190.38411.867610211.13408.997110242.26408.9856
10263.01425.453310314.89457.349910376.62480.892610427.95495.874810500.95537.1636
#Mann= 3 , 0 , 0
 9499.04    0.12       0 9499.04    0.12       010500.95    0.12       0
#XS Ineff= 2 , 0
       0                               0
Bank Sta=9499.04,10500.95
Exp/Cntr=0.3,0.1

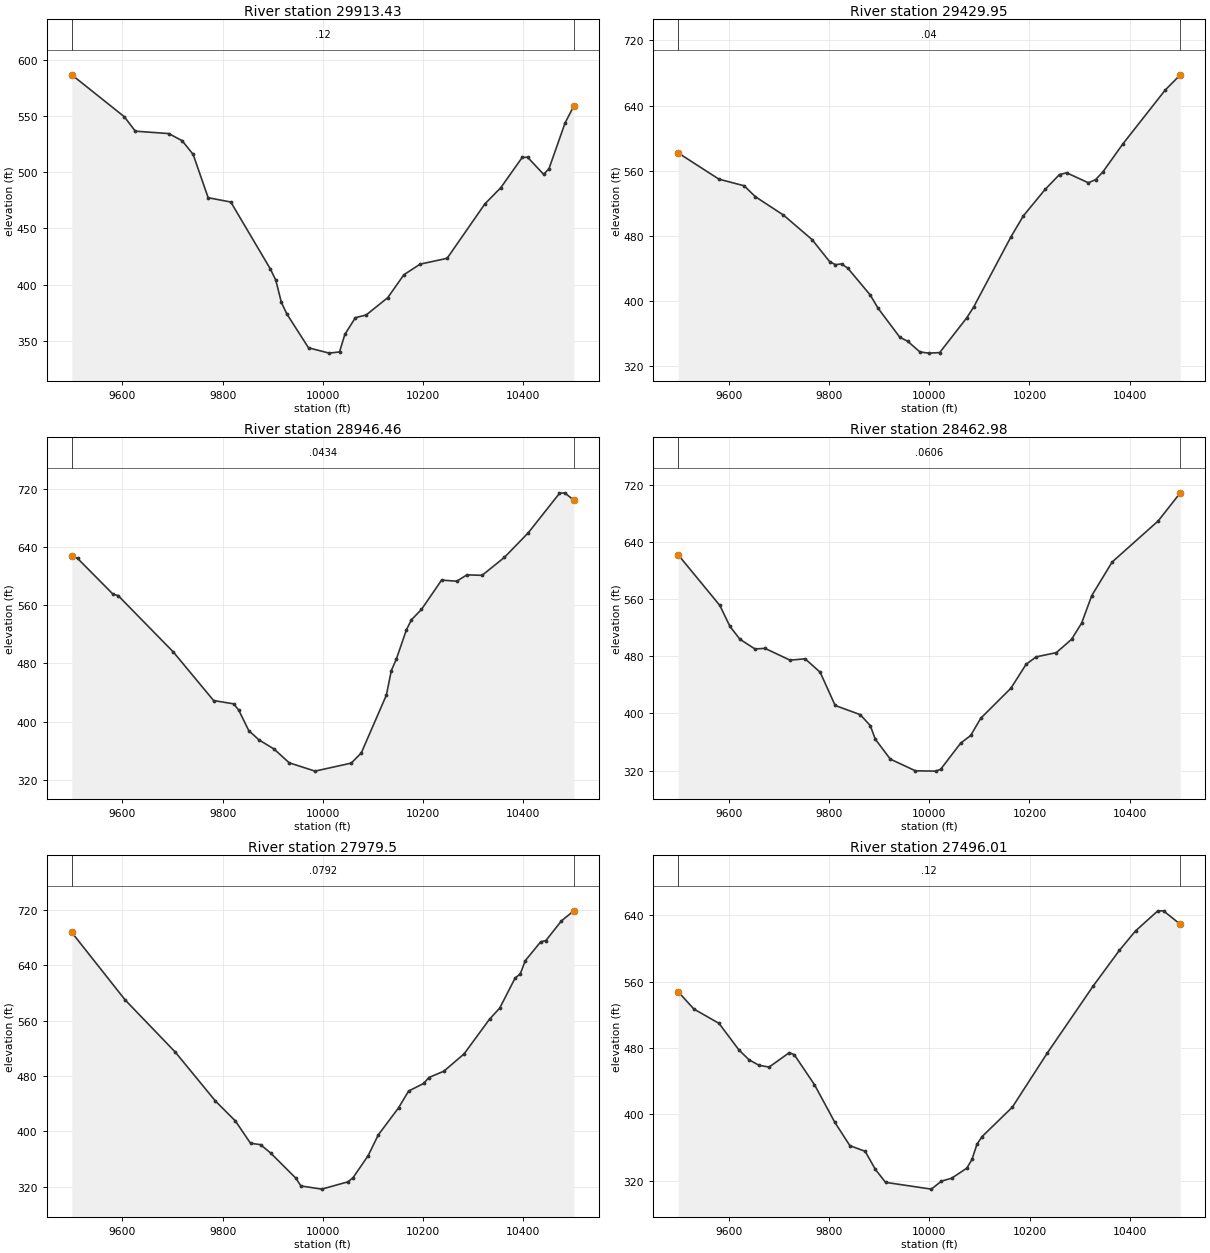
Type RM Length L Ch R = 1 ,29913.43,483.483400,483.483400,483.483400
XS GIS Cut Line= 6
585708.105237375823404.864594774585834.412285591823458.115013527
586110.235107651823597.122462236586227.210457644823632.068680582
586449.422862199823721.011358571586631.412300061823788.944872891
#Sta/Elev= 30
9499.056 586.7799603.977549.45169625.861536.60659692.596534.46829719.366528.1019
9741.204515.97259771.239477.34799816.417473.51439895.196414.02049906.225403.9059
9917.254384.25979928.283373.80449971.477343.723310012.69338.967610033.41340.0465
10043.95 355.62210065.03370.536310086.52372.917310129.61 388.37810161.92408.8225
10194.23418.193410248.09423.403410323.34471.780910355.36486.390610398.06 513.323
10408.73513.378810440.75498.140210451.43503.307410483.45543.919710500.97559.0736
#Mann= 3 , 0 , 0
9499.056    0.12       09499.056    0.12       010500.97    0.12       0
#XS Ineff= 2 , 0
       0                               0
Bank Sta=9499.056,10500.97
Exp/Cntr=0.3,0.1

Type RM Length L Ch R = 1 ,29429.95,483.483400,483.483400,483.483400
XS GIS Cut Line= 6
585589.119473739823567.013181218585702.239093308823792.322173432
 585775.62512129823902.103850538585821.150936142823950.638863327
585943.496663941824059.391114279586214.271399261824336.208709509
#Sta/Elev= 30
9499.091  581.759580.259 549.5319630.627541.39689652.924528.00239709.125505.3816
 9766.01475.36869801.017448.34189812.686444.45279825.061445.42759837.446 440.161
 9882.34407.12589897.543391.22849941.309355.21889956.667350.49829981.436337.2126
    9999335.778910020.77336.427110074.56378.9108 10088.3392.1103 10163.2478.8688
10187.91504.542110231.12536.881310259.93 555.24310274.33557.309410317.54545.0496
10331.95548.950610346.35558.341110385.97592.527510470.94659.078110500.97677.7099
#Mann= 3 , 0 , 0
9499.091    0.04       09499.091    0.04       010500.97    0.04       0
#XS Ineff= 2 , 0
       0                               0
Bank Sta=9499.091,10500.97
Exp/Cntr=0.3,0.1

Type RM Length L Ch R = 1 ,28946.46,483.483400,483.483400,483.483400
XS GIS Cut Line= 6
585420.392528664823553.741802334585444.090748049823826.710249546
585400.027564335824098.362942963585397.486913026824193.855620065
585417.320874627824372.985783595 585459.71992825824542.618698416
#Sta/Elev= 30
9499.098 627.8979510.557624.57359581.562575.14459591.628573.32649702.022495.4736
9782.035428.92669822.098424.31429832.114 415.8859852.186387.60039872.334 374.853
9902.556362.21769932.961343.19659984.477331.736810056.66342.7592 10076.7356.7137
10126.74436.206910136.74470.161210146.75 486.001 10166.8526.205110176.83540.0129
10196.89554.2911   10237594.620210267.33593.110610287.54601.866910317.87601.2049
10362.38625.918410409.84659.647910472.17713.995310482.57  714.7310500.88704.6035
#Mann= 3 , 0 , 0
9499.098  0.0434       09499.098  0.0434       010500.88  0.0434       0
#XS Ineff= 2 , 0
       0                               0
Bank Sta=9499.098,10500.88
Exp/Cntr=0.3,0.1

Type RM Length L Ch R = 1 ,28462.98,483.483400,483.483400,483.483400
XS GIS Cut Line= 6
584920.948236579823571.958960289584932.731650571 823976.19685973
584947.632345615824188.679691132584970.958263414824388.182470392
584988.122778313824482.637543231585008.105359194824567.943993569
#Sta/Elev= 30
9499.017621.61579582.142550.84589602.161521.66279622.166503.63779652.175490.0744
9672.181490.93319722.195474.38549752.203476.34419782.212457.5507 9812.22411.0332
9862.235398.2201 9882.24382.90149892.243363.97799922.277 336.0089972.358  319.68
10012.45319.231710022.48321.628310062.61358.362410082.67369.143510102.74393.1722
10163.01435.253110193.16468.558310213.26478.985610253.59484.954810283.87503.4924
10304.05526.252310324.28564.759310364.94 611.66710456.86669.133710500.97708.4037
#Mann= 3 , 0 , 0
9499.017  0.0606       09499.017  0.0606       010500.97  0.0606       0
#XS Ineff= 2 , 0
       0                               0
Bank Sta=9499.017,10500.97
Exp/Cntr=0.3,0.1

Type RM Length L Ch R = 1 , 27979.5,483.483300,483.483300,483.483300
XS GIS Cut Line= 6
584434.346725573823608.388915209584441.022126386824029.230071693
584448.708284561824074.023632891584475.747831667824170.976786168
584509.626459947824425.340913555584549.443901245824598.807367892
#Sta/Elev= 30
9499.079 687.7299605.726590.02739705.726514.65449785.726444.04999825.726415.0922
9855.742382.99629875.772380.96639895.802 368.9699946.215332.51859956.361321.2885
9997.844316.693410049.84327.1806 10060.1332.955510090.53365.199210110.76395.1621
10151.07434.102710171.22458.468410201.43469.4933 10211.5477.981310241.72487.1949
10282.07 512.29110332.72562.358210353.13578.451210383.73621.770210393.93627.6443
10404.13646.989410434.82674.175810445.18675.981810476.27704.487310500.94718.9186
#Mann= 3 , 0 , 0
9499.079  0.0792       09499.079  0.0792       010500.94  0.0792       0
#XS Ineff= 2 , 0
       0                               0
Bank Sta=9499.079,10500.94
Exp/Cntr=0.3,0.1

Type RM Length L Ch R = 1 ,27496.01,483.483400,483.483400,483.483400
XS GIS Cut Line= 6
584032.253975738823593.713299716 584025.54730948823840.767092482
583967.906407069824194.997746463583959.933575008824293.679212059
583983.164188654 824448.30034235 584042.32457827824574.243196133
#Sta/Elev= 30
9499.037547.58099530.365526.87199580.368509.64739620.379477.40029640.396465.6808
9660.413459.01389680.454456.95629720.598474.28159730.635471.80089770.913435.7104
9811.279390.57899841.553362.2135    9872355.38729892.336333.69639912.673 317.979
10004.08309.803710024.35 319.48810044.62322.931610075.02335.156910085.16345.6642
10095.29364.157510105.42373.187810165.76 408.62810235.82474.177110326.87554.4978
10379.23597.561510411.52621.028410456.08645.2652 10467.5645.192710500.91628.9988
#Mann= 3 , 0 , 0
9499.037    0.12       09499.037    0.12       010500.91    0.12       0
#XS Ineff= 2 , 0
       0                               0
Bank Sta=9499.037,10500.91
Exp/Cntr=0.3,0.1

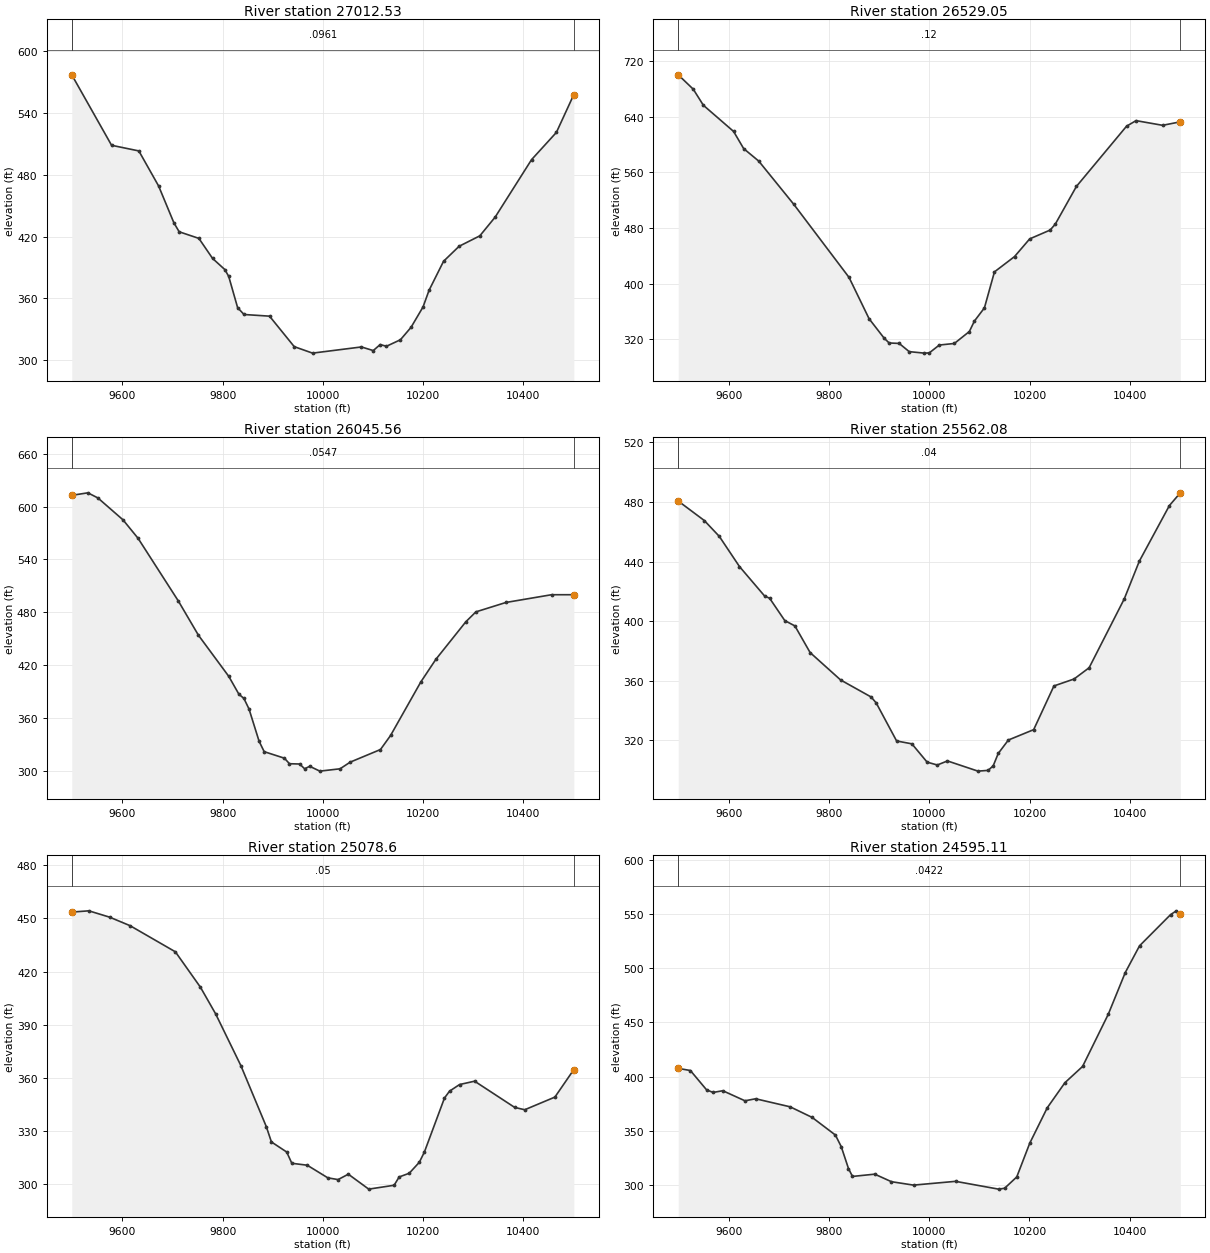
Type RM Length L Ch R = 1 ,27012.53,483.483400,483.483400,483.483400
XS GIS Cut Line= 6
583205.306994589823618.701351041583331.288566509823750.849993791
583452.679670502823898.643474798583617.434950856824127.370862108
 583752.97555845824331.776297371583812.635944311 824413.03956079
#Sta/Elev= 30
9499.031577.3055 9578.48508.83999632.884503.36199672.365469.26029702.818433.5258
9713.335424.81069752.703418.38259780.033398.9012 9804.53388.06299812.195381.4781
9830.031351.04759842.781344.43269893.673342.82269942.977313.18869979.547306.9006
10077.06312.901210100.64309.385110114.49315.220410126.97313.568510154.88319.8844
10176.03331.946210200.03351.786410212.03367.978810240.95396.144310272.02410.7323
10313.33 420.85710344.01439.119410416.55494.883210466.17521.386410500.95558.1906
#Mann= 3 , 0 , 0
9499.031  0.0961       09499.031  0.0961       010500.95  0.0961       0
#XS Ineff= 2 , 0
       0                               0
Bank Sta=9499.031,10500.95
Exp/Cntr=0.3,0.1

Type RM Length L Ch R = 1 ,26529.05,483.483400,483.483400,483.483400
XS GIS Cut Line= 6
582945.128498921824445.435352554583205.308378427824467.121651094
583541.538467845824461.536018321583650.403717795824469.720533853
583769.839354382824505.551696298583913.584414628824595.826448339
#Sta/Elev= 30
9499.043700.3717 9529.08679.64229549.192 656.5839609.525618.88959629.637594.1847
9659.708576.23399729.831513.83789839.889408.84189879.891349.36549909.906321.4259
9919.912314.50979939.926313.84649959.939302.0355 9989.96299.89119999.967   300.2
10019.98 311.52710049.99313.7786   10080331.002710090.01345.997210110.02364.9852
10130.03416.800910170.16438.854310200.36464.286310241.13 476.97810251.38485.4379
10293.53  539.7110393.66626.4544 10412.6634.455410465.53627.731410500.92632.7151
#Mann= 3 , 0 , 0
9499.043    0.12       09499.043    0.12       010500.92    0.12       0
#XS Ineff= 2 , 0
       0                               0
Bank Sta=9499.043,10500.92
Exp/Cntr=0.3,0.1

Type RM Length L Ch R = 1 ,26045.56,483.483400,483.483400,483.483400
XS GIS Cut Line= 6
582992.898382488 824996.87260712583203.636565856824983.154365582
583577.959405621824933.445902387583715.838346696824921.224515231
583853.306599067824922.850220185583988.640384732824943.952181272
#Sta/Elev= 30
9499.019612.66519531.158615.49489551.182609.6861 9601.24584.91069631.306564.0068
9711.616493.05599751.897454.11979812.319407.6362 9832.46387.4851 9842.56382.5881
9852.661370.76339872.862334.11379882.963322.34749923.366314.94419933.466308.6761
9953.668308.36069963.768302.96669973.869305.7755 9994.07300.298110034.44302.9386
10054.62310.474510115.07324.766910135.19 340.662 10195.4401.141810225.47426.8302
10285.48469.503210305.49480.671610365.56491.338610456.41500.081810500.94500.0927
#Mann= 3 , 0 , 0
9499.019  0.0547       09499.019  0.0547       010500.94  0.0547       0
#XS Ineff= 2 , 0
       0                               0
Bank Sta=9499.019,10500.94
Exp/Cntr=0.3,0.1

Type RM Length L Ch R = 1 ,25562.08,483.483300,483.483300,483.483300
XS GIS Cut Line= 6
583062.992798737825485.462934393583163.761465438825483.205113936
583289.593080239825470.169720785583804.826920666825385.447742745
583918.965822113825375.935088452584056.756239348825376.224222364
#Sta/Elev= 30
9499.021480.57069551.029467.51939581.054456.84139621.155436.6652 9671.35416.8837
9681.427415.35049711.658 400.3799731.837 396.8069762.205378.92559822.985360.5635
9883.977349.11459894.142 345.1149934.804319.6185  9965.3317.68669995.703305.4085
10015.98303.494510036.26306.218810097.12299.3811 10117.4299.881510127.54302.9272
10137.65311.260510157.85 320.24910208.35327.212810248.75 356.52910288.89361.1849
10318.99368.738110389.15414.974210419.16440.243310479.18477.552510500.95486.0944
#Mann= 3 , 0 , 0
9499.021    0.04       09499.021    0.04       010500.95    0.04       0
#XS Ineff= 2 , 0
       0                               0
Bank Sta=9499.021,10500.95
Exp/Cntr=0.3,0.1

Type RM Length L Ch R = 1 , 25078.6,483.483400,483.483400,483.483400
XS GIS Cut Line= 6
583182.511060872825901.590051468583279.543415135825928.501163119
583405.559305988825936.942716569 583883.66887104825858.743137425
584030.423426302825852.644705989584172.679423151825861.613477779
#Sta/Elev= 30
9499.073453.60029533.152454.30889574.744450.71679615.492445.90689705.827431.1516
9755.896411.11759786.045396.15739836.482366.8648 9887.28332.38329897.454323.7437
9927.978318.04129938.191311.6806 9968.98 310.58510010.01303.456410030.48302.4666
10050.94305.517810091.66297.079110142.29299.262210152.39303.955210172.51306.0569
10192.64312.2601 10202.7318.023210242.84348.578110252.86 352.41510272.91356.1656
10302.92358.061610382.95 343.23610402.96341.928310463.12349.071710500.95364.6447
#Mann= 3 , 0 , 0
9499.073    0.05       09499.073    0.05       010500.95    0.05       0
#XS Ineff= 2 , 0
       0                               0
Bank Sta=9499.073,10500.95
Exp/Cntr=0.3,0.1

Type RM Length L Ch R = 1 ,24595.11,483.483400,483.483400,483.483400
XS GIS Cut Line= 6
583290.356037725826089.989076397583492.023174702826241.149492094
583559.668512172826281.063208898583683.735072554826343.182018968
583752.743138006826406.561282168 584110.73236805826659.691226243
#Sta/Elev= 30
9499.097 407.7139523.365405.7529  9555.7 387.9429568.641385.57219588.034387.1376
9632.274377.86499653.503379.73459722.447  372.329766.296362.5653 9812.74346.3264
9824.351335.64779838.835315.45499846.793308.21199891.202310.31029924.508303.3685
9968.579300.214910052.49303.695110138.16296.522710150.32297.307410174.63307.7614
10200.42338.706810235.41371.414210270.77394.573610305.95409.507610357.18457.5401
10391.13495.995510419.61 520.60310481.48549.295210492.99552.822210500.95549.7692
#Mann= 3 , 0 , 0
9499.097  0.0422       09499.097  0.0422       010500.95  0.0422       0
#XS Ineff= 2 , 0
       0                               0
Bank Sta=9499.097,10500.95
Exp/Cntr=0.3,0.1

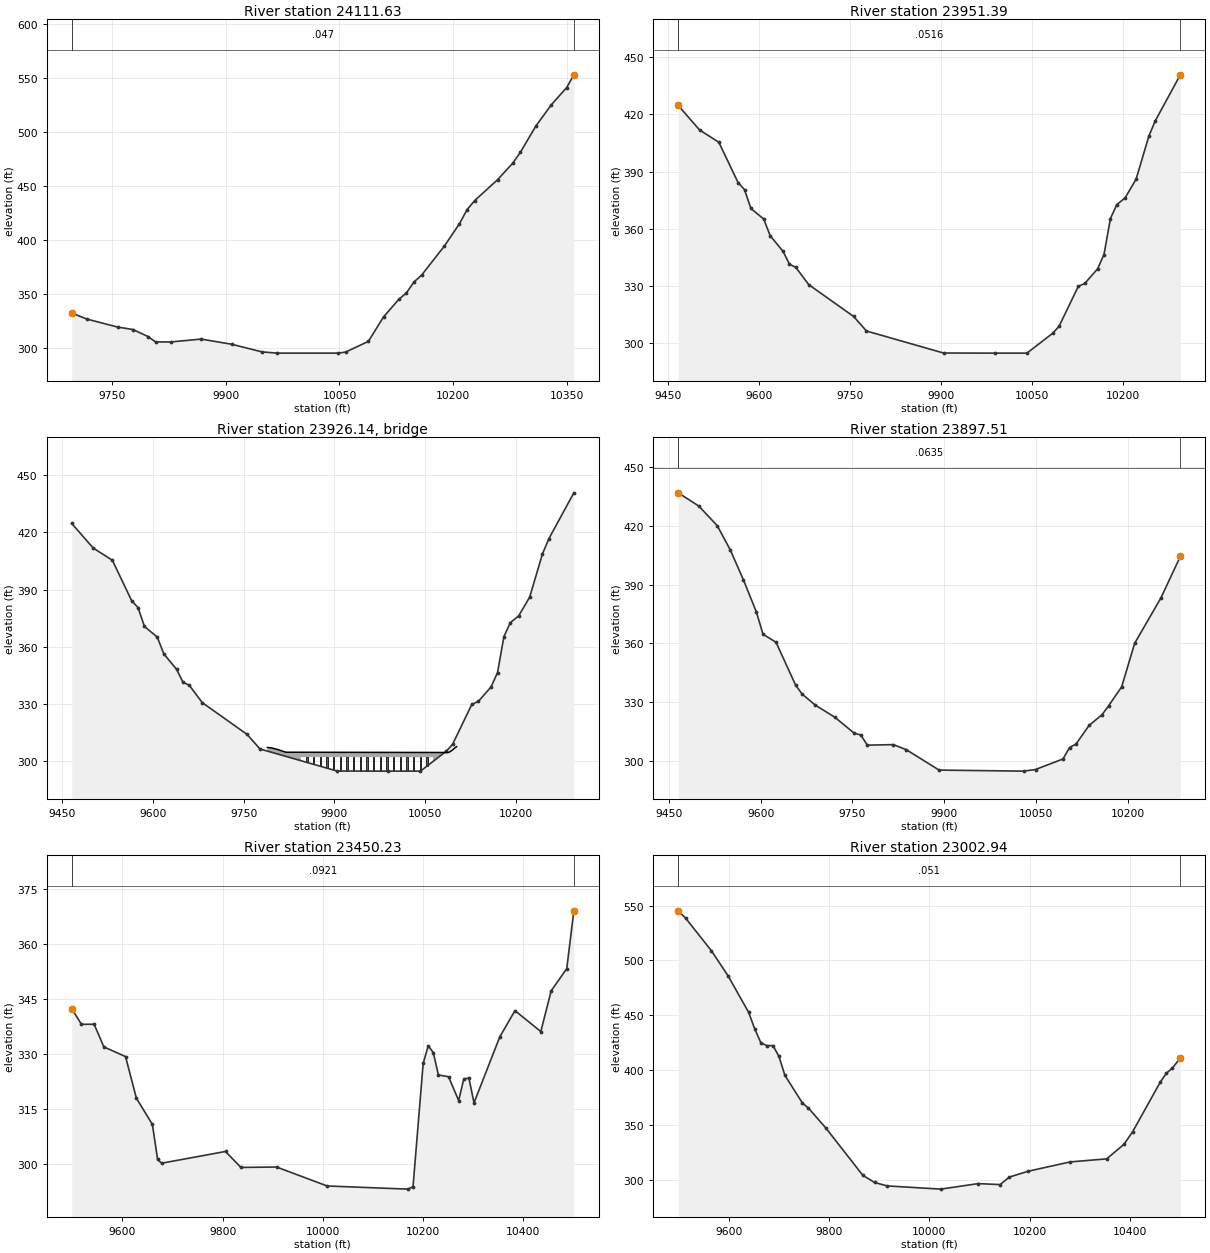
Type RM Length L Ch R = 1 ,24111.63,160.239100,160.239100,160.239100
XS GIS Cut Line= 6
583275.150880952 826205.37762769583285.218112009826272.037248359
583286.061814501826331.037966778583265.802376869826632.978355683
583269.698607484826726.221721172583290.084918944826864.286001181
#Sta/Elev= 30
 9696.93332.1007 9717.03326.50029757.363319.12859777.407316.85349797.409310.3562
 9807.41305.34849827.419305.29519867.489307.96099907.637303.19689947.814296.0704
9967.893294.923310048.14294.923310058.14295.898210088.16305.834510108.17328.5858
10128.19344.771210138.19350.7361 10148.2360.908910158.21367.233410188.24394.1752
10208.25415.012210218.26428.047510228.32436.535210258.52455.883510278.65471.3475
10288.72481.454310308.98505.640310329.33525.350510349.69541.458310359.14553.2533
#Mann= 3 , 0 , 0
 9696.93   0.047       0 9696.93   0.047       010359.14   0.047       0
#XS Ineff= 2 , 0
       0                               0
Bank Sta=9696.93,10359.14
Exp/Cntr=0.3,0.1

Type RM Length L Ch R = 1 ,23951.39,53.877500,53.877500,53.877500
XS GIS Cut Line= 2
583289.249051721826001.767403909583014.815772036826783.886379523
#Sta/Elev= 30
9466.374424.66159501.593411.83899533.386405.39899565.179384.25859575.777380.5829
9586.375   370.7 9607.57365.12829618.168356.42219639.363348.26299649.961 341.529
9660.559339.83549681.754330.82049755.938314.12439777.134306.51499904.307294.9821
9989.088294.923310042.08294.923310084.47305.313110095.07308.979110126.86329.9132
10137.46331.402110158.65339.062110169.25346.579710179.85365.436410190.45372.7493
10204.08376.231410222.24386.036410243.43408.710210254.03416.703810295.24440.7239
#Mann= 3 , 0 , 0
9466.374  0.0516       09466.374  0.0516       010295.24  0.0516       0
#XS Ineff= 2 , 0
       0                               0
Bank Sta=9466.374,10295.24
Exp/Cntr=0.3,0.1

Type RM Length L Ch R = 3 ,23926.14,,,
BEGIN DESCRIPTION:
END DESCRIPTION:
Bridge Culvert--1,0,-1,-1, 0
Deck Dist Width WeirC Skew NumUp NumDn MinLoCord MaxHiCord MaxSubmerge Is_Ogee
16.938750,20.000000,2.6,0, 14, 14, , , 0.95, 0, 0,0,,
 9789.38 9796.12 9806.51 9806.76 9817.40 9820.56 9844.67 9844.6710062.6710062.67
10088.5410094.0610099.0710101.55
  307.34  307.08  306.25  306.23  305.05  304.83  304.81  304.81  304.70  304.70
  304.68  305.80  307.14  307.73
 -692.66 -692.92 -693.75 -693.77 -694.95 -695.17 -695.19  302.31  302.20 -695.30
 -695.32 -694.20 -692.86 -692.27
 9789.38 9796.12 9806.51 9806.76 9817.40 9820.56 9846.56 9846.5610064.5610064.56
10088.5410094.0610099.0710101.55
  307.34  307.08  306.25  306.23  305.05  304.83  304.81  304.81  304.70  304.70
  304.68  305.80  307.14  307.73
 -692.66 -692.92 -693.75 -693.77 -694.95 -695.17 -695.19  302.31  302.20 -695.30
 -695.32 -694.20 -692.86 -692.27
Pier Skew, UpSta & Num, DnSta & Num=  ,9854.67, 2 ,9856.56, 2 , 0 , 0 , 0 ,,
    2.00    2.00
 -695.19  304.81
    2.00    2.00
 -695.19  304.81
Pier Skew, UpSta & Num, DnSta & Num=  ,9865.67, 2 ,9867.56, 2 , 0 , 0 , 0 ,,
    2.00    2.00
 -695.20  304.80
    2.00    2.00
 -695.20  304.80
Pier Skew, UpSta & Num, DnSta & Num=  ,9876.67, 2 ,9878.56, 2 , 0 , 0 , 0 ,,
    2.00    2.00
 -695.20  304.80
    2.00    2.00
 -695.20  304.80
Pier Skew, UpSta & Num, DnSta & Num=  ,9887.67, 2 ,9889.56, 2 , 0 , 0 , 0 ,,
    2.00    2.00
 -695.21  304.79
    2.00    2.00
 -695.21  304.79
Pier Skew, UpSta & Num, DnSta & Num=  ,9898.67, 2 ,9900.56, 2 , 0 , 0 , 0 ,,
    2.00    2.00
 -695.21  304.79
    2.00    2.00
 -695.22  304.78
Pier Skew, UpSta & Num, DnSta & Num=  ,9909.67, 2 ,9911.56, 2 , 0 , 0 , 0 ,,
    2.00    2.00
 -695.22  304.78
    2.00    2.00
 -695.22  304.78
Pier Skew, UpSta & Num, DnSta & Num=  ,9920.67, 2 ,9922.56, 2 , 0 , 0 , 0 ,,
    2.00    2.00
 -695.23  304.77
    2.00    2.00
 -695.23  304.77
Pier Skew, UpSta & Num, DnSta & Num=  ,9931.67, 2 ,9933.56, 2 , 0 , 0 , 0 ,,
    2.00    2.00
 -695.23  304.77
    2.00    2.00
 -695.23  304.77
Pier Skew, UpSta & Num, DnSta & Num=  ,9942.67, 2 ,9944.56, 2 , 0 , 0 , 0 ,,
    2.00    2.00
 -695.24  304.76
    2.00    2.00
 -695.24  304.76
Pier Skew, UpSta & Num, DnSta & Num=  ,9953.67, 2 ,9955.56, 2 , 0 , 0 , 0 ,,
    2.00    2.00
 -695.24  304.76
    2.00    2.00
 -695.25  304.75
Pier Skew, UpSta & Num, DnSta & Num=  ,9964.67, 2 ,9966.56, 2 , 0 , 0 , 0 ,,
    2.00    2.00
 -695.25  304.75
    2.00    2.00
 -695.25  304.75
Pier Skew, UpSta & Num, DnSta & Num=  ,9975.67, 2 ,9977.56, 2 , 0 , 0 , 0 ,,
    2.00    2.00
 -695.26  304.74
    2.00    2.00
 -695.26  304.74
Pier Skew, UpSta & Num, DnSta & Num=  ,9986.67, 2 ,9988.56, 2 , 0 , 0 , 0 ,,
    2.00    2.00
 -695.26  304.74
    2.00    2.00
 -695.26  304.74
Pier Skew, UpSta & Num, DnSta & Num=  ,9997.67, 2 ,9999.56, 2 , 0 , 0 , 0 ,,
    2.00    2.00
 -695.27  304.73
    2.00    2.00
 -695.27  304.73
Pier Skew, UpSta & Num, DnSta & Num=  ,10008.67, 2 ,10010.56, 2 , 0 , 0 , 0 ,,
    2.00    2.00
 -695.27  304.73
    2.00    2.00
 -695.27  304.73
Pier Skew, UpSta & Num, DnSta & Num=  ,10019.67, 2 ,10021.56, 2 , 0 , 0 , 0 ,,
    2.00    2.00
 -695.28  304.72
    2.00    2.00
 -695.28  304.72
Pier Skew, UpSta & Num, DnSta & Num=  ,10030.67, 2 ,10032.56, 2 , 0 , 0 , 0 ,,
    2.00    2.00
 -695.29  304.71
    2.00    2.00
 -695.29  304.71
Pier Skew, UpSta & Num, DnSta & Num=  ,10041.67, 2 ,10043.56, 2 , 0 , 0 , 0 ,,
    2.00    2.00
 -695.29  304.71
    2.00    2.00
 -695.29  304.71
Pier Skew, UpSta & Num, DnSta & Num=  ,10052.67, 2 ,10054.56, 2 , 0 , 0 , 0 ,,
    2.00    2.00
 -695.30  304.70
    2.00    2.00
 -695.30  304.70
BR Coef=-1 , 0 , 0 ,, 0 ,,,0.8,0,1,0,
WSPro=,,,, 1 ,,,, 0 ,,,, 0 ,,,,-1 ,-1 ,-1 , 0 , 0 , 0 , 0 , 0
BC Design=,, 0 ,, 0 ,,,,,,

Type RM Length L Ch R = 1 ,23897.51,447.284600,447.284600,447.284600
XS GIS Cut Line= 2
583246.642222387825985.053499248582963.281680244826754.913257894
#Sta/Elev= 30
9465.401436.88969499.106430.10599529.279420.03269550.591407.59349571.902392.3791
9593.214375.8612 9603.87364.58679625.182360.47699657.149338.57399667.805334.0168
9689.117328.38229721.084322.17519753.052313.95819763.708313.06729774.364 307.863
9816.987308.13199838.299305.50179891.578295.1058 10030.1  294.5810049.17295.4083
10094.04300.7977 10104.7306.612810115.35308.459610136.66317.927810157.97323.4712
10168.63328.015410189.94337.702910211.25360.005510253.88383.043110285.75404.3484
#Mann= 3 , 0 , 0
9465.401  0.0635       09465.401  0.0635       010285.75  0.0635       0
#XS Ineff= 2 , 0
       0                               0
Bank Sta=9465.401,10285.75
Exp/Cntr=0.3,0.1

Type RM Length L Ch R = 1 ,23450.23,447.284600,447.284600,447.284600
XS GIS Cut Line= 6
582495.088970129825997.715864258582552.348785565826124.443296161
582602.171343672826292.760485829582623.032625739826404.184274826
582668.838005163826747.486188348582721.082484448826968.612592131
#Sta/Elev= 30
9499.067342.39179518.379338.12059543.702338.13379563.052331.94689606.346329.2984
9627.993317.93619659.875310.78629670.412301.18319678.344300.16849805.833303.3729
9836.558299.0121 9907.78299.124710008.67293.947410169.94293.085610180.05293.7671
10200.29327.450110210.41332.239210220.52 330.38510230.64324.286210250.88323.7943
10271.11317.2886 10281.3323.162810291.51323.454310301.72316.665210353.25334.7045
10383.43  341.8510435.01336.141810455.74347.267610486.84353.339610500.95369.1229
#Mann= 3 , 0 , 0
9499.067  0.0921       09499.067  0.0921       010500.95  0.0921       0
#XS Ineff= 2 , 0
       0                               0
Bank Sta=9499.067,10500.95
Exp/Cntr=0.3,0.1

Type RM Length L Ch R = 1 ,23002.94,447.284600,447.284600,447.284600
XS GIS Cut Line= 6
581953.609892052826173.604454222582042.231915776826288.921172133
582111.387200572826397.184466781582171.621690888826516.125871007
582277.252696314826776.051346081582449.624654383827037.944567714
#Sta/Elev= 30
9499.042545.33729513.665538.71599564.993509.02819598.453 486.0149639.653452.5467
 9651.84437.28159663.889424.95429675.939422.20339687.988422.32789700.038412.4216
9711.849395.1632 9747.01369.7267 9758.73365.3181 9793.28347.21279867.322303.8901
9890.826297.30559915.961294.169510022.96 291.236 10097.6296.2784 10141.3 295.386
10159.79302.246910197.48  307.5910281.15316.086710353.95318.8459 10388.7332.2096
10406.07343.835110460.66388.688210472.89 396.91810485.12401.801510500.95410.9572
#Mann= 3 , 0 , 0
9499.042   0.051       09499.042   0.051       010500.95   0.051       0
#XS Ineff= 2 , 0
       0                               0
Bank Sta=9499.042,10500.95
Exp/Cntr=0.3,0.1

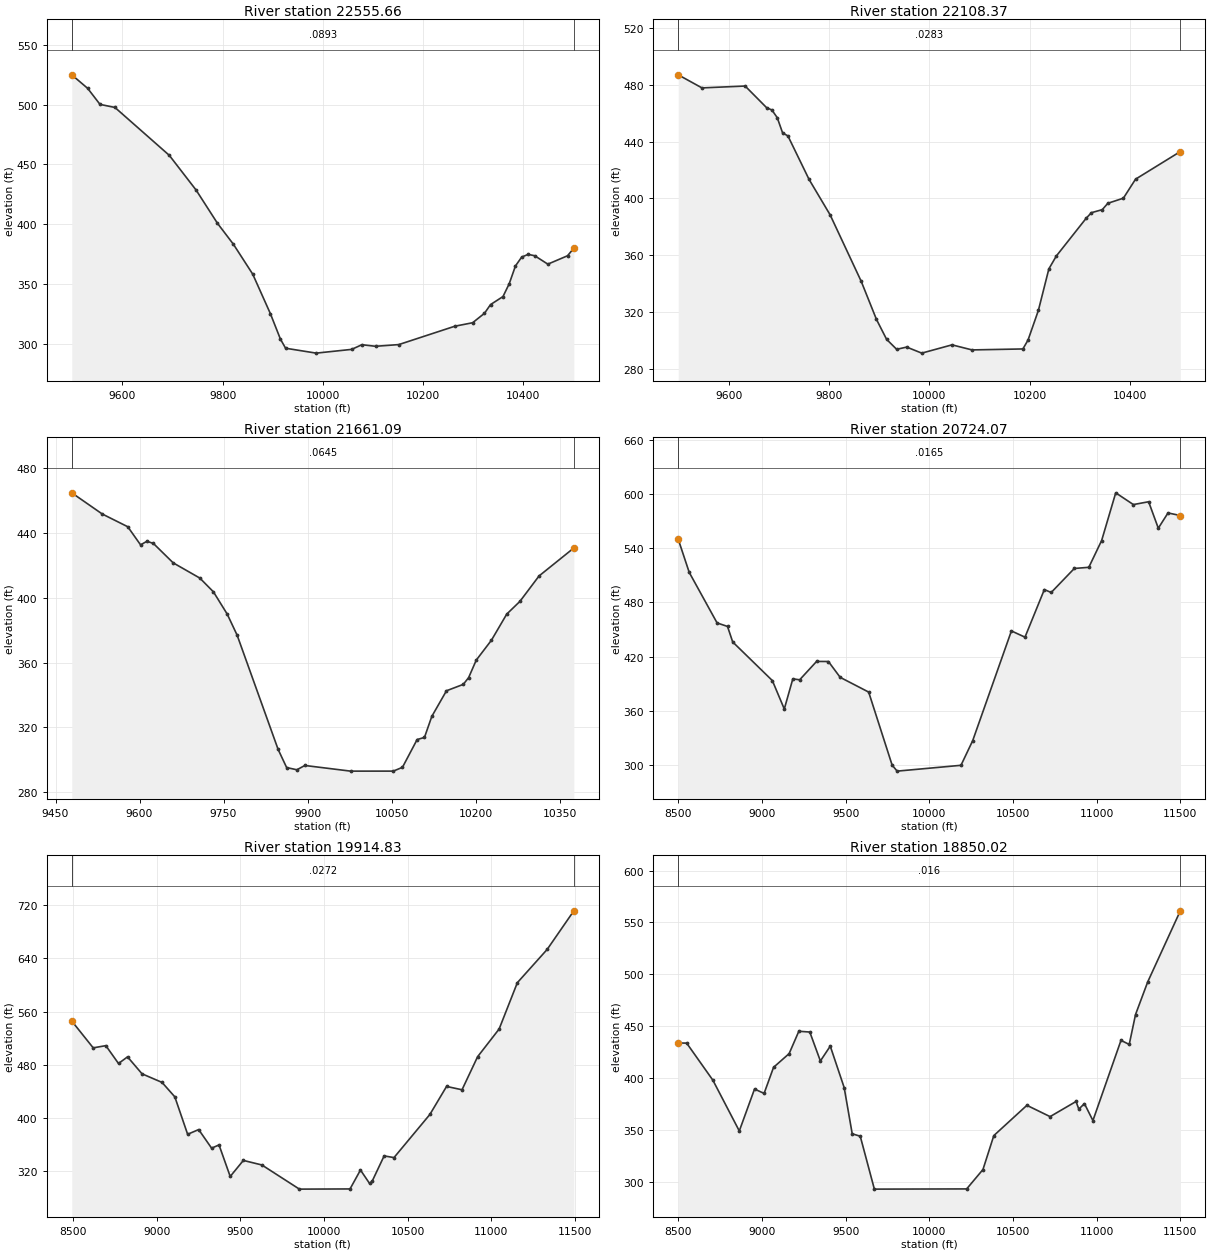
Type RM Length L Ch R = 1 ,22555.66,447.284600,447.284600,447.284600
XS GIS Cut Line= 6
581476.267142855826762.094708957581794.057942348826889.744794714
582026.975997944826937.773230694582112.420032211826966.731661703
582251.957832194827045.713334607582384.618866573827152.007369066
#Sta/Elev= 30
9499.031524.89099530.767 513.5789555.358 500.1769585.211497.59199693.628457.5573
9747.159428.50459789.826400.68439821.533383.21839860.127358.18859895.238325.2795
9915.427303.83489925.714296.23279986.739292.141210057.53295.272510077.94299.1786
 10105.3297.859710151.56299.2838 10263.4314.641310298.91317.556310322.58325.4534
10334.61332.7232 10359.5 339.45110371.94350.166410384.39365.055310396.83372.4673
10409.75374.730110422.85373.577110449.03366.5544 10488.3373.5632 10500.9  379.93
#Mann= 3 , 0 , 0
9499.031  0.0893       09499.031  0.0893       0 10500.9  0.0893       0
#XS Ineff= 2 , 0
       0                               0
Bank Sta=9499.031,10500.9
Exp/Cntr=0.3,0.1

Type RM Length L Ch R = 1 ,22108.37,447.284600,447.284600,447.284600
XS GIS Cut Line= 6
  581361.0268086 827223.90549306581700.131338525827343.921997082
581925.754144955 827350.60268878582049.341460972827372.482012016
582169.082944852827414.359125755582312.918956365827489.115667243
#Sta/Elev= 30
9499.085486.87179546.435 477.692 9632.58478.99449675.319463.82549685.976462.1636
9696.633456.77039707.289446.09949717.946443.94129760.156413.37559802.111388.5198
9864.102341.85869894.601315.04459914.791301.07579934.869294.05159954.911295.6092
9984.964291.369910045.29  297.18 10085.3293.624910186.76294.304710197.01300.5467
10217.63 321.35210238.59350.561710253.52359.622710313.03386.1224 10323.5390.0297
10345.17392.170710356.22396.631310387.24400.211410411.51413.562210500.84432.9556
#Mann= 3 , 0 , 0
9499.085  0.0283       09499.085  0.0283       010500.84  0.0283       0
#XS Ineff= 2 , 0
       0                               0
Bank Sta=9499.085,10500.84
Exp/Cntr=0.3,0.1

Type RM Length L Ch R = 1 ,21661.09,937.021800,937.021800,937.021800
XS GIS Cut Line= 6
 581216.32057364 827403.19748861581340.836540708 827469.14521301
 581490.14695866827571.421110262581605.299848826827683.620688444
581797.979600805827905.236617725581886.123694257827986.310895367
#Sta/Elev= 30
9479.024464.78179533.441451.71099579.019443.84239601.865432.66699613.287434.8723
9624.846433.51179660.093421.5576 9707.69412.1562 9732.02403.64029756.607389.9117
9774.334 376.8829847.537306.36119862.697295.19729881.019293.81739895.236296.4758
9976.843 292.98510053.22292.992710069.53295.344310095.73 312.48810108.82313.7814
10121.92326.766910148.11342.588810178.09346.531210187.72 350.73310201.26361.4906
10228.34373.760110255.74389.915510279.22397.751410313.45 413.47110375.56430.7324
#Mann= 3 , 0 , 0
9479.024  0.0645       09479.024  0.0645       010375.56  0.0645       0
#XS Ineff= 2 , 0
       0                               0
Bank Sta=9479.024,10375.56
Exp/Cntr=0.3,0.1

Type RM Length L Ch R = 1 ,20724.07,809.234600,809.234600,809.234600
XS GIS Cut Line= 6
579901.952164907828354.492172256580792.511742116828561.760641199
581624.244652647828533.169153741581905.366214916828565.339236825
582283.893220636828688.247193702582788.288616008828952.911091708
#Sta/Elev= 30
8499.065550.0555 8564.72 513.3268731.337457.27928793.653453.3917 8824.72436.1807
9061.742393.36989133.183361.8436 9184.21  395.289225.014394.2228 9326.28414.5996
 9396.93414.51479467.366396.94929637.637380.62129777.742299.76049807.801 292.985
10189.59299.443210259.61326.7714 10491.1448.405110572.24441.492410688.04494.2774
   10729491.027110867.26517.670510953.85518.9337 11030.5548.6048 11114.8601.5112
11220.34 588.48611311.49591.628511369.33 562.30511427.41 579.21111500.93576.3486
#Mann= 3 , 0 , 0
8499.065  0.0165       08499.065  0.0165       011500.93  0.0165       0
#XS Ineff= 2 , 0
       0                               0
Bank Sta=8499.065,11500.93
Exp/Cntr=0.3,0.1

Type RM Length L Ch R = 1 ,19914.83,1064.808900,1064.808900,1064.808900
XS GIS Cut Line= 6
579936.483433667828668.764894584580603.126509463 828949.95242128
581001.622259182829151.084739614581174.984252246 829256.08695628
581586.364883347829533.942108785582539.058293334830146.652075139
#Sta/Elev= 30
8491.406545.70718619.497505.40758695.152508.73198770.807481.89488824.846491.8756
8911.517466.37029031.129 453.4479107.569431.7481 9184.19375.43619250.163382.5402
 9327.44  354.58 9371.83359.45049438.732312.00349517.394336.14929628.153329.3049
9852.421 292.98510155.18293.270210217.59321.725510271.96301.506210287.08304.6535
10359.02 342.93610418.07340.4096 10632.5405.236910732.35447.399210824.79442.3774
10917.85492.040111046.63533.740611155.64603.419311333.98653.469611493.37711.4523
#Mann= 3 , 0 , 0
8491.406  0.0272       08491.406  0.0272       011493.37  0.0272       0
#XS Ineff= 2 , 0
       0                               0
Bank Sta=8491.406,11493.37
Exp/Cntr=0.3,0.1

Type RM Length L Ch R = 1 ,18850.02,1324.669900,1324.669900,1324.669900
XS GIS Cut Line= 6
579269.823285752829320.278439698579622.654972804829500.751473472
579926.676203447829673.788685128580614.571545801830121.849792091
581271.223258127830624.595730384581763.854350508830980.239782553
#Sta/Elev= 30
8499.026433.89888549.461433.71368706.203397.96478864.155349.05888955.219389.4584
  9012.4385.2405    9069410.38639162.094423.60269220.065445.15289285.644444.4067
9348.928416.51139408.008430.81699491.221390.85129539.234346.31729587.247343.9859
9671.733 292.98510223.67293.187510321.05311.897610385.97344.594210583.73373.7696
10722.34362.8698 10877.5377.462910894.05370.136210927.81375.373410978.45359.0729
11146.31436.367211195.55432.447411233.23461.273811306.01492.697711500.98561.2369
#Mann= 3 , 0 , 0
8499.026   0.016       08499.026   0.016       011500.98   0.016       0
#XS Ineff= 2 , 0
       0                               0
Bank Sta=8499.026,11500.98
Exp/Cntr=0.3,0.1