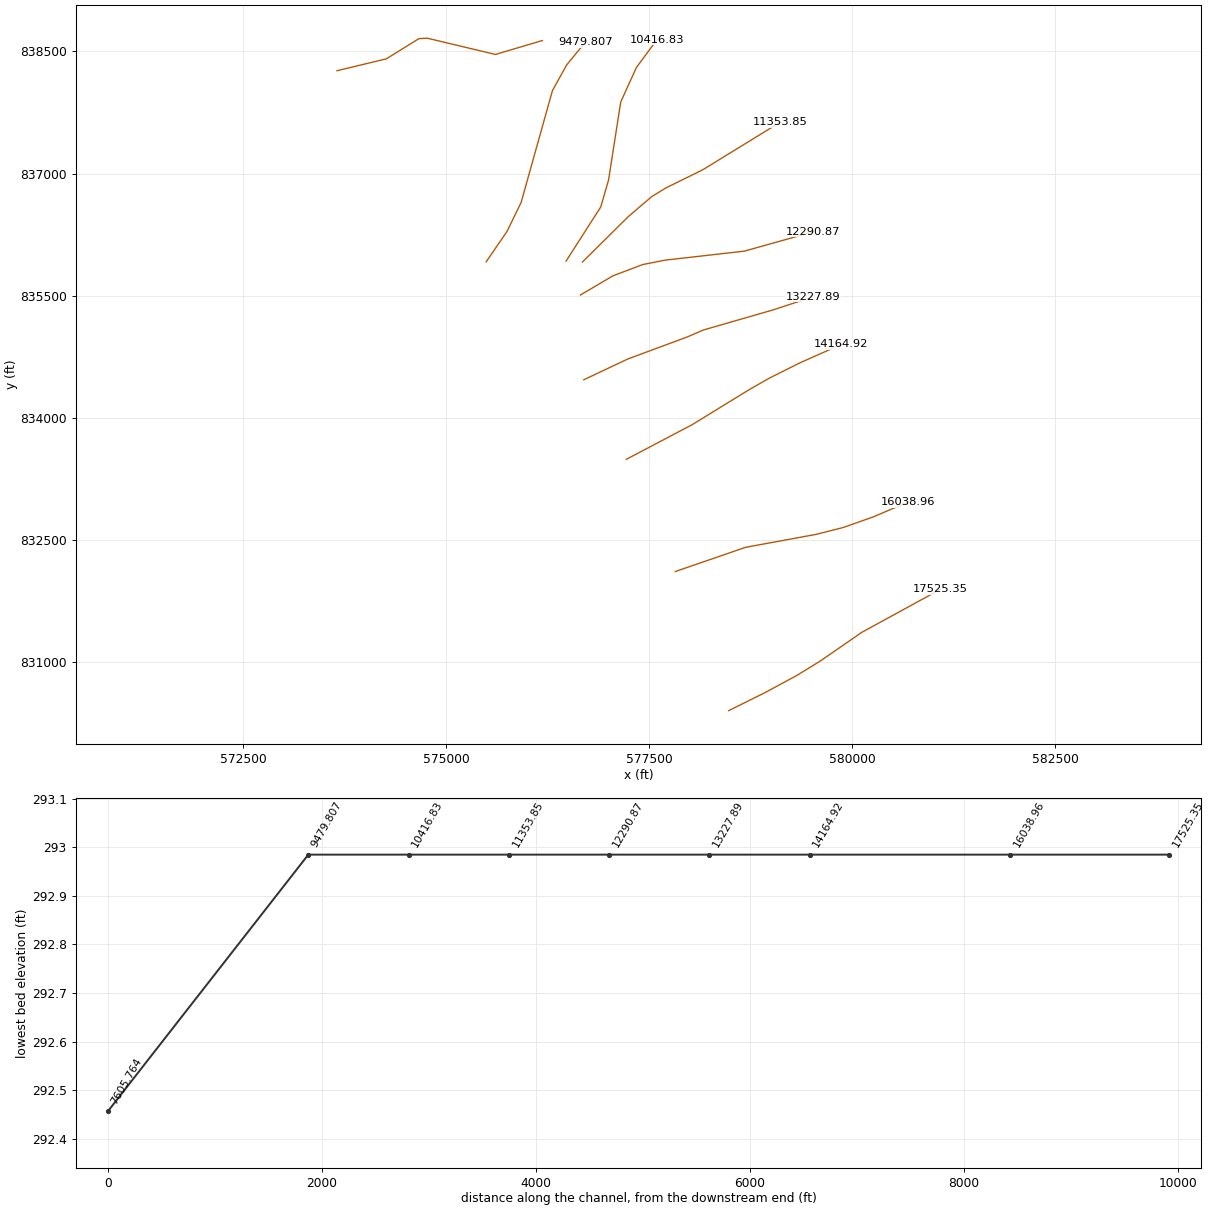
HEC-RAS study 10395_ras.prj: 10395

--- 10395_ras.g01 (geometry) --- (continued)

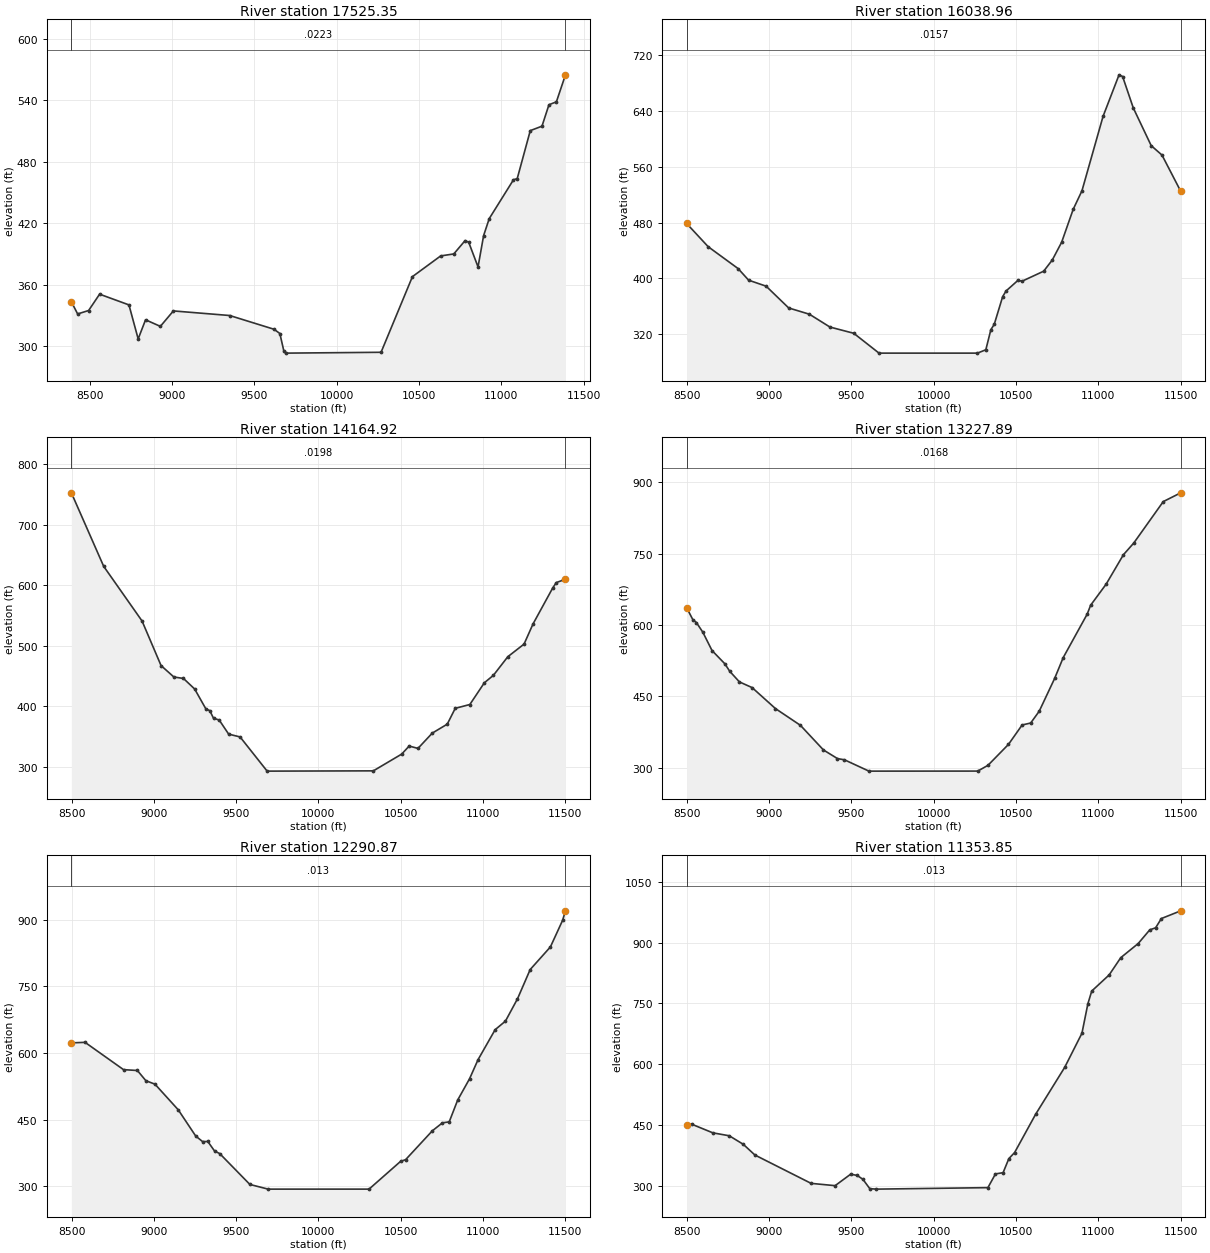
Type RM Length L Ch R = 1 ,17525.35,1486.395400,1486.395400,1486.395400
XS GIS Cut Line= 6
578480.823092741830404.786523008578937.394423351830630.657700086
579316.052145587830835.199424652579605.790854333 831012.47789202
 580117.18356011831365.322017644 581083.60455355831892.199102638
#Sta/Elev= 30
8387.594343.18838425.612331.27328492.356334.6138  8559.1350.58618737.435340.1053
8793.463306.85168838.284325.5508 8928.21319.12539007.364334.21869349.396329.7379
9618.786 316.3099654.324 312.1349678.302295.18529690.458 292.98510269.14293.8045
10459.71367.716110631.32387.958710710.96 389.89210779.71402.933710801.65401.3071
10858.33377.223310892.34407.878510926.35424.416511073.71462.371811096.38463.4584
11175.73510.371411246.85514.724311289.09535.642811334.44538.530411389.53564.8845
#Mann= 3 , 0 , 0
8387.594  0.0223       08387.594  0.0223       011389.53  0.0223       0
#XS Ineff= 2 , 0
       09479.851                       0
Bank Sta=8387.594,11389.53
Exp/Cntr=0.3,0.1

Type RM Length L Ch R = 1 ,16038.96,1874.043500,1874.043500,1874.043500
XS GIS Cut Line= 6
577822.710713425832112.509809503578688.101285407832410.017651081
579559.352414038832569.585923752579891.671780281832653.818756925
580261.392468214832784.168796767580689.067760688832966.586419273
#Sta/Elev= 30
8499.045 478.7148630.202445.38768812.062414.05578875.885397.46628982.169388.8831
9119.198357.69529245.014348.72289369.833330.34029514.466321.42069667.999 292.985
10265.99 292.985 10316.9297.788410347.59326.582910368.05334.208210419.32373.9715
10439.91382.032910512.23397.235110537.72396.070210668.37410.346810720.92426.4577
 10777.7451.877110847.57498.870310900.92  525.4911029.13632.105111126.33691.6127
11147.95689.2061 11212.8644.216711321.66590.186411387.23576.661911500.95524.8633
#Mann= 3 , 0 , 0
8499.045  0.0157       08499.045  0.0157       011500.95  0.0157       0
#XS Ineff= 2 , 0
       0                               0
Bank Sta=8499.045,11500.95
Exp/Cntr=0.3,0.1

Type RM Length L Ch R = 1 ,14164.92,937.021800,937.021800,937.021800
XS GIS Cut Line= 6
577219.808474054833490.296299102 578030.32817497833915.889051043
578741.649428242834351.670098005 578988.14042576834491.557881475
579352.036897779834673.014072779  579865.7480596834900.916406904
#Sta/Elev= 30
8499.013752.8316  8695.4631.34718928.362541.09649043.966467.37459121.767448.5185
9180.021446.11669248.042428.69459316.958395.44119339.838392.99299362.719380.3106
9397.039377.47879454.632354.13249523.952349.48789688.514 292.98510333.74293.4402
10505.88321.120210551.29334.407410604.94330.549610691.82355.819510782.75 370.596
10831.17396.734110920.04403.073311008.06438.964811062.94451.261111150.74482.0397
11249.46502.926411303.96536.233811423.86595.806911445.66604.609311500.97610.0017
#Mann= 3 , 0 , 0
8499.013  0.0198       08499.013  0.0198       011500.97  0.0198       0
#XS Ineff= 2 , 0
       0                               0
Bank Sta=8499.013,11500.97
Exp/Cntr=0.3,0.1

Type RM Length L Ch R = 1 ,13227.89,937.021800,937.021800,937.021800
XS GIS Cut Line= 6
576697.253066096834468.055854612577238.781642365834722.860497543
577978.736511252834996.455403925578162.964109347 835076.98600802
579026.575749584835325.477848032579515.430664792835485.343026749
#Sta/Elev= 30
8499.041636.73318536.559611.76418558.701605.31388597.389585.2496 8653.43546.6062
8731.368 518.7088761.254502.87988819.993480.5789  8897.1468.64719039.016424.4758
9190.718389.25629330.384337.50139415.744319.3529  9458.2316.79919606.793 292.985
10267.88293.083510330.13 305.22610454.62349.268210537.61390.069910589.48394.1454
10641.35 418.988 10734.9487.8542   10787531.645910932.87623.224310953.71641.8584
 11047.9686.199211152.82748.040311215.77772.679411394.91859.798111500.97 878.256
#Mann= 3 , 0 , 0
8499.041  0.0168       08499.041  0.0168       011500.97  0.0168       0
#XS Ineff= 2 , 0
       0                               0
Bank Sta=8499.041,11500.97
Exp/Cntr=0.3,0.1

Type RM Length L Ch R = 1 ,12290.87,937.021700,937.021700,937.021700
XS GIS Cut Line= 6
576655.488114914835508.602325067577055.677040131835744.006326573
577422.307073599835882.446151737577696.849221555 835936.40655965
578672.952676879836047.058066672579521.610139384836284.136993619
#Sta/Elev= 30
8499.041622.82928582.134624.06118815.878562.47268900.154560.54178951.683537.5272
9007.006529.71419148.487471.82449254.559412.68149296.559400.13089327.763400.4909
9369.257378.83089400.197373.19759583.642303.5146 9694.65 292.98510307.59292.9973
10499.31355.653210529.72359.4172 10692.4424.625610753.66442.533510794.66444.7025
10846.28 494.07910918.27541.929210969.83 584.98511073.55652.542211136.28671.9284
11209.49722.241711286.56 788.25911409.42839.252911483.39899.135311500.94920.6718
#Mann= 3 , 0 , 0
8499.041   0.013       08499.041   0.013       011500.94   0.013       0
#XS Ineff= 2 , 0
       0                               0
Bank Sta=8499.041,11500.94
Exp/Cntr=0.3,0.1

Type RM Length L Ch R = 1 ,11353.85,937.021800,937.021800,937.021800
XS GIS Cut Line= 6
 576679.90205656835913.342689591 577243.95759421836470.486626561
577530.777495261836715.097830954577703.358374765836821.104880658
578162.244467235837046.834098449579114.809440613837630.488881511
#Sta/Elev= 30
8499.085452.05738529.999452.82338658.466431.53398758.327424.3191 8843.28403.3555
8913.901376.98039255.361307.18229401.331301.49849495.901329.80149535.148 326.729
9570.317317.13059612.027294.11089652.299 292.98510329.67296.651710375.48330.4157
10421.91333.489210456.84368.083910491.76382.979210619.82 477.47310795.82592.5233
10900.91676.6994 10936.9749.160510960.41780.570511066.21820.250111136.75862.7335
11242.55897.505811313.09931.244111348.36936.215611383.62959.078311500.96978.0402
#Mann= 3 , 0 , 0
8499.085   0.013       08499.085   0.013       011500.96   0.013       0
#XS Ineff= 2 , 0
       0                               0
Bank Sta=8499.085,11500.96
Exp/Cntr=0.3,0.1

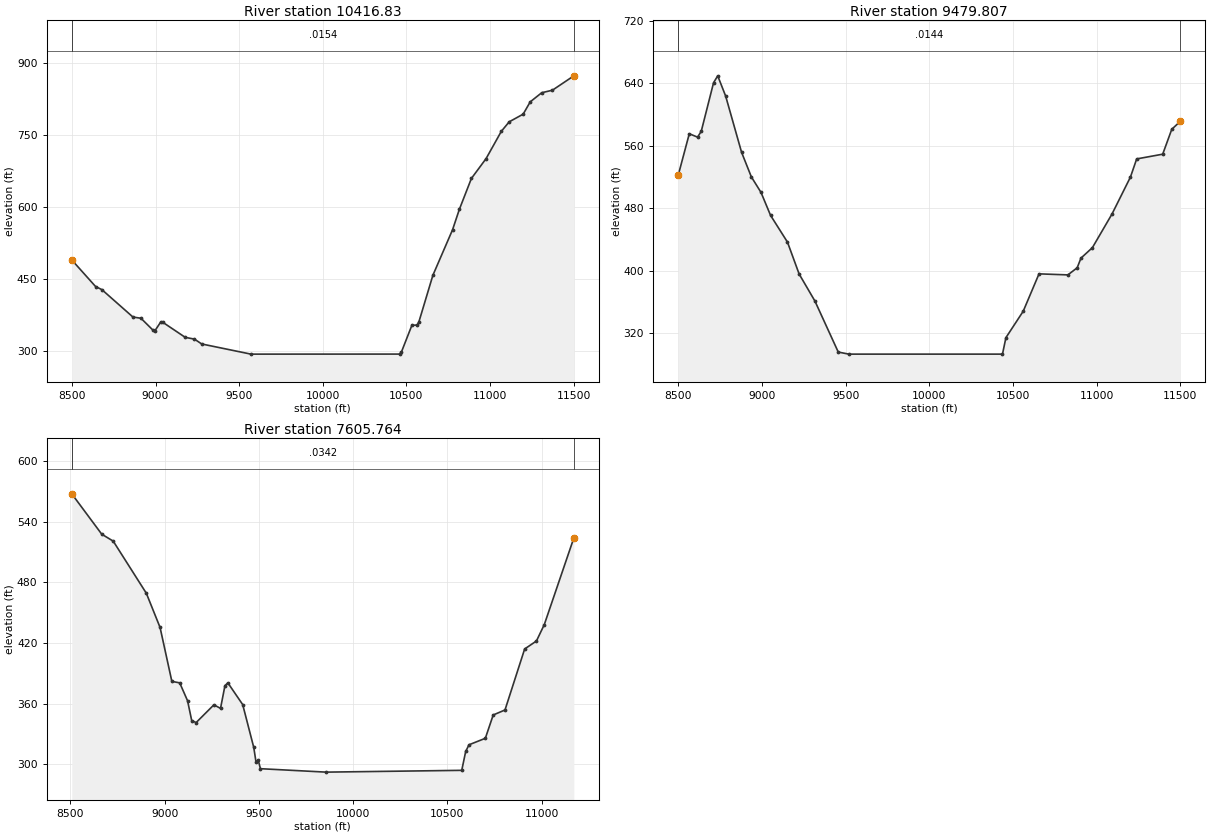
Type RM Length L Ch R = 1 ,10416.83,937.021800,937.021800,937.021800
XS GIS Cut Line= 6
 576478.68635385835925.063734416576905.183499133836589.407066379
577001.222496133836919.420200907 577151.19833953837878.329944104
577345.354816111838304.188348291577597.421523426838643.119488914
#Sta/Elev= 30
8499.043489.18748641.357433.83468679.198 427.2968864.919370.19058912.621367.7337
8983.641343.22678995.257341.16559030.104359.49399041.719359.66479177.405327.9372
9232.653324.21399276.195314.10819570.318 292.98510459.94293.071610470.29297.5806
10532.42352.878410563.59353.616110574.05359.646910658.18457.217810776.02552.2558
10816.74594.798710888.46658.9176 10976.3700.273711067.39757.059211114.54776.8664
11198.04792.849611240.17818.421311308.78837.417611372.94 842.71311500.97872.6461
#Mann= 3 , 0 , 0
8499.043  0.0154       08499.043  0.0154       011500.97  0.0154       0
#XS Ineff= 2 , 0
       0                               0
Bank Sta=8499.043,11500.97
Exp/Cntr=0.3,0.1

Type RM Length L Ch R = 1 ,9479.807,1874.043500,1874.043500,1874.043500
XS GIS Cut Line= 6
575494.642530081835915.549336551 575752.09810819836290.265797507
575925.343072031 836645.83574189576311.021146216838019.460392138
576486.443758488838334.317709227576715.979868253838612.655491951
#Sta/Elev= 30
8499.049522.18558565.147575.30988614.506570.96568636.504578.32248710.189640.6166
8735.096649.50798782.634623.52968877.735551.55078936.211520.03618993.859500.2089
9051.107 470.7149152.123436.49979221.894395.6084  9316.4360.92269455.778295.6457
9518.946 292.98510437.71 292.98510458.31314.126310561.78347.980610656.14 395.821
10828.86394.494310884.44403.645310906.93415.972610975.32429.396511092.82472.5852
11202.79519.829511240.06543.051411395.68549.1303 11449.9581.043711500.94591.2195
#Mann= 3 , 0 , 0
8499.049  0.0144       08499.049  0.0144       011500.94  0.0144       0
#XS Ineff= 2 , 0
       0                               0
Bank Sta=8499.049,11500.94
Exp/Cntr=0.3,0.1

Type RM Length L Ch R = 1 ,7605.764,0.000000,0.000000,0.000000
XS GIS Cut Line= 6
573658.329848945838262.568379447574265.968737811838408.401712805
574667.010404497838656.665601686574771.177071154838661.873935014
575608.850682259838462.221157238576185.239571154838633.228101686
#Sta/Elev= 30
8506.784567.41458665.844 527.5348726.759520.66958902.475469.17418975.375435.3669
9037.861382.10559079.518 380.6499121.175362.9625 9143.22343.41499166.742341.4249
 9260.83358.92379296.113355.46039319.635377.9208 9335.12 380.6499413.724359.2059
9472.529316.7994 9484.29302.58199496.051304.39679507.812295.84649856.413 292.456
10576.11294.223410596.98312.840410614.63319.477910701.28325.877310743.01348.9106
10805.59353.8754 10909.9414.122310972.49422.019211014.21438.263111170.92523.8376
#Mann= 3 , 0 , 0
8506.784  0.0342       08506.784  0.0342       011170.92  0.0342       0
#XS Ineff= 2 , 0
       0                               0
Bank Sta=8506.784,11170.92
Exp/Cntr=0.3,0.1